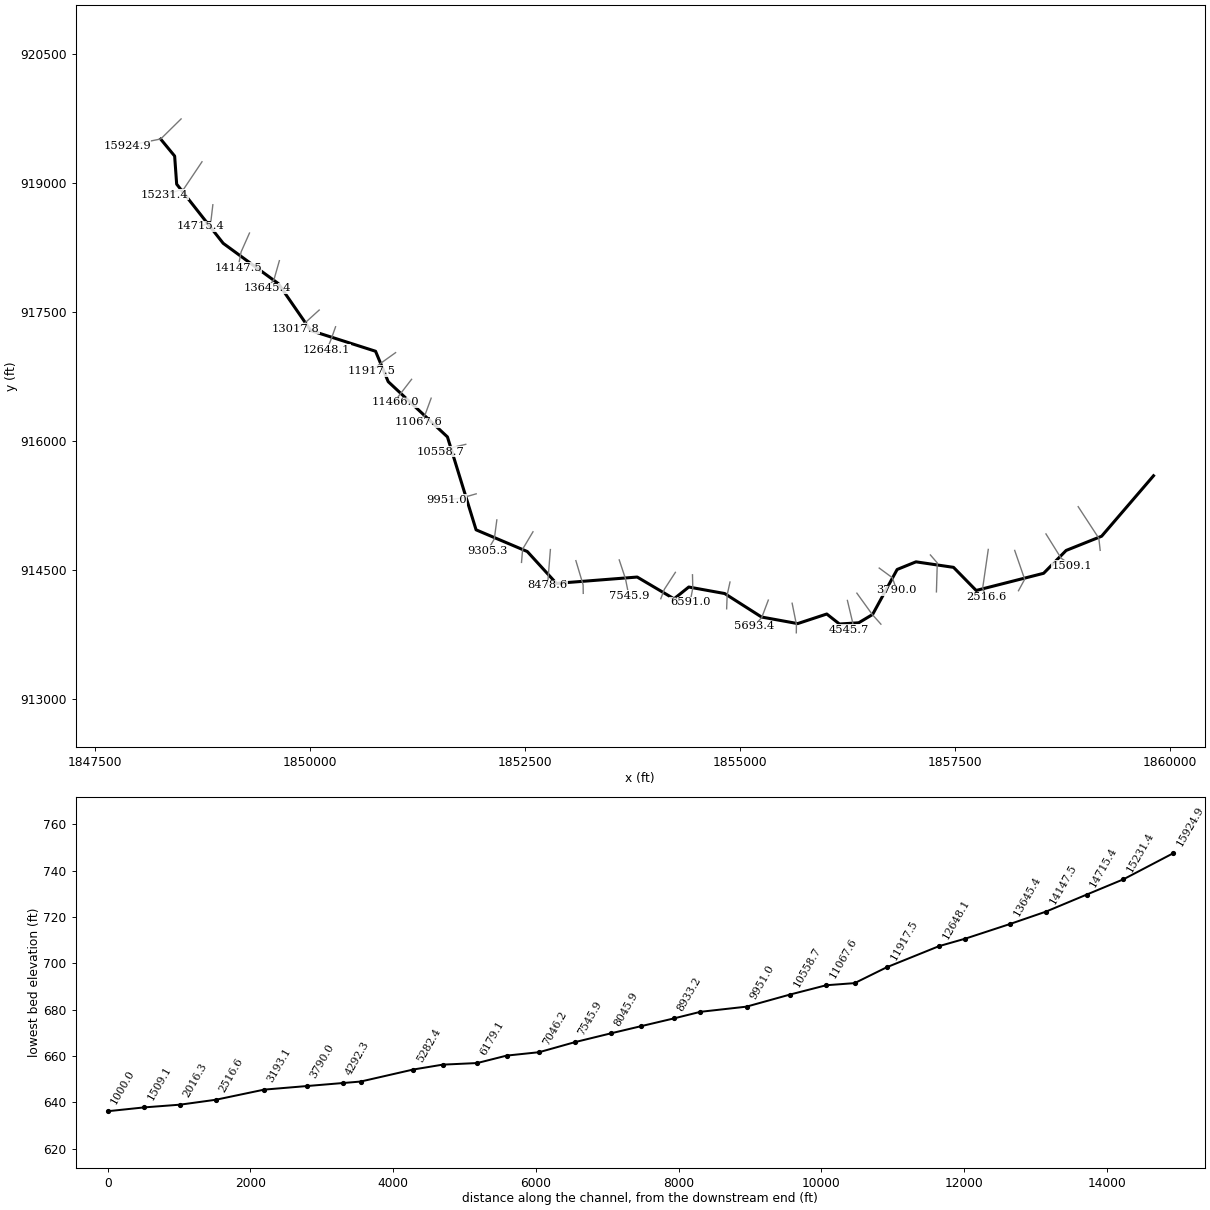
--- GRAYS BRANCH TRIBUTARY 2.PRJ (project) ---

Proj Title=Grays Branch Tributary 2
Current Plan=p01
Default Exp/Contr=0.3,0.1
English Units
Geom File=g01
Flow File=f01
Plan File=p01
Y Axis Title=Elevation
X Axis Title(PF)=Main Channel Distance
X Axis Title(XS)=Station
BEGIN DESCRIPTION:
GRAYS BRANCH TRIBUTARY 2
END DESCRIPTION:
DSS Export Rating Curves= 0
DSS Export Rating Curve Sorted= 0
DSS Export Volume Flow Curves= 0
DXF OffsetX= 0
DXF OffsetY= 0
DXF ScaleX= 1
DXF ScaleY= 10

--- GRAYS BRANCH TRIBUTARY 2.p01 (plan) ---

Plan Title=100-Year-Single
Program Version=3.10
Short Identifier=Plan01
Geom File=g01
Flow File=f01
Subcritical Flow
K Sum by GR= 0
Std Step Tol= 0.01
Critical Tol= 0.01
Num of Std Step Trials= 20
Max Error Tol= 0.3
Flow Tol Ratio= 0.001
Split Flow NTrial= 30
Split Flow Tol= 0.02
Split Flow Ratio= 0.02
Log Output Level= 0
Friction Slope Method= 1
Unsteady Friction Slope Method= 2
Parabolic Critical Depth
Global Vel Dist= 0 , 0 , 0
Global Log Level= 0
CheckData=True
Encroach Param=-1 ,0,0, 2
Encroach River=GraysBranchTribu
Encroach Reach=Reach - 1
Encroach Node=15924.9
       4      .7
Encroach Node=15231.4
       1    4975    5035
Encroach Node=14715.4
       4      .7
Encroach Node=14147.5
       4      .7
Encroach Node=13645.4
       4      .7
Encroach Node=13017.8
       4      .7
Encroach Node=12648.1
       4      .7
Encroach Node=11917.5
       4      .7
Encroach Node=11466.0
       4      .7
Encroach Node=11067.6
       4      .7
Encroach Node=10558.7
       4      .7
Encroach Node=9951.0
       4      .7
Encroach Node=9305.3
       1 4964.87 5095.85
Encroach Node=8933.2
       1 4915.18 5017.64
Encroach Node=8478.6
       1 4869.66 5022.97
Encroach Node=8045.9
       1 4882.03  5005.8
Encroach Node=7545.9
       1 4931.32 5073.46
Encroach Node=7046.2
       1 4983.84 5033.19
Encroach Node=6591.0
       1 4984.51 5054.91
Encroach Node=6179.1
       1 4946.01 5043.77
Encroach Node=5693.4
       1 4928.89 5060.76
Encroach Node=5282.4
       1 4912.84 5048.12
Encroach Node=4545.7
       1 4862.98    5019
Encroach Node=4292.3
       1  4872.9 5052.28
Encroach Node=3790.0
       1 4944.58 5047.99
Encroach Node=3193.1
       1  4962.9 5164.22
Encroach Node=2516.6
       1  4798.7    5019
Encroach Node=2016.3
       1 4813.08 5059.11
Encroach Node=1509.1
       1  4839.2 5074.36
Encroach Node=1000.0
       1    4900 5109.51
Encroach Node=447.1
       1    4972    5028
Encroach Node=426.3
       1    4976    5024
Encroach Node=405.6
       1    4976    5024
Encroach Node=286.2
       1    4870 5027.89
Encroach Node=150.5
       1    4960 5018.86
Computation Interval=1HOUR
Output Interval=1HOUR
Run HTab= 0
Run UNet= 0
Run PostProcess= 0
UNET Theta= 1
UNET Theta Warmup= 1
UNET ZTol= 0.02
UNET ZSATol= 0.05
UNET MxIter= 20
UNET MaxInSteps= 1
UNET DtIC= 0
UNET DtMin= 0
UNET MaxCRTS= 20
UNET WFStab= 2
UNET SFStab= 1
UNET WFX= 1
UNET SFX= 1
UNET DSS MLevel= 4
UNET Convert EG Bridges=-1
UNET Use Existing IB Tables=-1
UNET Froude Reduction=False
UNET Froude Limit= 1
UNET Froude Power= 10
Instantaneous Interval=1HOUR
Write IC File= 0
Echo Input=False
Echo Output=False
Write Detailed= 0

--- GRAYS BRANCH TRIBUTARY 2.f01 (steady flow) ---

Flow Title= 100-Year-Single
Program Version=3.10
Number of Profiles= 2
Profile Names=100-Year,AFW
River Rch & RM=GraysBranchTribu,Reach - 1       ,15924.9
     631     631
River Rch & RM=GraysBranchTribu,Reach - 1       ,9951.0
    1150    1150
River Rch & RM=GraysBranchTribu,Reach - 1       ,3790.0
    1426    1426
Boundary for River Rch & Prof#=GraysBranchTribu,Reach - 1       , 1
Up Type= 0
Dn Type= 3
Dn Slope=0.0075
Boundary for River Rch & Prof#=GraysBranchTribu,Reach - 1       , 2
Up Type= 0
Dn Type= 1
Dn Known WS=641.32
DSS Import GetInterval= 0
DSS Import GetPeak= 0
DSS Import FillOption= 0

--- GRAYS BRANCH TRIBUTARY 2.g01 (geometry) ---

Geom Title=Geom 01 by CodeH2 for Windows

River Reach=GraysBranchTribu,Reach - 1
Reach XY= 30
      1848261.43       919510.77      1848423.41       919313.95
      1848446.88        918987.8      1848987.73       918300.29
      1849628.75       917832.43      1850006.08       917286.64
      1850759.28       917046.13      1850906.42       916692.84
         1851595       916050.75      1851928.11       914971.17
      1852523.42       914719.29      1852861.68       914348.91
      1853801.28       914422.62      1854229.65       914169.41
      1854400.94       914306.67      1854818.37       914231.13
      1855246.82       913958.23      1855666.98       913881.84
      1856005.38       913993.13      1856152.62          913877
       1856376.5       913891.19         1856538        913987.5
      1856823.52       914510.55      1857042.25       914599.37
      1857479.07       914535.34      1857742.25       914266.78
      1858526.62       914466.25      1858788.16       914731.57
      1859200.88       914896.88      1859804.37       915599.44

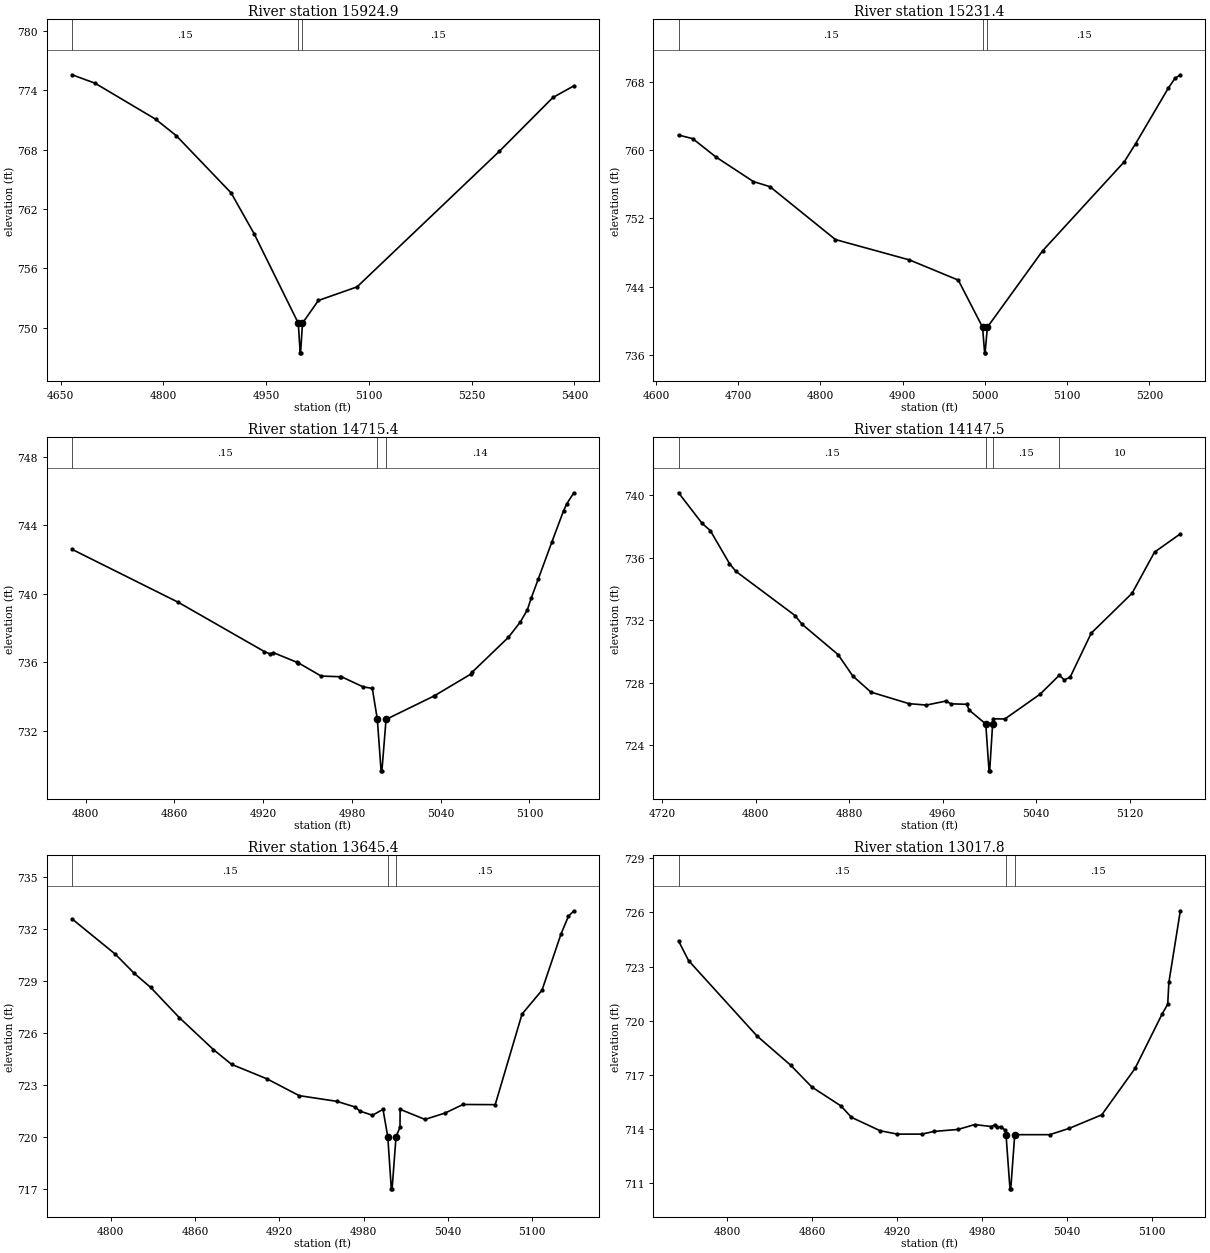
Type RM Length L Ch R = 1 ,15924.9,693.5,693.5,693.5
XS GIS Cut Line= 3
      1848498.46       919745.60      1848261.61       919512.51
      1847869.38       919433.96
BEGIN DESCRIPTION:
Grays Branch Tributary 2 32.0
END DESCRIPTION:
#Sta/Elev= 15
  4666.8  775.56  4700.3  774.71  4788.6  771.08  4818.9  769.41  4898.9  763.63
  4932.3  759.53 4996.92  750.48 4999.72  747.48 5000.28  747.48 5003.08  750.48
  5026.3  752.77  5082.7  754.14  5290.5  767.84  5368.6  773.27  5399.1  774.44
#Mann= 3 , 1 , 0
 4666.80    0.15       0 4996.92    0.05       0 5003.08    0.15       0
Bank Sta=4996.92,5003.08
Exp/Cntr=0.3,0.1

Type RM Length L Ch R = 1 ,15231.4,516,516,516
XS GIS Cut Line= 3
      1848741.45       919247.59      1848530.55       918933.18
      1848309.51       918864.02
BEGIN DESCRIPTION:
Grays Branch Tributary 2 30.0
END DESCRIPTION:
#Sta/Elev= 18
  4627.5  761.75  4644.8  761.32  4672.7   759.2  4718.5  756.31  4738.7  755.71
  4818.3  749.53  4908.3  747.15  4967.7  744.79  4997.2  739.29 4999.72  736.29
 5000.28  736.29 5003.08  739.29  5070.2  748.21  5169.5  758.62  5183.3  760.73
  5223.2  767.25  5231.1  768.36  5237.7  768.79
#Mann= 3 , 1 , 0
 4627.50    0.15       0  4997.2    0.05       0 5003.08    0.15       0
Bank Sta=4997.20,5003.08
Exp/Cntr=0.3,0.1

Type RM Length L Ch R = 1 ,14715.4,567.9,567.9,567.9
XS GIS Cut Line= 3
      1848867.60       918748.46      1848843.40       918543.19
      1848719.62       918496.17
BEGIN DESCRIPTION:
Grays Branch Tributary 2 29.0
END DESCRIPTION:
#Sta/Elev= 30
  4790.9   742.6  4862.7  739.51  4920.8  736.64  4924.7   736.5  4926.8  736.58
  4942.9  736.01  4943.5  735.99  4943.8  735.98  4959.2  735.21  4971.9  735.17
  4972.7  735.18  4987.5  734.58  4993.8  734.49  4997.2  732.68 4999.72  729.68
 5000.28  729.68 5003.08  732.68  5035.6  734.05    5036  734.07  5060.3  735.32
  5061.1  735.42  5085.8  737.47  5093.9  738.37  5098.6  739.08  5101.2  739.76
    5106  740.88  5115.1  743.02    5123  744.84  5125.3  745.27    5130   745.9
#Mann= 3 , 1 , 0
 4790.90    0.15       0  4997.2    0.05       0 5003.08    0.14       0
Bank Sta=4997.20,5003.08
Exp/Cntr=0.3,0.1

Type RM Length L Ch R = 1 ,14147.5,502.1,502.1,502.1
XS GIS Cut Line= 3
      1849293.58       918419.75      1849196.24       918200.57
      1849159.70       918014.35
BEGIN DESCRIPTION:
Grays Branch Tributary 2 28.0
END DESCRIPTION:
#Sta/Elev= 30
  4733.9  740.16  4754.1   738.2  4761.1  737.74  4777.5  735.63    4783  735.13
  4833.7   732.3  4839.4  731.76  4870.5   729.8  4883.1  728.43  4898.6   727.4
  4931.3  726.66  4946.1  726.57    4963  726.83    4967  726.65  4980.6  726.62
  4982.7  726.25 4996.92  725.36 4999.72  722.36 5000.28  722.36  5002.8  725.36
  5003.4  725.69  5013.3  725.68  5043.5  727.27  5059.9  728.48  5064.2  728.18
  5069.2  728.36  5087.2  731.17  5122.2  733.73  5141.4  736.36  5163.5  737.53
#Mann= 4 , 1 , 0
 4733.90    0.15       0 4996.92    0.05       0  5002.8    0.15       0
  5059.9      10       0
Bank Sta=4996.92,5002.80
Exp/Cntr=0.3,0.1

Type RM Length L Ch R = 1 ,13645.4,627.6,627.6,627.6
XS GIS Cut Line= 3
      1849641.13       918098.35      1849578.56       917879.53
      1849498.92       917777.15
BEGIN DESCRIPTION:
Grays Branch Tributary 2 27.0
END DESCRIPTION:
#Sta/Elev= 29
  4772.4  732.58  4803.2  730.55  4816.6  729.45  4828.4  728.63  4848.7   726.9
  4873.1  725.05    4886   724.2  4911.1  723.37  4934.1   722.4    4961  722.07
  4974.1  721.74  4977.3  721.51  4986.3  721.27  4993.8  721.61  4997.2  720.03
 4999.72  717.03 5000.28  717.03 5003.08  720.03  5005.9  720.58    5006  721.61
  5023.7  721.03  5038.1   721.4  5050.8  721.89  5073.7  721.88  5092.8   727.1
    5107  728.47  5120.5   731.7  5125.8  732.73  5129.7  733.05
#Mann= 3 , 1 , 0
 4772.40    0.15       0  4997.2    0.05       0 5003.08    0.15       0
Bank Sta=4997.20,5003.08
Exp/Cntr=0.3,0.1

Type RM Length L Ch R = 1 ,13017.8,369.7,369.7,369.7
XS GIS Cut Line= 3
      1850103.97       917524.93      1849931.42       917368.74
      1849826.47       917306.82
BEGIN DESCRIPTION:
Grays Branch Tributary 2 26.0
END DESCRIPTION:
#Sta/Elev= 30
  4765.5  724.42  4772.6  723.33  4820.9  719.16  4844.7  717.54  4859.7  716.33
  4880.3  715.28  4887.7  714.65  4907.9  713.91  4920.2  713.72  4937.5  713.72
  4946.1  713.87    4963  713.98  4974.8  714.25  4986.6  714.14    4989  714.24
  4990.4  714.12  4993.1  714.14  4996.2  713.94 4996.92  713.69 4999.72  710.69
 5000.28  710.69 5003.08  713.69  5027.8  713.69  5041.6  714.04  5064.6  714.79
  5088.1  717.36  5107.1  720.35  5111.2  720.92    5112  722.12  5120.1  726.09
#Mann= 3 , 1 , 0
 4765.50    0.15       0 4996.92    0.05       0 5003.08    0.15       0
Bank Sta=4996.92,5003.08
Exp/Cntr=0.3,0.1

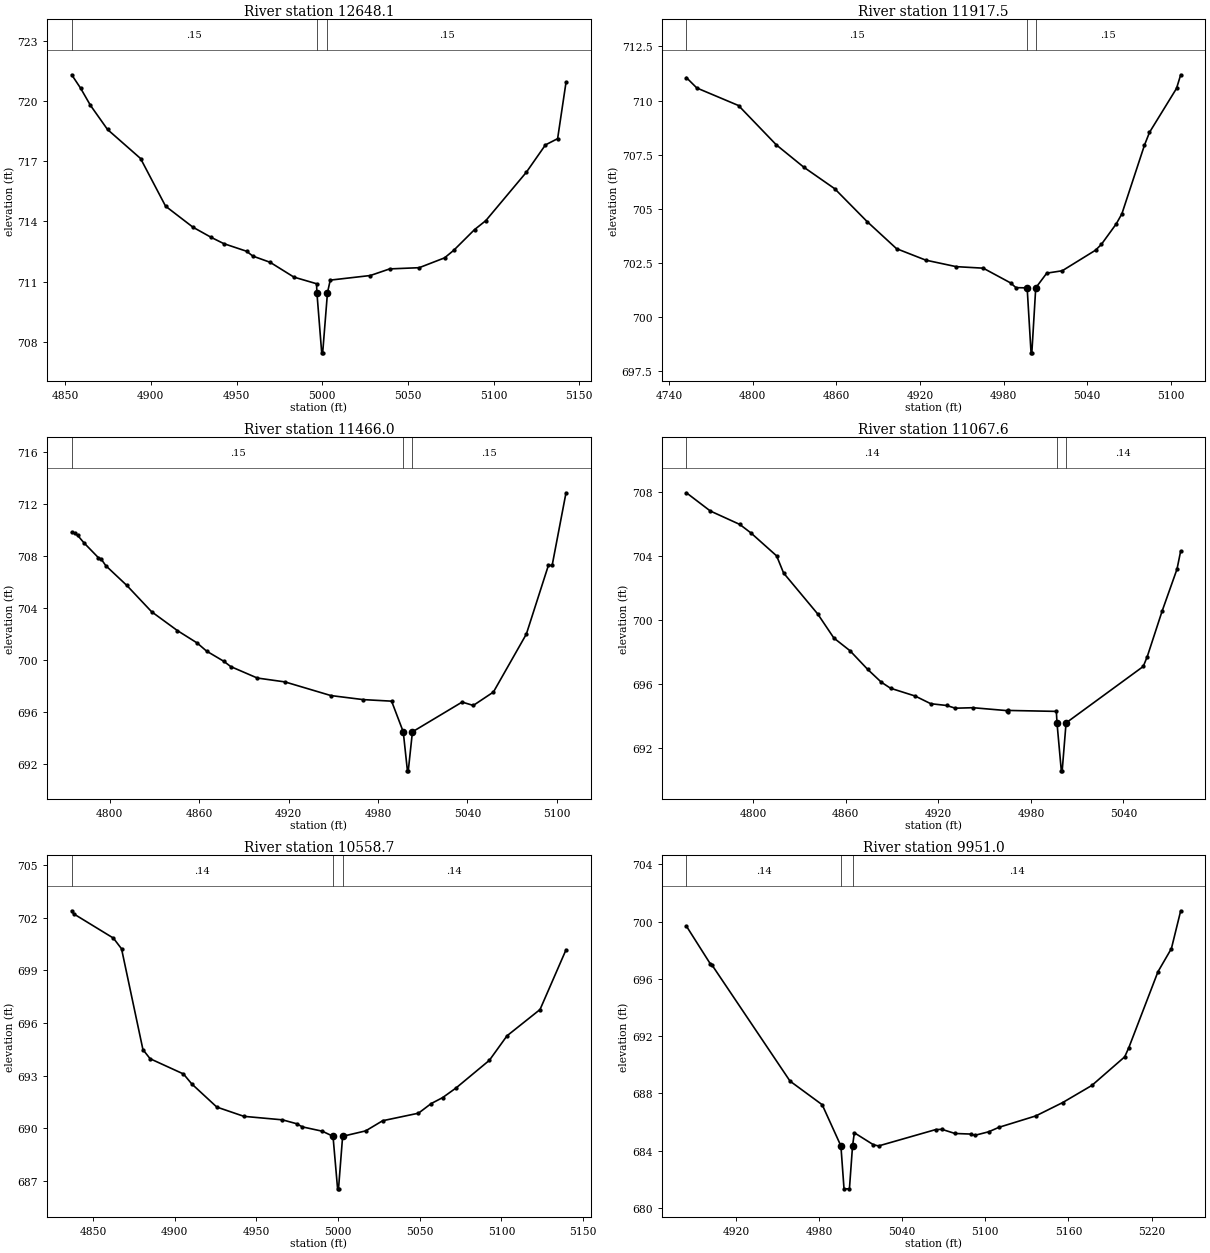
Type RM Length L Ch R = 1 ,12648.1,730.6,730.6,730.6
XS GIS Cut Line= 3
      1850294.38       917330.75      1850245.74       917192.88
      1850192.00       917061.12
BEGIN DESCRIPTION:
Grays Branch Tributary 2 25.0
END DESCRIPTION:
#Sta/Elev= 30
  4853.8  721.32    4859  720.65  4864.7   719.8  4874.7  718.59    4894  717.14
  4908.6  714.76  4924.6  713.71  4935.3   713.2  4942.6  712.89  4955.9  712.51
  4959.5  712.27  4969.6  711.96  4983.5  711.22  4996.7  710.89 4996.92  710.44
 4999.72  707.44 5000.28  707.44 5003.08  710.44  5004.7  711.07  5028.1   711.3
  5039.4  711.63  5056.6  711.69  5071.4  712.18  5076.8  712.56  5088.9  713.59
  5095.5  714.04  5119.2  716.46  5130.3  717.82  5137.4  718.13  5142.3  720.94
#Mann= 3 , 1 , 0
 4853.80    0.15       0 4996.92    0.05       0 5003.08    0.15       0
Bank Sta=4996.92,5003.08
Exp/Cntr=0.3,0.1

Type RM Length L Ch R = 1 ,11917.5,451.5,451.5,451.5
XS GIS Cut Line= 3
      1850992.21       917029.96      1850827.17       916912.08
      1850708.95       916816.74
BEGIN DESCRIPTION:
Grays Branch Tributary 2 24.0
END DESCRIPTION:
#Sta/Elev= 27
  4752.4  711.06  4759.9  710.58  4789.8  709.77    4817  707.95  4836.7  706.92
  4858.8  705.93  4882.1  704.41  4903.2  703.16  4924.2  702.63    4946  702.33
  4965.4  702.26    4985  701.58  4988.9  701.36 4996.92  701.35 4999.72  698.35
 5000.28  698.35 5003.08  701.35    5011  702.03  5022.1  702.14    5046  703.09
  5050.2  703.36  5060.8   704.3  5064.9  704.77  5081.1  707.94  5084.7  708.53
  5104.1  710.56  5107.1  711.19
#Mann= 3 , 1 , 0
 4752.40    0.15       0 4996.92    0.05       0 5003.08    0.15       0
Bank Sta=4996.92,5003.08
Exp/Cntr=0.3,0.1

Type RM Length L Ch R = 1 ,11466.0,398.4,398.4,398.4
XS GIS Cut Line= 3
      1851178.36       916720.26      1851024.77       916521.29
      1850985.80       916451.15
BEGIN DESCRIPTION:
Grays Branch Tributary 2 23.0
END DESCRIPTION:
#Sta/Elev= 30
  4774.5  709.83  4776.4  709.77  4778.5  709.59  4782.8  709.01  4792.3  707.89
  4794.4  707.75  4797.4  707.26  4811.5  705.74  4828.1  703.72  4845.4  702.27
  4858.6  701.32    4865  700.69  4876.5  699.91  4881.2   699.5    4899  698.62
  4917.6  698.32  4948.4  697.27    4970  696.96  4989.1  696.84 4996.92  694.48
 4999.72  691.48 5000.28  691.48 5003.08  694.48  5036.4  696.77  5043.9  696.51
  5057.4  697.54  5079.5     702  5094.3  707.29  5096.8  707.28  5106.1  712.87
#Mann= 3 , 1 , 0
 4774.50    0.15       0 4996.92    0.05       0 5003.08    0.15       0
Bank Sta=4996.92,5003.08
Exp/Cntr=0.3,0.1

Type RM Length L Ch R = 1 ,11067.6,508.9,508.9,508.9
XS GIS Cut Line= 3
      1851405.91       916501.16      1851334.00       916305.59
      1851261.12       916220.50
BEGIN DESCRIPTION:
Grays Branch Tributary 2 22.0
END DESCRIPTION:
#Sta/Elev= 30
  4756.7  707.96  4772.2  706.82  4791.3  705.98  4798.5  705.45  4815.2  704.01
  4819.7  702.94  4841.8  700.38  4852.3  698.87  4862.7  698.08  4874.1  696.92
    4883  696.11    4889  695.73    4905  695.24  4915.1  694.76  4925.4  694.65
    4931  694.48  4942.5  694.51  4964.3  694.33    4965  694.24  4965.1  694.34
  4996.5  694.28 4996.92  693.56 4999.72  690.56 5000.28  690.56  5002.8  693.56
  5052.8  697.09  5055.4   697.7    5065  700.54  5074.7  703.18  5077.1  704.32
#Mann= 3 , 1 , 0
 4756.70    0.14       0 4996.92   0.045       0  5002.8    0.14       0
Bank Sta=4996.92,5002.80
Exp/Cntr=0.3,0.1

Type RM Length L Ch R = 1 ,10558.7,607.7,607.7,607.7
XS GIS Cut Line= 3
      1851808.21       915964.61      1851649.59       915927.10
      1851518.46       915879.50
BEGIN DESCRIPTION:
Grays Branch Tributary 2 21.0
END DESCRIPTION:
#Sta/Elev= 28
    4837  702.41  4838.3  702.23  4862.5  700.85  4867.5  700.24  4880.6  694.48
    4885  693.96  4905.4  693.09  4910.5  692.52  4925.8   691.2  4942.4  690.67
    4966  690.47  4974.6  690.25  4978.1  690.07  4990.4  689.82 4996.92  689.53
 4999.72  686.53 5000.28  686.53  5002.8  689.53  5016.9  689.84  5027.3  690.42
  5049.2  690.85    5057   691.4    5064  691.74  5072.2  692.29  5092.6  693.87
  5103.4  695.27  5123.6  696.77  5139.5  700.18
#Mann= 3 , 1 , 0
 4837.00    0.14       0 4996.92   0.045       0  5002.8    0.14       0
Bank Sta=4996.92,5002.80
Exp/Cntr=0.3,0.1

Type RM Length L Ch R = 1 ,9951.0,645.7,645.7,645.7
XS GIS Cut Line= 3
      1851929.21       915389.57      1851758.05       915340.13
      1851580.98       915317.28
BEGIN DESCRIPTION:
Grays Branch Tributary 2 20.0
END DESCRIPTION:
#Sta/Elev= 27
  4884.3  699.69  4901.5  697.06  4902.7  696.98  4959.1  688.85  4982.3   687.2
  4995.8  684.32 4998.05  681.32 5001.95  681.32  5004.2  684.32  5005.5  685.24
  5019.3   684.4    5023  684.32  5064.1  685.46  5068.7  685.48  5078.1  685.19
  5089.4  685.15  5092.4  685.06  5102.5  685.31  5109.8  685.62  5136.5  686.42
  5155.8  687.35  5176.9  688.55  5200.6  690.55  5203.6   691.2  5224.6   696.5
  5234.3  698.12    5241  700.76
#Mann= 3 , 1 , 0
 4884.30    0.14       0  4995.8   0.045       0  5004.2    0.14       0
Bank Sta=4995.80,5004.20
Exp/Cntr=0.3,0.1

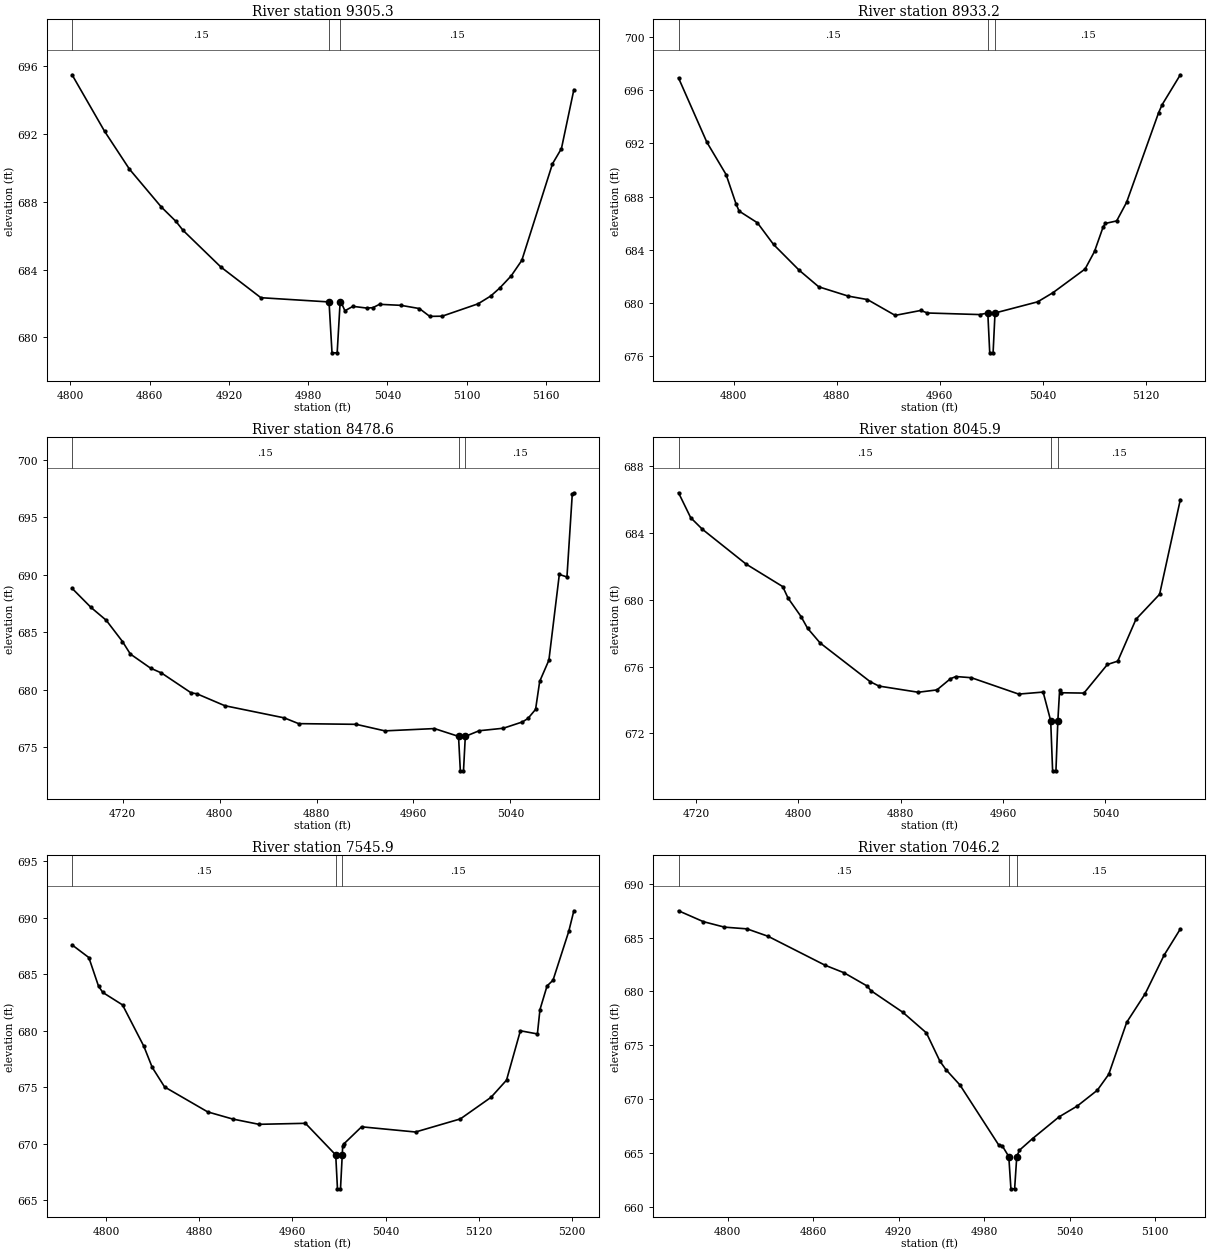
Type RM Length L Ch R = 1 ,9305.3,372.1,372.1,372.1
XS GIS Cut Line= 3
      1852169.41       915086.95      1852140.06       914865.91
      1852061.38       914730.25
BEGIN DESCRIPTION:
Grays Branch Tributary 2 19.0
END DESCRIPTION:
#Sta/Elev= 30
  4801.3  695.48  4825.9  692.15  4844.7  689.92  4868.8  687.69  4879.9  686.84
  4885.3  686.31  4913.9  684.15  4944.2  682.34  4995.8  682.09 4998.05  679.09
 5001.95  679.09  5004.2  682.09  5004.9  682.08  5007.8  681.57  5013.9  681.83
  5024.2  681.73  5028.9  681.75    5034  681.95  5050.2  681.89  5064.2   681.7
    5072  681.24  5081.4  681.25  5108.6  681.98  5118.2  682.44    5125  682.91
  5133.7  683.63  5141.7  684.54  5164.9  690.23  5171.7  691.13  5181.1   694.6
#Mann= 3 , 1 , 0
 4801.30    0.15       0  4995.8    0.05       0  5004.2    0.15       0
Bank Sta=4995.80,5004.20
Exp/Cntr=0.3,0.1

Type RM Length L Ch R = 1 ,8933.2,454.6,454.6,454.6
XS GIS Cut Line= 3
      1852589.62       914948.51      1852469.38       914747.35
      1852456.26       914592.87
BEGIN DESCRIPTION:
Grays Branch Tributary 2 18.0
END DESCRIPTION:
#Sta/Elev= 30
  4757.2  696.93  4779.2  692.09  4794.1  689.66  4801.8  687.46  4804.2  686.91
  4818.4  686.03  4830.9   684.4  4850.8  682.46    4866  681.21  4888.9  680.51
  4903.8  680.25  4925.3  679.06  4945.2  679.43  4950.3  679.24    4991  679.12
  4997.2  679.24  4998.7  676.24  5001.3  676.24  5002.8  679.24  5035.9  680.08
  5047.8  680.77  5072.7  682.55    5080  683.87  5086.6  685.69  5088.4  685.98
  5097.2  686.17  5104.9  687.57  5129.8  694.33  5132.5  694.92  5146.6  697.17
#Mann= 3 , 1 , 0
 4757.20    0.15       0  4997.2    0.05       0  5002.8    0.15       0
Bank Sta=4997.20,5002.80
Exp/Cntr=0.3,0.1

Type RM Length L Ch R = 1 ,8478.6,432.7,432.7,432.7
XS GIS Cut Line= 2
      1852792.08       914741.99      1852759.06       914329.07
BEGIN DESCRIPTION:
Grays Branch Tributary 2 17.0
END DESCRIPTION:
#Sta/Elev= 30
  4678.2  688.82  4693.8  687.16  4706.4  686.04  4719.8  684.19  4726.3   683.1
    4743  681.87    4752  681.45  4776.5  679.72  4781.2  679.64  4804.3   678.6
  4853.4  677.54  4865.2  677.04  4912.7  676.98  4936.4  676.41  4977.3  676.61
  4997.2  675.93  4998.7  672.93  5001.3  672.93  5002.8  675.93  5014.2  676.42
  5034.2  676.64    5050  677.19  5054.5  677.49  5060.8  678.28  5064.2  680.72
  5071.8  682.57  5080.4  690.03  5086.7  689.81  5091.1  697.04  5092.4  697.14
#Mann= 3 , 1 , 0
 4678.20    0.15       0  4997.2    0.05       0  5002.8    0.15       0
Bank Sta=4997.20,5002.80
Exp/Cntr=0.3,0.1

Type RM Length L Ch R = 1 ,8045.9,500,500,500
XS GIS Cut Line= 3
      1853088.38       914613.15      1853172.52       914331.88
      1853174.01       914233.38
BEGIN DESCRIPTION:
Grays Branch Tributary 2 16.0
END DESCRIPTION:
#Sta/Elev= 30
  4706.4  686.39  4715.9   684.9    4725  684.21  4759.1  682.13  4787.8  680.78
    4792  680.09  4802.1  678.99  4807.2  678.29    4817  677.41  4856.2  675.09
    4863  674.83  4893.7  674.46  4908.3   674.6  4918.9  675.27  4923.1   675.4
  4935.2  675.33  4972.2  674.35  4991.3  674.47  4997.2  672.76  4998.7  669.76
  5001.3  669.76  5002.8  672.76  5004.2  674.61  5005.3  674.43  5023.2  674.41
  5041.5  676.12  5049.6  676.32  5063.8  678.82  5082.3  680.32  5098.5  685.98
#Mann= 3 , 1 , 0
 4706.40    0.15       0  4997.2    0.05       0  5002.8    0.15       0
Bank Sta=4997.20,5002.80
Exp/Cntr=0.3,0.1

Type RM Length L Ch R = 1 ,7545.9,499.7,499.7,499.7
XS GIS Cut Line= 3
      1853592.37       914621.82      1853664.63       914404.41
      1853704.13       914206.72
BEGIN DESCRIPTION:
Grays Branch Tributary 2 15.0
END DESCRIPTION:
#Sta/Elev= 30
  4770.9  687.58  4785.3  686.46  4793.6  683.93  4797.3  683.37  4814.2  682.27
  4832.5  678.61  4839.7  676.74  4850.3  675.01  4887.3   672.8  4908.7  672.17
  4931.3   671.7  4971.2  671.79  4997.2  668.99  4998.7  665.99  5001.3  665.99
  5002.8  668.99  5003.2  669.79  5003.9  669.94  5019.4  671.48  5065.7  671.02
  5104.2  672.18  5130.5  674.09  5143.8  675.61  5155.7  679.98  5170.3   679.7
  5172.5  681.85  5178.6  683.95  5183.7  684.45  5197.2  688.77  5201.6   690.6
#Mann= 3 , 1 , 0
 4770.90    0.15       0  4997.2    0.05       0  5002.8    0.15       0
Bank Sta=4997.20,5002.80
Exp/Cntr=0.3,0.1

Type RM Length L Ch R = 1 ,7046.2,455.2,455.2,455.2
XS GIS Cut Line= 3
      1854245.19       914477.23      1854117.38       914280.74
      1854075.60       914170.91
BEGIN DESCRIPTION:
Grays Branch Tributary 2 14.0
END DESCRIPTION:
#Sta/Elev= 30
  4765.6  687.49    4783  686.48  4797.8  685.97  4813.6  685.81  4828.4  685.12
  4868.4  682.43  4881.7  681.73    4898  680.49  4900.4  680.08  4922.8  678.07
  4939.4  676.15  4948.9  673.52  4953.1  672.74    4963   671.3    4990  665.76
  4992.6  665.66  4997.2  664.66  4998.7  661.66  5001.3  661.66  5002.8  664.66
  5004.7  665.25  5013.9  666.33  5032.4  668.34  5045.2  669.35  5059.3  670.82
  5067.3   672.3  5079.9  677.13  5092.9  679.79  5106.1  683.36  5117.5   685.8
#Mann= 3 , 1 , 0
 4765.60    0.15       0  4997.2    0.05       0  5002.8    0.15       0
Bank Sta=4997.20,5002.80
Exp/Cntr=0.3,0.1

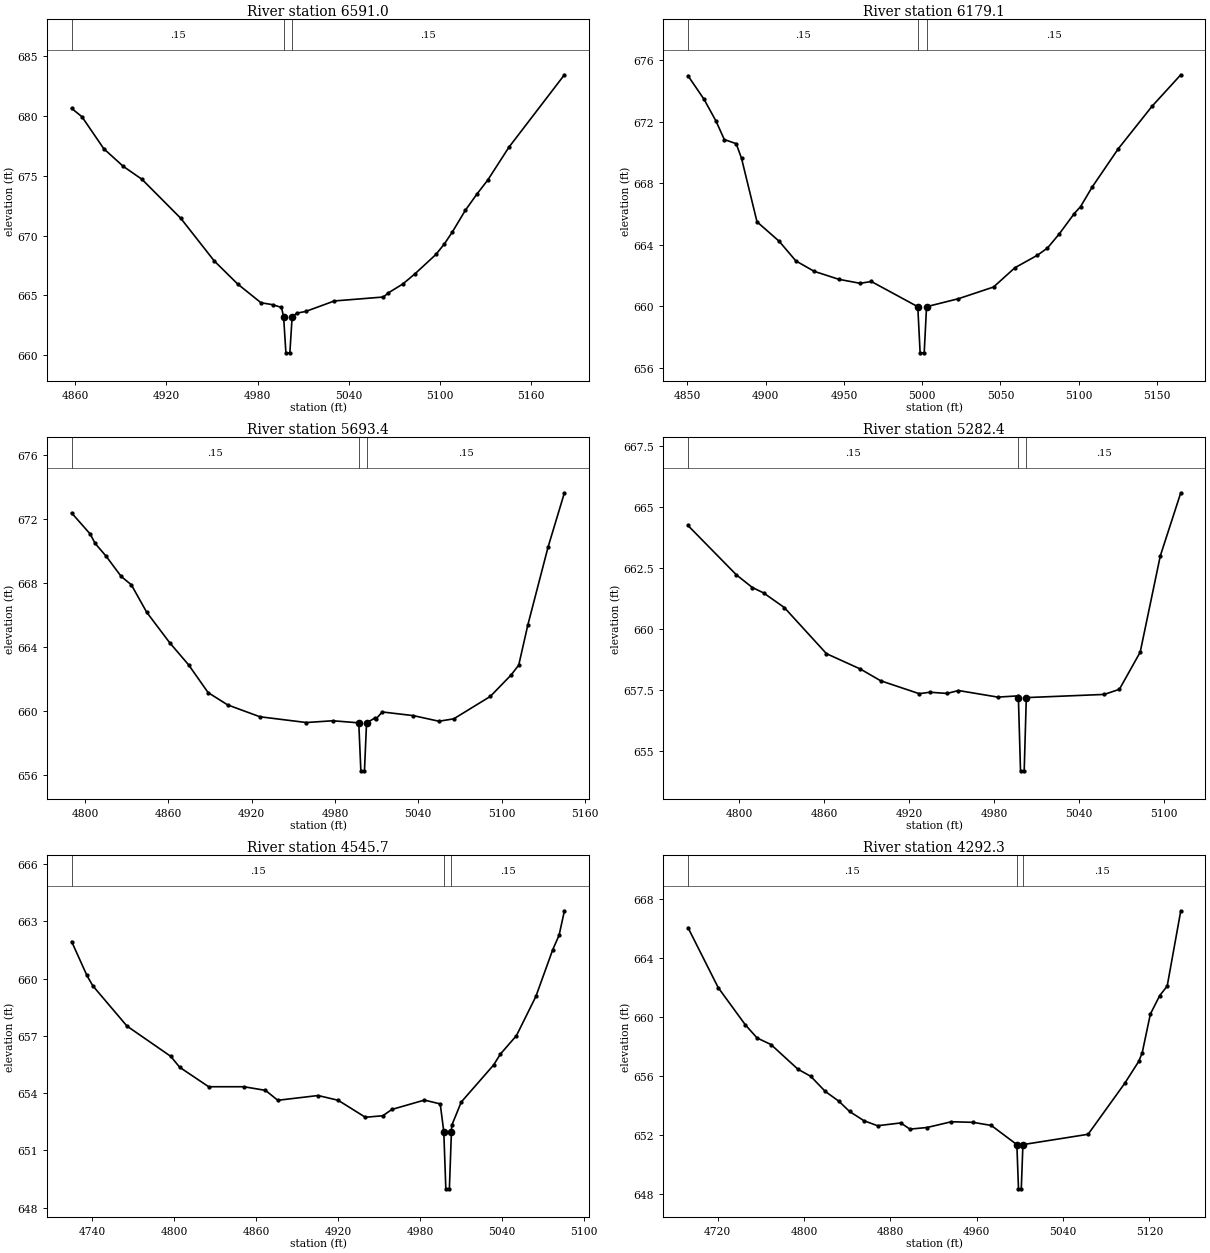
Type RM Length L Ch R = 1 ,6591.0,411.9,411.9,411.9
XS GIS Cut Line= 3
      1854444.07       914449.03      1854447.90       914294.96
      1854415.72       914127.64
BEGIN DESCRIPTION:
Grays Branch Tributary 2 13.0
END DESCRIPTION:
#Sta/Elev= 30
  4857.6  680.64  4864.4  679.94  4878.8  677.26  4891.7  675.78  4903.9  674.71
  4929.5  671.44  4951.5  667.88    4967  665.94  4982.3  664.38  4989.9  664.22
  4995.8  663.99  4997.2  663.19  4998.7  660.19  5001.3  660.19  5002.8  663.19
  5005.9  663.51  5011.7  663.65  5030.6  664.53  5062.9  664.86  5066.2  665.21
  5075.7  665.95  5083.6  666.79  5097.5  668.42  5103.1  669.31  5108.3   670.3
  5116.8   672.1  5124.3  673.44  5131.6  674.64  5145.5  677.38  5182.1  683.45
#Mann= 3 , 1 , 0
 4857.60    0.15       0  4997.2    0.05       0  5002.8    0.15       0
Bank Sta=4997.20,5002.80
Exp/Cntr=0.3,0.1

Type RM Length L Ch R = 1 ,6179.1,485.7,485.7,485.7
XS GIS Cut Line= 3
      1854880.33       914364.86      1854847.37       914215.06
      1854841.25       914053.76
BEGIN DESCRIPTION:
Grays Branch Tributary 2 12.0
END DESCRIPTION:
#Sta/Elev= 29
  4850.4     675  4860.7  673.46  4868.3  672.05  4873.6  670.85  4881.2  670.58
  4884.6  669.63  4894.5   665.5  4908.7  664.23  4919.3  662.96    4931  662.28
  4946.8  661.76  4960.4   661.5  4967.5  661.62  4997.2  659.98  4998.7  656.98
  5001.3  656.98  5002.8  659.98  5023.2   660.5  5045.6  661.26  5059.2  662.51
  5073.5  663.32    5080  663.79  5087.4  664.69  5097.2  666.04  5101.2  666.49
  5108.6  667.76  5125.2  670.24  5146.9  673.02  5165.2  675.06
#Mann= 3 , 1 , 0
 4850.40    0.15       0  4997.2    0.05       0  5002.8    0.15       0
Bank Sta=4997.20,5002.80
Exp/Cntr=0.3,0.1

Type RM Length L Ch R = 1 ,5693.4,411,411,411
XS GIS Cut Line= 3
      1855325.76       914154.82      1855249.91       913953.87
      1855156.82       913849.15
BEGIN DESCRIPTION:
Grays Branch Tributary 2 11.0
END DESCRIPTION:
#Sta/Elev= 30
  4790.4   672.4  4803.8  671.08  4807.3   670.5  4815.3  669.69  4826.1  668.43
  4833.4  667.91  4844.5  666.19  4861.1  664.28  4874.7   662.9  4888.7  661.17
  4902.8   660.4    4926  659.66  4959.4   659.3  4978.5  659.41  4997.2  659.28
  4998.7  656.28  5001.3  656.28  5002.8  659.28    5009  659.59  5009.7  659.53
  5014.1  659.96  5036.6  659.73  5054.9  659.38  5065.6  659.53  5091.9  660.93
  5106.9  662.27  5112.4  662.89  5118.9  665.38  5133.5  670.26  5145.3  673.66
#Mann= 3 , 1 , 0
 4790.40    0.15       0  4997.2    0.05       0  5002.8    0.15       0
Bank Sta=4997.20,5002.80
Exp/Cntr=0.3,0.1

Type RM Length L Ch R = 1 ,5282.4,736.7,736.7,736.7
XS GIS Cut Line= 3
      1855602.69       914118.31      1855652.45       913870.90
      1855651.22       913774.90
BEGIN DESCRIPTION:
Grays Branch Tributary 2 10.0
END DESCRIPTION:
#Sta/Elev= 23
  4763.6  664.23  4797.8  662.21  4809.1  661.69    4817  661.47  4831.7  660.87
  4861.5  658.98  4885.5  658.35  4899.8  657.87  4927.1  657.34  4934.6   657.4
  4946.8  657.35  4954.8  657.47  4982.7   657.2  4996.7  657.25  4997.2  657.18
  4998.7  654.18  5001.3  654.18  5002.8  657.18  5057.9  657.31  5068.6  657.52
  5083.3  659.04  5097.5  662.98    5112  665.57
#Mann= 3 , 1 , 0
 4763.60    0.15       0  4997.2    0.05       0  5002.8    0.15       0
Bank Sta=4997.20,5002.80
Exp/Cntr=0.3,0.1

Type RM Length L Ch R = 1 ,4545.7,253.4,253.4,253.4
XS GIS Cut Line= 3
      1856245.23       914150.88      1856309.04       913883.23
      1856265.21       913809.81
BEGIN DESCRIPTION:
Grays Branch Tributary 2 9.0
END DESCRIPTION:
#Sta/Elev= 30
  4724.8  661.95    4736  660.17  4740.3  659.63  4765.3  657.52  4797.4  655.93
  4803.9  655.36  4825.1  654.34  4850.9  654.34  4866.7  654.15  4875.7  653.63
  4905.2  653.88  4919.9  653.63  4939.8  652.74  4952.6  652.82  4959.2  653.15
    4983  653.64  4994.6  653.44  4997.2  651.99  4998.7  648.99  5001.3  648.99
  5002.8  651.99    5003  652.31    5010  653.54  5033.8  655.49  5038.5  656.04
  5050.4  657.02  5064.6  659.07    5077  661.53  5081.6  662.28  5085.5  663.56
#Mann= 3 , 1 , 0
 4724.80    0.15       0  4997.2    0.05       0  5002.8    0.15       0
Bank Sta=4997.20,5002.80
Exp/Cntr=0.3,0.1

Type RM Length L Ch R = 1 ,4292.3,502.3,502.3,502.3
XS GIS Cut Line= 3
      1856355.38       914235.49      1856534.36       913987.67
      1856634.89       913874.99
BEGIN DESCRIPTION:
Grays Branch Tributary 2 8.0
END DESCRIPTION:
#Sta/Elev= 30
  4692.4  666.06  4720.4  661.99  4745.6  659.46  4756.5  658.57  4769.3  658.13
  4794.2  656.46  4806.2  655.97  4819.6  654.95  4832.3  654.28  4842.1  653.59
  4855.5  652.96  4868.1  652.62  4889.6  652.81  4898.1  652.39  4913.9   652.5
  4936.5  652.89  4956.6  652.85  4973.5  652.64  4997.2  651.34  4998.7  648.34
  5001.3  648.34  5002.8  651.34  5063.2  652.04  5097.1  655.49  5110.1  656.98
  5113.3  657.55  5120.9  660.19  5129.6  661.45  5136.5  662.09  5149.1   667.2
#Mann= 3 , 1 , 0
 4692.40    0.15       0  4997.2    0.04       0  5002.8    0.15       0
Bank Sta=4997.20,5002.80
Exp/Cntr=0.3,0.1

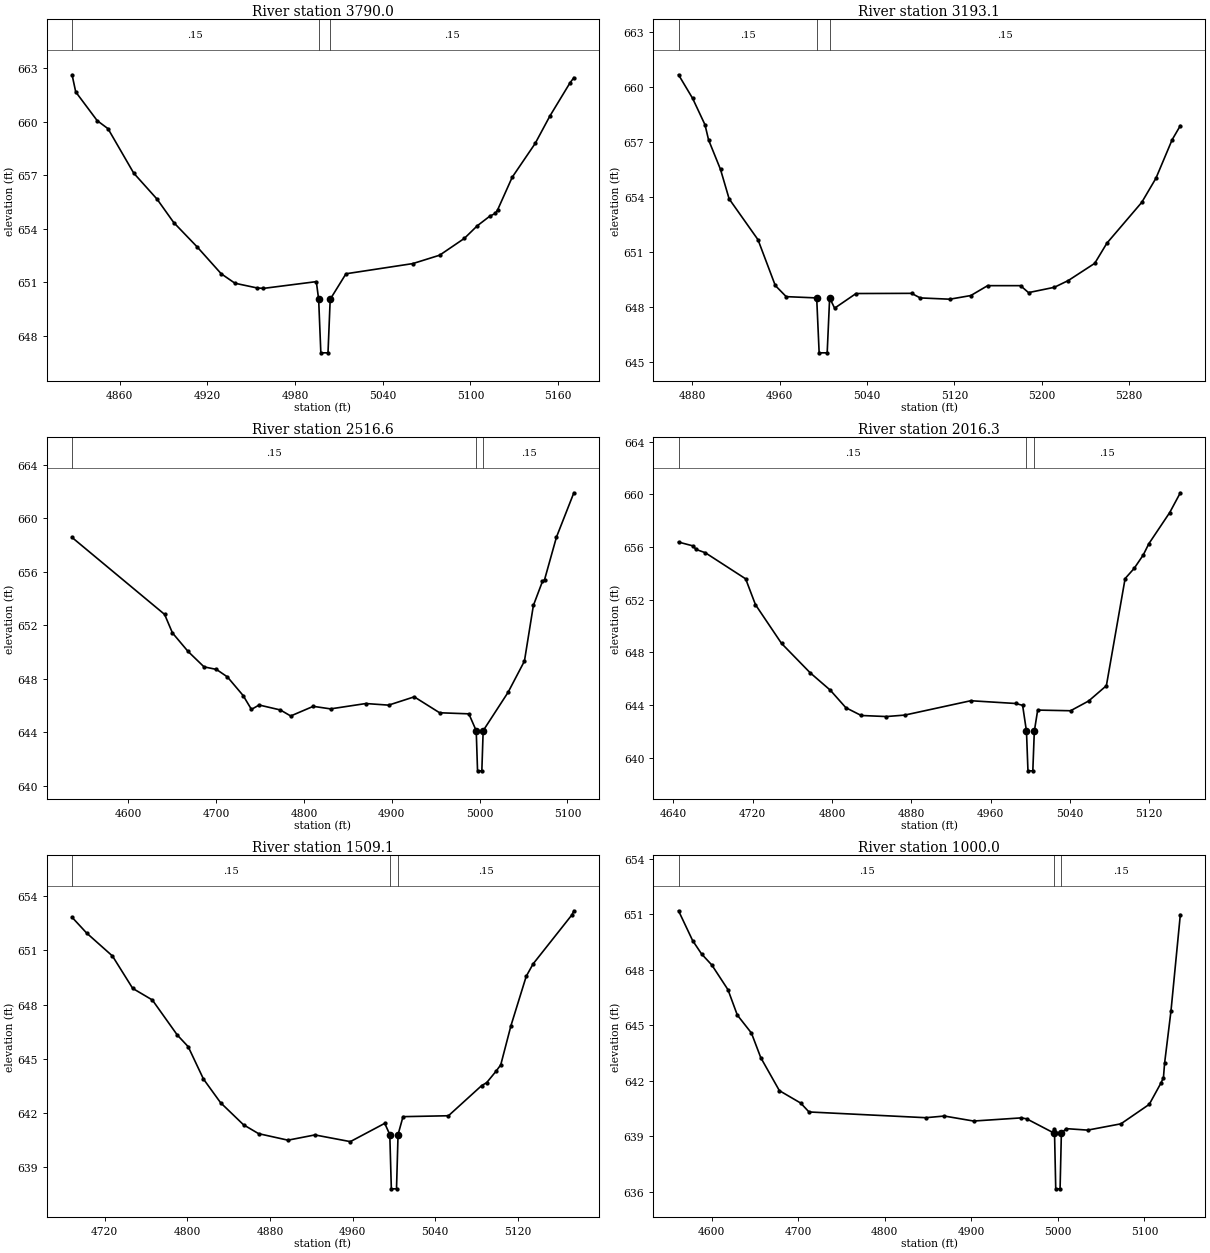
Type RM Length L Ch R = 1 ,3790.0,596.9,596.9,596.9
XS GIS Cut Line= 3
      1856615.07       914527.05      1856767.89       914414.80
      1856818.62       914269.51
BEGIN DESCRIPTION:
Grays Branch Tributary 2 7.0
END DESCRIPTION:
#Sta/Elev= 30
  4827.3  662.62  4829.8  661.66  4844.5  660.05  4851.9   659.6  4869.5  657.11
  4885.5  655.65  4896.9  654.34    4913  652.97  4929.4  651.47  4938.8  650.94
  4953.7  650.68  4958.2  650.65  4994.5  651.03  4996.1  650.04  4997.6  647.04
  5002.5  647.04    5004  650.04  5014.8  651.47  5060.5  652.04  5078.9  652.51
  5095.8  653.45  5104.7  654.16  5113.3   654.7    5117  654.85  5118.6  655.05
  5128.6  656.88  5144.3  658.77  5154.4  660.31  5168.1  662.16  5170.8  662.46
#Mann= 3 , 1 , 0
 4827.30    0.15       0  4996.1    0.04       0    5004    0.15       0
Bank Sta=4996.10,5004.00
Exp/Cntr=0.3,0.1

Type RM Length L Ch R = 1 ,3193.1,676.5,676.5,676.5
XS GIS Cut Line= 3
      1857210.20       914679.27      1857290.28       914586.88
      1857280.23       914250.13
BEGIN DESCRIPTION:
Grays Branch Tributary 2 6.0
END DESCRIPTION:
#Sta/Elev= 30
  4867.6  660.69  4880.5   659.4  4891.8  657.96  4895.1  657.13    4906  655.52
  4913.9  653.91  4940.3  651.68  4956.1  649.18  4966.1  648.57    4994   648.5
 4996.25   645.5  5003.6   645.5 5005.85   648.5  5010.4  647.94    5030  648.74
  5080.8  648.75  5088.7   648.5  5115.8  648.43    5135  648.63  5150.4  649.17
  5180.5  649.17  5187.8  648.79  5211.4  649.08  5224.2  649.45  5248.4  650.39
  5259.5  651.49  5291.4  653.72  5304.4  655.04  5319.2  657.14  5326.7  657.91
#Mann= 3 , 1 , 0
 4867.60    0.15       0    4994    0.04       0 5005.85    0.15       0
Bank Sta=4994.00,5005.85
Exp/Cntr=0.3,0.1

Type RM Length L Ch R = 1 ,2516.6,500.3,500.3,500.3
XS GIS Cut Line= 3
      1857883.08       914743.62      1857818.02       914294.25
      1857861.52       914185.12
BEGIN DESCRIPTION:
Grays Branch Tributary 2 5.0
END DESCRIPTION:
#Sta/Elev= 30
  4535.8  658.57  4641.2  652.82  4650.1  651.44  4667.8  650.06  4686.1   648.9
  4700.2  648.71  4712.7  648.15  4730.6  646.76  4740.1  645.72  4748.8  646.05
    4773  645.68  4784.8  645.23  4810.5  645.95  4830.2  645.76  4870.4  646.16
  4896.3  646.04  4925.5  646.66  4954.4  645.47  4987.7  645.39  4996.1  644.13
  4997.6  641.13  5002.5  641.13    5004  644.13  5032.4     647    5051  649.33
  5061.2  653.49  5071.5  655.28  5073.9  655.41  5087.5   658.6  5107.3  661.91
#Mann= 3 , 1 , 0
 4535.80    0.15       0  4996.1    0.04       0    5004    0.15       0
Bank Sta=4996.10,5004.00
Exp/Cntr=0.3,0.1

Type RM Length L Ch R = 1 ,2016.3,507.2,507.2,507.2
XS GIS Cut Line= 3
      1858190.44       914732.04      1858306.45       914396.61
      1858234.35       914263.59
BEGIN DESCRIPTION:
Grays Branch Tributary 2 4.0
END DESCRIPTION:
#Sta/Elev= 30
  4645.1  656.37  4660.1  656.07  4662.5  655.82  4672.1  655.56  4712.8  653.58
  4722.7  651.62    4749  648.68  4777.9  646.45  4798.2  645.13  4813.9   643.8
  4829.4  643.21  4854.7  643.13  4873.3  643.24  4939.9  644.33  4985.3  644.12
  4992.2  643.98  4996.1  642.01  4997.6  639.01  5002.5  639.01    5004  642.01
  5007.4  643.62  5040.6  643.57  5058.8  644.31  5076.7  645.47  5095.6   653.6
  5104.7  654.37  5113.9  655.39  5119.5  656.24  5140.6  658.61  5151.3  660.11
#Mann= 3 , 1 , 0
 4645.10    0.15       0  4996.1    0.04       0    5004    0.15       0
Bank Sta=4996.10,5004.00
Exp/Cntr=0.3,0.1

Type RM Length L Ch R = 1 ,1509.1,509.1,509.1,509.1
XS GIS Cut Line= 3
      1858553.77       914923.74      1858730.21       914641.09
      1858857.28       914556.60
BEGIN DESCRIPTION:
Grays Branch Tributary 2 3.0
END DESCRIPTION:
#Sta/Elev= 30
  4688.4  652.83  4702.5  651.96  4727.5  650.69  4747.1   648.9  4766.1  648.26
  4790.3  646.32  4800.8  645.68  4815.6  643.89  4832.2  642.58  4854.4  641.36
    4869  640.87  4897.4  640.51  4923.5   640.8  4957.8  640.43  4991.1  641.44
    4996  640.82  4997.5  637.82  5002.5  637.82    5004  640.82  5008.8  641.81
  5052.8  641.86    5085  643.53  5089.8  643.69  5098.7  644.31  5103.4  644.67
  5113.3  646.84  5128.1  649.57  5134.7  650.25  5172.4  652.97  5174.2  653.19
#Mann= 3 , 1 , 0
 4688.40    0.15       0    4996    0.04       0    5004    0.15       0
Bank Sta=4996.00,5004.00
Exp/Cntr=0.3,0.1

Type RM Length L Ch R = 1 ,1000.0,552.95,552.95,552.95
XS GIS Cut Line= 3
      1858928.46       915240.33      1859168.28       914873.59
      1859184.26       914733.09
BEGIN DESCRIPTION:
Grays Branch Tributary 2 2.0
END DESCRIPTION:
#Sta/Elev= 30
  4561.8  651.18  4578.1  649.57  4588.4  648.85  4600.3  648.25  4618.9  646.92
  4629.7  645.55    4646  644.58  4656.8  643.25  4678.3  641.47  4702.9   640.8
  4712.5  640.32  4847.4  640.01  4868.8   640.1  4902.6  639.83  4957.6     640
  4963.9  639.95  4995.9  639.17    4996  639.39  4997.5  636.17  5002.5  636.17
    5004  639.17  5009.5  639.42  5034.4  639.34  5072.8  639.68  5105.5  640.73
  5118.9  641.87  5121.9  642.17  5123.2  642.94  5130.6  645.77  5141.4  650.97
#Mann= 3 , 1 , 0
 4561.80    0.15       0  4995.9    0.04       0    5004    0.15       0
Bank Sta=4995.90,5004.00
Exp/Cntr=0.5,0.3