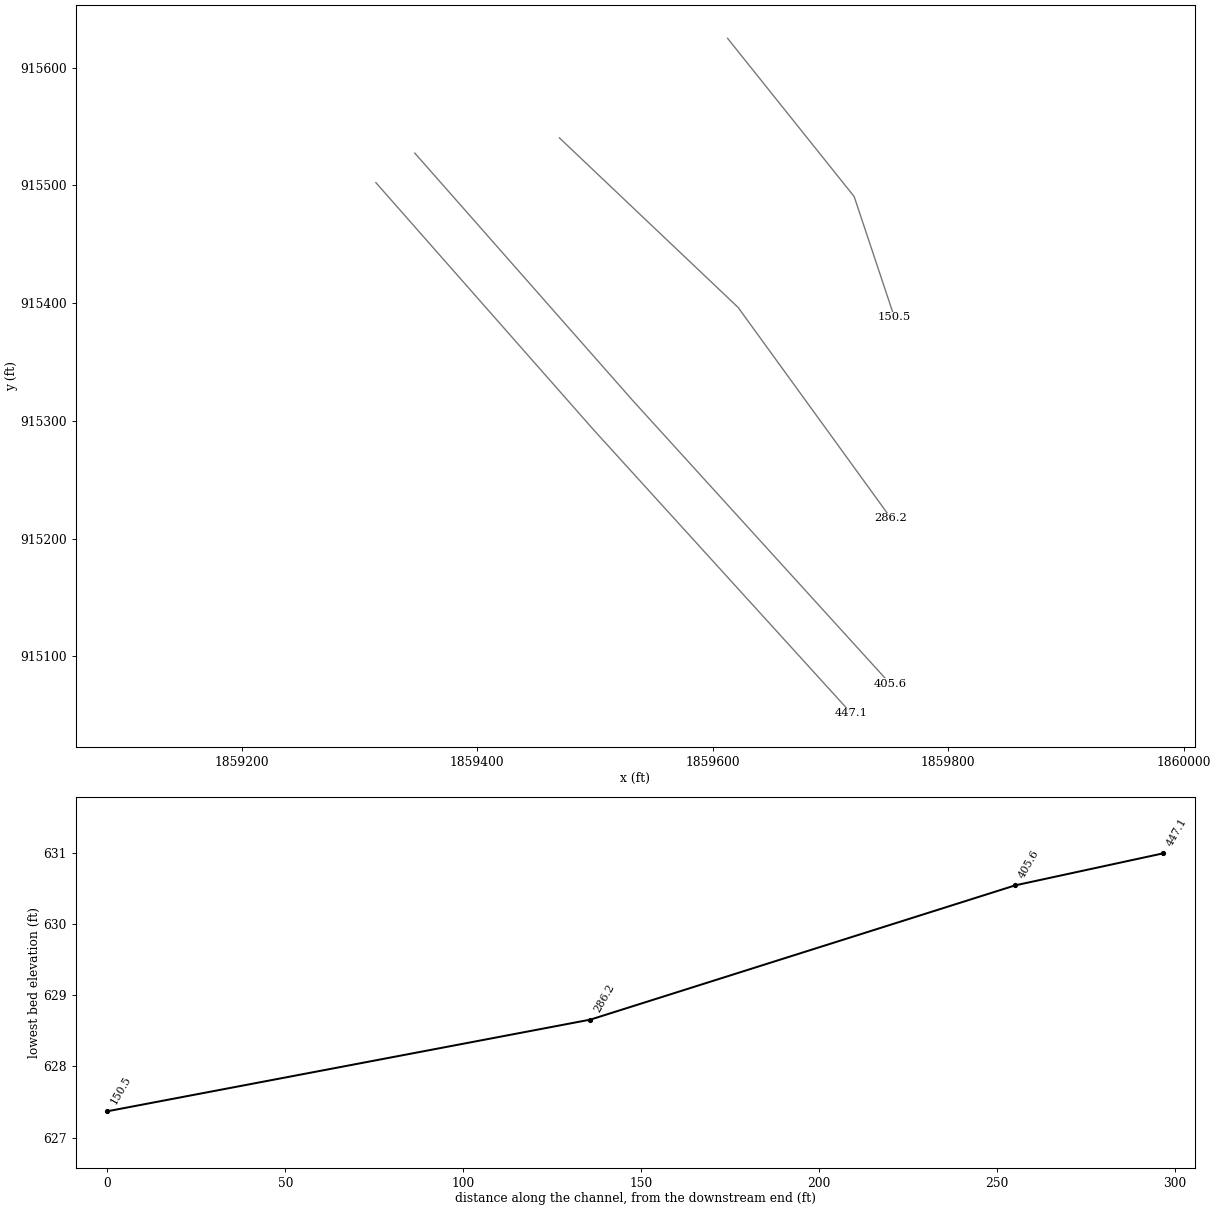
HEC-RAS study GRAYS BRANCH TRIBUTARY 2.PRJ: Grays Branch Tributary 2

--- GRAYS BRANCH TRIBUTARY 2.g01 (geometry) --- (continued)

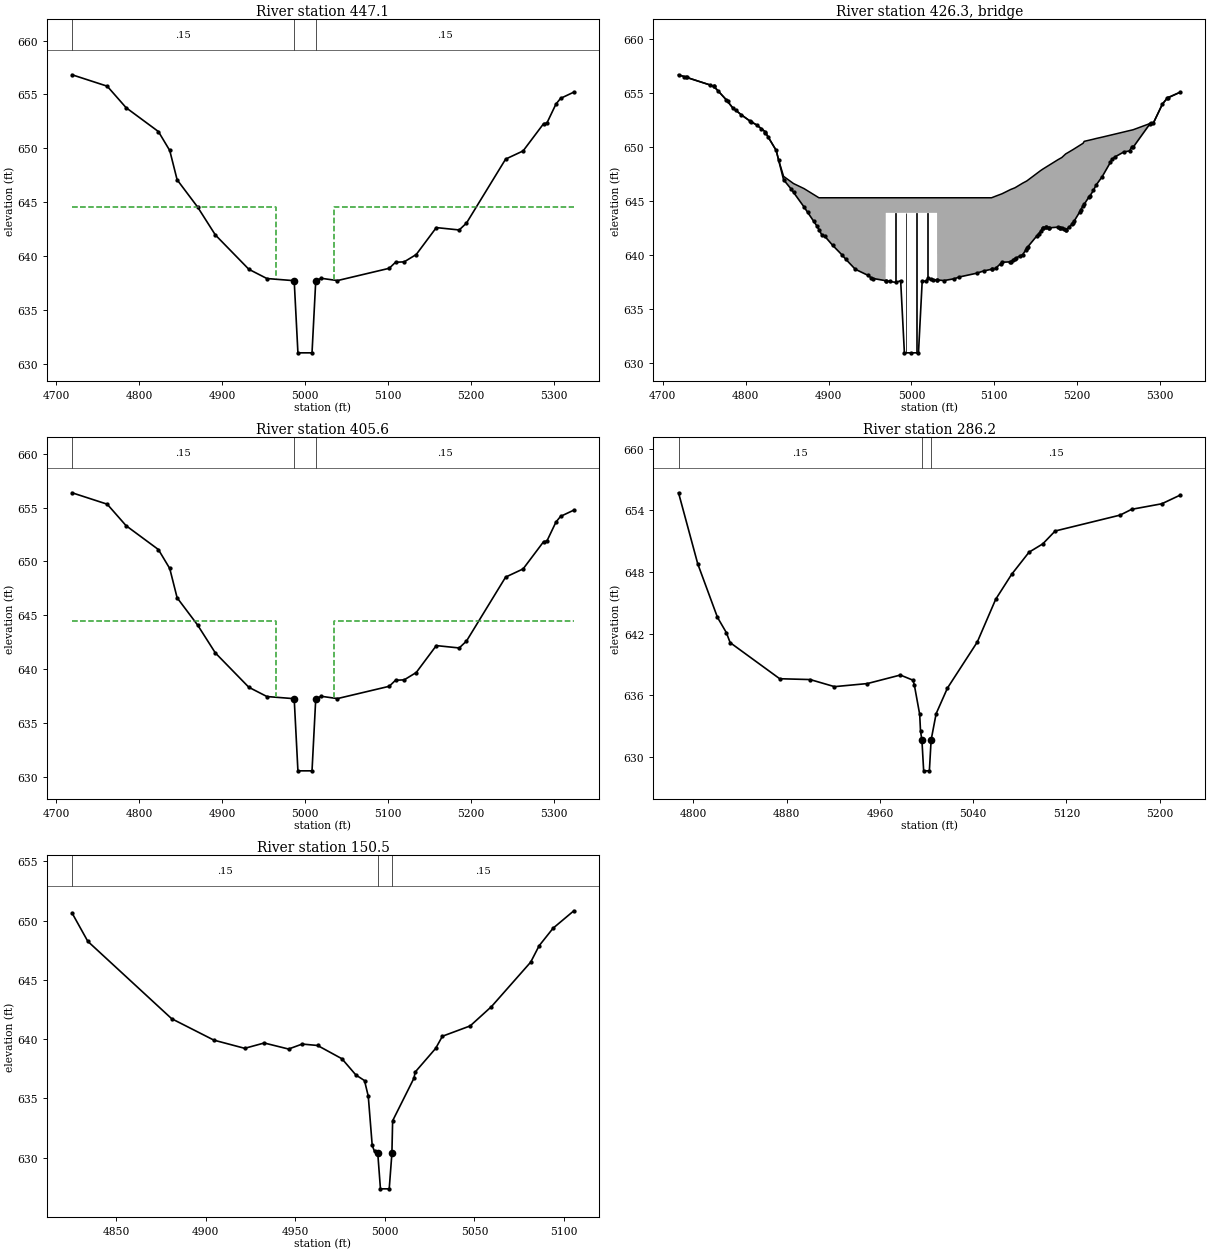
Type RM Length L Ch R = 1 ,447.1,41.5,41.5,41.5
XS GIS Cut Line= 3
      1859314.01       915502.25      1859498.93       915292.31
      1859717.82       915051.51
BEGIN DESCRIPTION:
Upstream Section of Bridge/Culvert/Weir
END DESCRIPTION:
#Sta/Elev= 30
  4719.1  656.82  4761.5  655.76  4784.3  653.76  4823.2  651.55  4836.9  649.79
  4845.8  647.07  4870.5  644.54  4891.9  641.95  4932.3  638.76  4954.1   637.9
    4987   637.7  4991.5     631  5008.5     631    5013   637.7  5019.8  637.92
  5039.2  637.71  5101.6  638.85  5109.2  639.41  5119.7  639.45  5134.2  640.13
  5158.4  642.63    5186  642.41  5194.8  643.05    5242  648.99  5263.1  649.75
  5287.9  652.29  5291.8  652.34  5302.7   654.1  5308.3  654.63  5324.3  655.21
#Mann= 3 , 1 , 0
 4719.10    0.15       0    4987    0.04       0    5013    0.15       0
#XS Ineff= 2 , 0
       0    4965   644.5    5035       0   644.5
Bank Sta=4987.00,5013.00
Exp/Cntr=0.5,0.3

Type RM Length L Ch R = 3 ,426.3,,,
BEGIN DESCRIPTION:
Underwood Road TOR
Structure ID: NCF-0227
Approximate Survey Structure
END DESCRIPTION:
Bridge Culvert--1,0,-1,-1, 0
Deck Dist Width WeirC Skew NumUp NumDn MinLoCord MaxHiCord MaxSubmerge Is_Ogee
10,21.5,2.6,, 55, 55,,,0.95,0,1,1,,
  4719.1  4761.5  4776.6  4784.3  4794.8  4805.8  4813.3  4823.2  4836.9  4839.8
  4845.8  4857.8  4870.5  4886.3  4888.4  4891.9  4895.3  4904.9  4932.3  4954.1
 4968.91    4969 5030.89    5031  5039.2  5051.7  5096.6  5101.6  5109.2  5119.7
  5124.9  5134.2  5139.1  5155.7  5158.4  5176.6  5181.4    5186  5190.2  5194.8
    5207  5208.4  5219.5  5222.5    5230    5242  5256.1  5263.1    5266  5267.5
  5287.9  5291.8  5302.7  5308.3  5324.3
  656.72  655.67  654.41  653.67  653.01   652.4  652.07  651.46   649.7  648.81
  647.29  646.62  646.15   645.4   645.3   645.3   645.3   645.3   645.3   645.3
   645.3   645.3   645.3   645.3   645.3   645.3   645.3  645.45  645.67  646.07
  646.23  646.66  646.86  647.82  647.96  648.83  649.04  649.37  649.56  649.77
  650.36  650.54  650.74   650.8  650.93  651.15  651.41  651.54  651.59  651.62
   652.2  652.24     654  654.53  655.11
  656.72  655.66   654.4  653.66     653  652.39  652.06  651.45  649.69   648.8
  646.97   645.8  644.44  642.64  642.34  641.85  641.74  640.89  638.66   637.8
   637.6   643.9   643.9  637.67  637.61  637.78  638.66  638.75  639.31  639.35
  639.65  640.03  640.63  642.17  642.53  642.57  642.47  642.31  642.57  642.95
  644.53   644.7  645.98  646.45  647.25  648.89  649.55  649.65  650.06     650
  652.19  652.24     654  654.53  655.11
  4719.1  4761.5  4776.6  4784.3  4794.8  4805.8  4813.3  4823.2  4836.9  4839.8
  4845.8  4857.8  4870.5  4886.3  4888.4  4891.9  4895.3  4904.9  4932.3  4954.1
 4968.91    4969 5030.89    5031  5039.2  5051.7  5096.6  5101.6  5109.2  5119.7
  5124.9  5134.2  5139.1  5155.7  5158.4  5176.6  5181.4    5186  5190.2  5194.8
    5207  5208.4  5219.5  5222.5    5230    5242  5256.1  5263.1    5266  5267.5
  5287.9  5291.8  5302.7  5308.3  5324.3
  656.72  655.67  654.41  653.67  653.01   652.4  652.07  651.46   649.7  648.81
  647.29  646.62  646.15   645.4   645.3   645.3   645.3   645.3   645.3   645.3
   645.3   645.3   645.3   645.3   645.3   645.3   645.3  645.45  645.67  646.07
  646.23  646.66  646.86  647.82  647.96  648.83  649.04  649.37  649.56  649.77
  650.36  650.54  650.74   650.8  650.93  651.15  651.41  651.54  651.59  651.62
   652.2  652.24     654  654.53  655.11
  656.47  655.41  654.15  653.41  652.75  652.14  651.81   651.2  649.44  648.55
  646.72  645.55  644.19  642.39  642.09   641.6  641.49  640.64  638.41  637.55
  637.35  643.65  643.65  637.42  637.36  637.53  638.41   638.5  639.06   639.1
   639.4  639.78  640.38  641.92  642.28  642.32  642.22  642.06  642.32   642.7
  644.28  644.45  645.73   646.2     647  648.64   649.3   649.4  649.81  649.75
  651.94  651.99  653.75  654.28  654.86
Pier Skew, UpSta & Num, DnSta & Num=,4980.5, 2 ,4980.5, 2 , 0 , 0 , 0 ,,
       1       1
  636.44   644.9
       1       1
  636.19  644.65
Pier Skew, UpSta & Num, DnSta & Num=,4993.5, 2 ,4993.5, 2 , 0 , 0 , 0 ,,
       1       1
   629.9   644.9
       1       1
  629.65  644.65
Pier Skew, UpSta & Num, DnSta & Num=,5006.5, 2 ,5006.5, 2 , 0 , 0 , 0 ,,
       1       1
   629.9   644.9
       1       1
  629.65  644.65
Pier Skew, UpSta & Num, DnSta & Num=,5019.5, 2 ,5019.5, 2 , 0 , 0 , 0 ,,
       1       1
  636.72   644.9
       1       1
  636.47  644.65
Abutment Skew #Up #Dn=, 2 , 2
 4968.80 4974.00
  643.90  637.53
 4968.80 4974.00
  643.65  637.28
Abutment Skew #Up #Dn=, 2 , 2
 5026.00 5031.09
  637.71  643.90
 5026.00 5031.09
  637.46  643.65
BR Coef= 1 , 1 , 0 ,1.25, 0 ,,,0.8,0,2,0,
Wspro=,,,, 1 ,,,, 0 ,,,, 0 ,,,,-1 ,-1 ,-1 , 0 , 0 , 0 , 0 , 0
BC Design=,, 0 ,, 0 ,,,,,,
BR U #Sta/Elev= 117
  4719.1  656.72  4726.2  656.54  4728.2  656.49  4729.1  656.47  4757.1  655.77
  4761.5  655.66  4761.6  655.65  4766.9  655.21  4776.6   654.4  4778.3  654.24
  4784.3  653.66  4788.1  653.42  4794.8     653  4805.8  652.39  4806.9  652.34
  4813.3  652.06  4819.1   651.7  4823.2  651.45  4823.9  651.36  4827.4  650.91
  4836.9  649.69  4839.8   648.8  4845.8  646.97  4854.5  646.15  4857.8   645.8
  4870.5  644.44  4874.7  643.96  4881.9  643.14  4886.3  642.64  4888.4  642.34
  4891.9  641.85  4895.3  641.74  4904.9  640.89  4915.8  640.03  4920.8  639.59
  4932.3  638.66  4947.2  638.11  4951.1  637.89  4954.1   637.8 4968.91   637.6
    4969   637.6    4974  637.53  4981.1  637.44    4987   637.6  4991.5   630.9
  4999.9   630.9  5008.5   630.9    5013   637.6  5017.4  637.53  5019.8  637.82
  5023.3  637.73    5026  637.71 5030.89  637.67    5031  637.67  5039.2  637.61
  5051.7  637.78  5057.6  637.94  5078.5  638.29  5087.1   638.5  5096.6  638.66
    5097  638.67  5101.6  638.75  5107.5  639.18  5109.2  639.31  5119.3  639.35
  5119.7  639.35    5123  639.54  5124.9  639.65  5126.6  639.72  5130.7  639.89
  5134.2  640.03  5137.9  640.44  5139.1  640.63  5140.4  640.75  5151.5  641.78
  5153.3  641.95  5155.7  642.17  5158.4  642.53  5158.9  642.53  5162.1  642.56
  5162.4  642.56  5165.9  642.52  5166.4  642.51  5176.6  642.57  5179.5  642.53
  5179.6  642.53  5181.4  642.47  5184.2  642.37    5186  642.31  5186.7  642.35
  5190.2  642.57    5194  642.88  5194.8  642.95    5196   643.1  5202.8  643.96
  5204.2   644.2    5207  644.53  5208.4   644.7    5214  645.36  5215.2  645.46
  5219.5  645.98  5222.5  646.45    5230  647.25  5239.9  648.58    5242  648.89
  5245.4  649.09  5256.1  649.55  5263.1  649.65    5266  650.06  5267.5     650
  5287.9  652.19  5288.6   652.2  5291.8  652.24  5302.7     654  5308.3  654.53
  5309.5  654.61  5324.3  655.11
BR U #Mann= 3
 4719.10    0.15    4987    0.04    5013    0.15
BR U Banks=4987.00,5013.00
BR D #Sta/Elev= 117
  4719.1  656.47  4726.2  656.29  4728.2  656.24  4729.1  656.22  4757.1  655.52
  4761.5  655.41  4761.6   655.4  4766.9  654.96  4776.6  654.15  4778.3  653.99
  4784.3  653.41  4788.1  653.17  4794.8  652.75  4805.8  652.14  4806.9  652.09
  4813.3  651.81  4819.1  651.45  4823.2   651.2  4823.9  651.11  4827.4  650.66
  4836.9  649.44  4839.8  648.55  4845.8  646.72  4854.5   645.9  4857.8  645.55
  4870.5  644.19  4874.7  643.71  4881.9  642.89  4886.3  642.39  4888.4  642.09
  4891.9   641.6  4895.3  641.49  4904.9  640.64  4915.8  639.78  4920.8  639.34
  4932.3  638.41  4947.2  637.86  4951.1  637.64  4954.1  637.55 4968.91  637.35
    4969  637.35    4974  637.28  4981.1  637.19    4987  637.35  4991.5  630.65
  4999.9  630.65  5008.5  630.65    5013  637.35  5017.4  637.28  5019.8  637.57
  5023.3  637.48    5026  637.46 5030.89  637.42    5031  637.42  5039.2  637.36
  5051.7  637.53  5057.6  637.69  5078.5  638.04  5087.1  638.25  5096.6  638.41
    5097  638.42  5101.6   638.5  5107.5  638.93  5109.2  639.06  5119.3   639.1
  5119.7   639.1    5123  639.29  5124.9   639.4  5126.6  639.47  5130.7  639.64
  5134.2  639.78  5137.9  640.19  5139.1  640.38  5140.4   640.5  5151.5  641.53
  5153.3   641.7  5155.7  641.92  5158.4  642.28  5158.9  642.28  5162.1  642.31
  5162.4  642.31  5165.9  642.27  5166.4  642.26  5176.6  642.32  5179.5  642.28
  5179.6  642.28  5181.4  642.22  5184.2  642.12    5186  642.06  5186.7   642.1
  5190.2  642.32    5194  642.63  5194.8   642.7    5196  642.85  5202.8  643.71
  5204.2  643.95    5207  644.28  5208.4  644.45    5214  645.11  5215.2  645.21
  5219.5  645.73  5222.5   646.2    5230     647  5239.9  648.33    5242  648.64
  5245.4  648.84  5256.1   649.3  5263.1   649.4    5266  649.81  5267.5  649.75
  5287.9  651.94  5288.6  651.95  5291.8  651.99  5302.7  653.75  5308.3  654.28
  5309.5  654.36  5324.3  654.86
BR D #Mann= 3
 4719.10    0.15    4987    0.04    5013    0.15
BR D Banks=4987.00,5013.00

Type RM Length L Ch R = 1 ,405.6,119.35,119.35,119.35
XS GIS Cut Line= 3
      1859347.07       915527.33      1859531.99       915317.39
      1859750.88       915076.59
BEGIN DESCRIPTION:
Downstream Section of Bridge/Culvert/Weir
END DESCRIPTION:
#Sta/Elev= 30
  4719.1  656.37  4761.5  655.31  4784.3  653.31  4823.2   651.1  4836.9  649.34
  4845.8  646.62  4870.5  644.09  4891.9   641.5  4932.3  638.31  4954.1  637.45
    4987  637.25  4991.5  630.55  5008.5  630.55    5013  637.25  5019.8  637.47
  5039.2  637.26  5101.6   638.4  5109.2  638.96  5119.7     639  5134.2  639.68
  5158.4  642.18    5186  641.96  5194.8   642.6    5242  648.54  5263.1   649.3
  5287.9  651.84  5291.8  651.89  5302.7  653.65  5308.3  654.18  5324.3  654.76
#Mann= 3 , 1 , 0
 4719.10    0.15       0    4987    0.04       0    5013    0.15       0
#XS Ineff= 2 , 0
       0    4965   644.5    5035       0   644.5
Bank Sta=4987.00,5013.00
Exp/Cntr=0.5,0.3

Type RM Length L Ch R = 1 ,286.2,135.7,135.7,135.7
XS GIS Cut Line= 3
      1859469.89       915540.26      1859621.63       915396.30
      1859751.59       915217.04
BEGIN DESCRIPTION:
Grays Branch Tributary 2 1.0
END DESCRIPTION:
#Sta/Elev= 30
  4787.2  655.71  4803.7  648.79  4820.6  643.59  4828.2  642.11  4831.5  641.13
    4874  637.62  4900.1  637.54    4921  636.85  4949.2  637.15  4977.5  637.98
  4988.3  637.48  4989.5  637.01  4994.1  634.15  4994.8  632.52    4996  631.66
  4997.5  628.66  5002.4  628.66  5003.9  631.66  5008.2  634.22  5017.9  636.71
  5043.5  641.19  5059.3  645.35    5073  647.78  5087.9  649.93  5099.7  650.74
  5110.3  651.99  5166.1  653.54  5175.9   654.1  5201.8  654.64  5217.7  655.49
#Mann= 3 , 1 , 0
 4787.20    0.15       0    4996   0.055       0  5003.9    0.15       0
Bank Sta=4996.00,5003.90
Exp/Cntr=0.3,0.1

Type RM Length L Ch R = 1 ,150.5,0,0,0
XS GIS Cut Line= 3
      1859612.69       915624.83      1859720.22       915490.42
      1859754.40       915387.89
BEGIN DESCRIPTION:
Grays Branch Tributary 2 0.5
END DESCRIPTION:
#Sta/Elev= 30
  4825.3  650.63  4834.1  648.24  4880.9  641.72  4904.5  639.91  4921.7  639.22
  4932.6  639.67  4946.2  639.16  4953.8  639.58  4962.4  639.46    4976  638.34
  4983.8  636.97  4988.6   636.5  4990.7  635.18  4992.9  631.03  4994.2  630.52
    4996  630.37  4997.5  627.37  5002.4  627.37  5003.9  630.37  5004.3  633.11
  5016.2   636.7  5016.9  637.22  5028.3  639.21  5032.1  640.24  5047.6  641.11
  5059.5  642.74  5081.4  646.49  5086.1  647.87  5093.9  649.35  5105.5  650.82
#Mann= 3 , 1 , 0
 4825.30    0.15       0    4996   0.055       0  5003.9    0.15       0
Bank Sta=4996.00,5003.90
Exp/Cntr=0.3,0.1

Chan Stop Cuts=-1