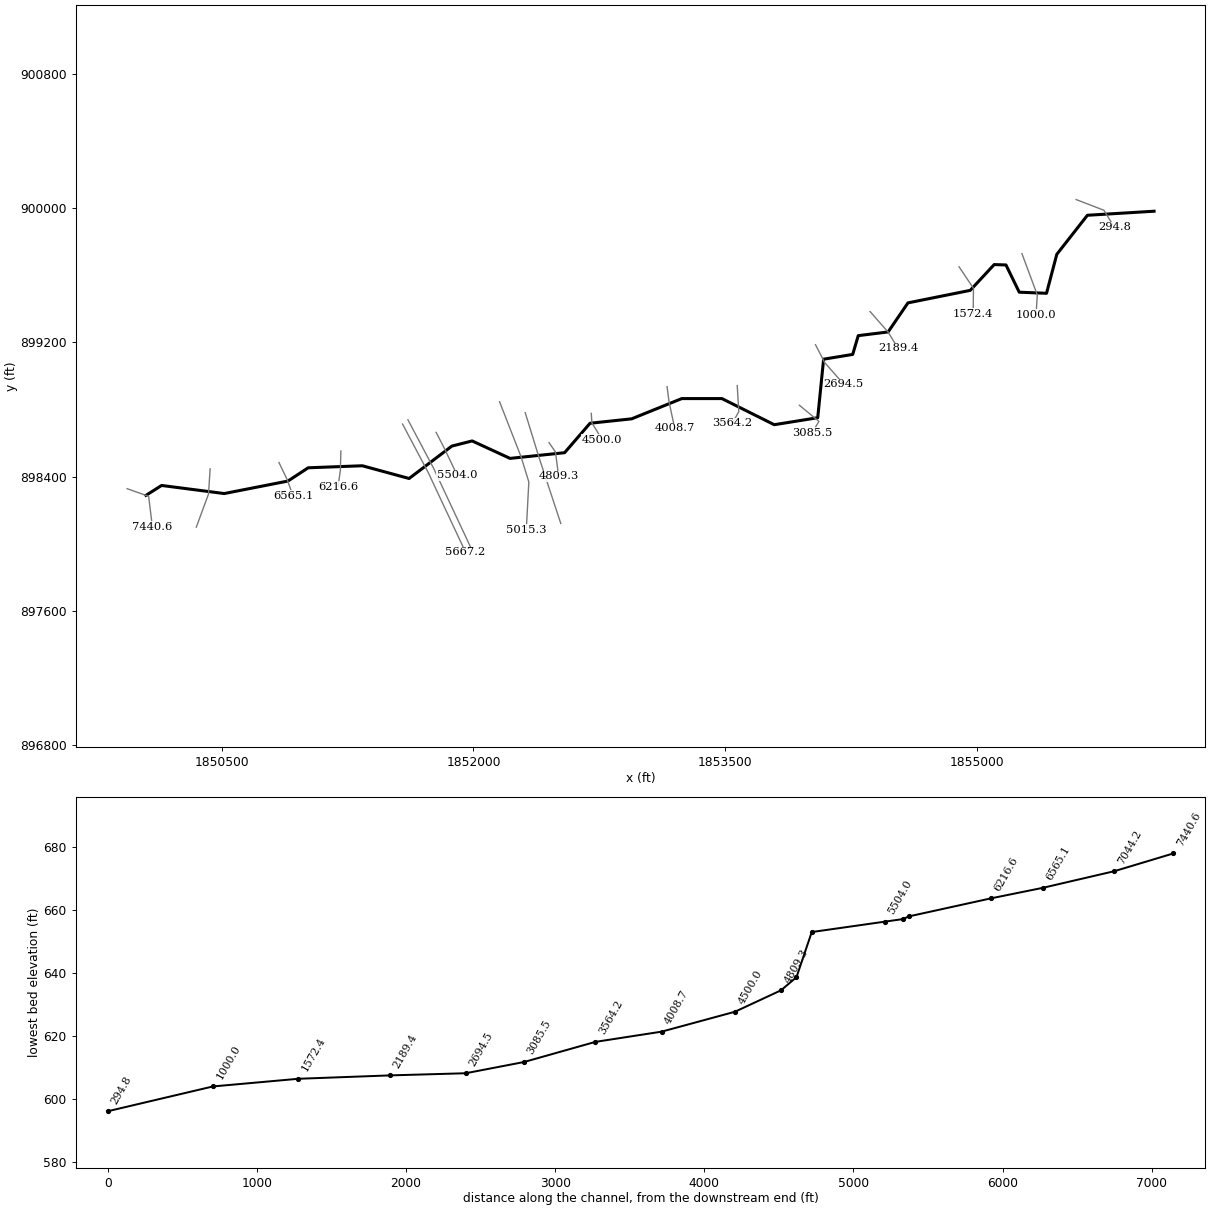
--- JONES CREEK.PRJ (project) ---

Proj Title=Jones Creek
Current Plan=p01
Default Exp/Contr=0.3,0.1
English Units
Geom File=g01
Flow File=f01
Plan File=p01
Y Axis Title=Elevation
X Axis Title(PF)=Main Channel Distance
X Axis Title(XS)=Station
BEGIN DESCRIPTION:
####(Watershed Name)####
JONES CREEK
HCFCD Unit X###-##-##
(Flood Hazard, Floodway) Model
10, 2, 1, 0.2% Event
Filename:  N:\NC_flood\60273\Approximates\Eng\Haw-Reedy\Eng\Jones Creek\Jones Creek.prj
Prepared by:  ________     Date: ________
Reviewed by:  ________     Date: ________
STATUS (Draft RAS, SVSQ, FINAL)
END DESCRIPTION:
DSS Export Rating Curves= 0
DSS Export Rating Curve Sorted= 0
DSS Export Volume Flow Curves= 0
DXF OffsetX= 0
DXF OffsetY= 0
DXF ScaleX= 1
DXF ScaleY= 10

--- JONES CREEK.p01 (plan) ---

Plan Title=100-Year-Single
Program Version=3.10
Short Identifier=Plan01
Geom File=g01
Flow File=f01
Subcritical Flow
K Sum by GR= 0
Std Step Tol= 0.01
Critical Tol= 0.01
Num of Std Step Trials= 20
Max Error Tol= 0.3
Flow Tol Ratio= 0.001
Split Flow NTrial= 30
Split Flow Tol= 0.02
Split Flow Ratio= 0.02
Log Output Level= 0
Friction Slope Method= 1
Unsteady Friction Slope Method= 2
Parabolic Critical Depth
Global Vel Dist= 0 , 0 , 0
Global Log Level= 0
CheckData=True
Encroach Param=-1 ,5,5, 2
Encroach River=Jones Creek
Encroach Reach=Reach - 1
Encroach Node=7440.6
       1 4987.47 5017.84
Encroach Node=7044.2
       1    4980 5013.37
Encroach Node=6565.1
       1 4975.74 5019.27
Encroach Node=6216.6
       1    4980 5009.63
Encroach Node=5667.2
       1  4982.5  5017.5
Encroach Node=5646.7
       1  4982.5  5017.5
Encroach Node=5626.2
       1  4982.5  5017.5
Encroach Node=5504.0
       1    4980 5011.74
Encroach Node=5015.3
       1    4900    5080
Encroach Node=5000.3
       4    4900    5080
Encroach Node=4913.0
       1 4976.57  5006.8
Encroach Node=4809.3
       1 4988.67 5014.78
Encroach Node=4500.0
       1 4987.34 5018.63
Encroach Node=4008.7
       1 4978.61 5027.21
Encroach Node=3564.2
       1 4953.75 5014.63
Encroach Node=3085.5
       1 4976.72 5012.39
Encroach Node=2694.5
       1 4981.74 5036.11
Encroach Node=2189.4
       1 4967.06 5033.07
Encroach Node=1572.4
       1 4946.48 5037.95
Encroach Node=1000.0
       1 4984.38  5036.1
Encroach Node=294.8
       1 4979.84 5014.94
Computation Interval=1HOUR
Output Interval=1HOUR
Run HTab= 0
Run UNet= 0
Run PostProcess= 0
UNET Theta= 1
UNET Theta Warmup= 1
UNET ZTol= 0.02
UNET ZSATol= 0.05
UNET MxIter= 20
UNET MaxInSteps= 1
UNET DtIC= 0
UNET DtMin= 0
UNET MaxCRTS= 20
UNET WFStab= 2
UNET SFStab= 1
UNET WFX= 1
UNET SFX= 1
UNET DSS MLevel= 4
UNET Convert EG Bridges=-1
UNET Use Existing IB Tables=-1
UNET Froude Reduction=False
UNET Froude Limit= 1
UNET Froude Power= 10
Instantaneous Interval=1HOUR
Write IC File= 0
Echo Input=False
Echo Output=False
Write Detailed= 0

--- JONES CREEK.f01 (steady flow) ---

Flow Title= 100-Year-Single
Program Version=3.10
Number of Profiles= 2
Profile Names=100-Year,AFW
River Rch & RM=Jones Creek,Reach - 1       ,7440.6
     575     575
River Rch & RM=Jones Creek,Reach - 1       ,5015.3
     880     880
Boundary for River Rch & Prof#=Jones Creek,Reach - 1       , 1
Up Type= 0
Dn Type= 3
Dn Slope=0.008
DSS Import GetInterval= 0
DSS Import GetPeak= 0
DSS Import FillOption= 0

--- JONES CREEK.g01 (geometry) ---

Geom Title=Geom 01 by CodeH2 for Windows

River Reach=Jones Creek,Reach - 1
Reach XY= 30
      1850050.07       898287.95         1850143       898347.06
      1850515.88       898298.81       1850895.5       898373.37
      1851016.13       898452.37      1851338.25       898464.44
         1851617       898388.56      1851871.75       898581.81
       1851992.5       898612.38      1852218.13       898508.31
         1852543       898542.31      1852694.38       898717.81
      1852942.25       898744.12      1853240.63       898864.81
      1853479.75       898864.81      1853791.37       898709.06
      1854050.25       898750.75      1854085.25       899099.56
      1854258.63       899128.06       1854291.5       899239.94
      1854469.25       899261.87      1854587.63       899435.19
       1854958.5       899509.81         1855101       899663.38
      1855171.25       899661.19      1855250.25       899498.81
      1855412.62       899492.25         1855474       899724.81
      1855656.12       899957.31      1856053.12        899981.5

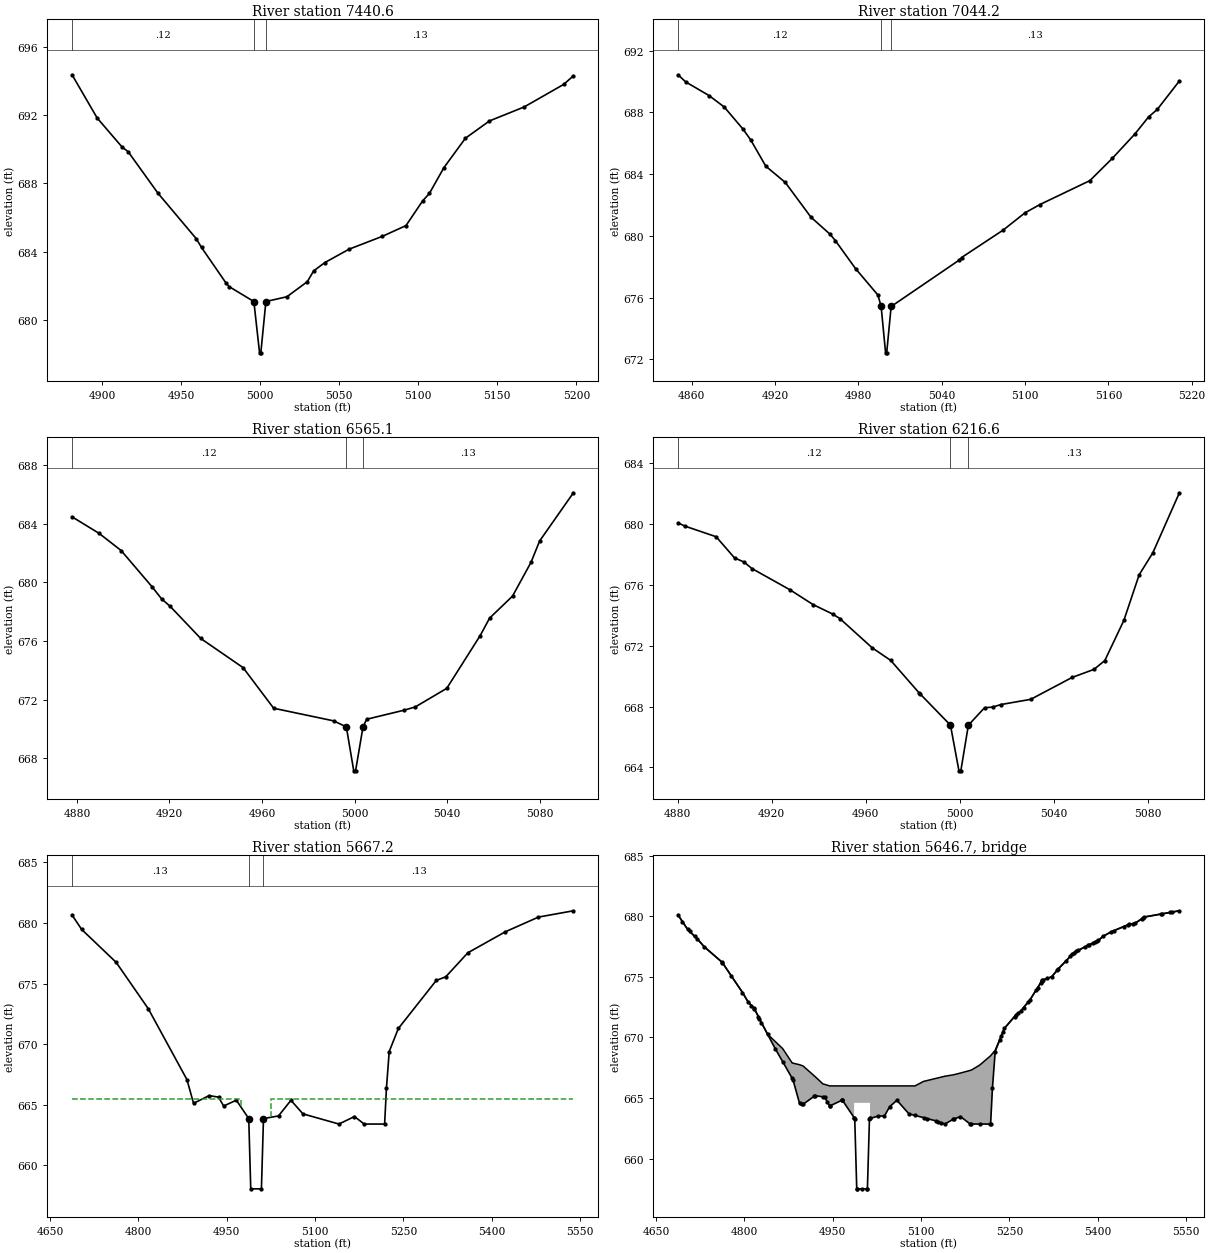
Type RM Length L Ch R = 1 ,7440.6,396.4,396.4,396.4
XS GIS Cut Line= 3
      1849937.92       898327.87      1850065.97       898282.24
      1850088.04       898102.42
BEGIN DESCRIPTION:
Jones Creek 15.0
END DESCRIPTION:
#Sta/Elev= 28
    4881  694.35  4896.9  691.82  4912.6  690.13  4916.5  689.85  4935.3  687.43
  4959.6  684.76  4962.9  684.25  4978.4  682.17  4980.4  681.96    4996  681.09
  4999.6  678.09  5000.4  678.09  5003.6  681.09  5016.9  681.37  5029.8  682.25
  5033.8  682.88  5040.9  683.37  5056.2  684.15  5077.2   684.9  5092.2  685.53
  5102.7  686.97    5107  687.41  5116.2  688.92  5129.8  690.64    5145  691.65
    5167  692.47    5192  693.79  5198.1  694.29
#Mann= 3 , 1 , 0
 4881.00    0.12       0    4996   0.045       0  5003.6    0.13       0
Bank Sta=4996.00,5003.60
Exp/Cntr=0.3,0.1

Type RM Length L Ch R = 1 ,7044.2,479.1,479.1,479.1
XS GIS Cut Line= 3
      1850432.10       898446.06      1850422.39       898295.55
      1850349.71       898098.45
BEGIN DESCRIPTION:
Jones Creek 14.0
END DESCRIPTION:
#Sta/Elev= 28
  4850.2  690.43  4855.7  689.97  4872.6  689.08  4883.5  688.34  4896.9  686.92
  4902.4  686.23  4913.4  684.51  4927.4  683.46  4945.9  681.21  4959.6  680.11
  4963.5  679.69    4978  677.88  4994.1  676.17  4996.4  675.43  4999.6  672.43
  5000.4  672.43  5003.6  675.43  5052.7  678.44  5054.3   678.6  5084.3  680.38
  5099.9  681.49  5110.7  682.03  5146.7  683.58  5162.8  685.02  5178.9  686.58
  5188.9   687.7  5195.2  688.19  5211.1  690.03
#Mann= 3 , 1 , 0
 4850.20    0.12       0  4996.4   0.045       0  5003.6    0.13       0
Bank Sta=4996.40,5003.60
Exp/Cntr=0.3,0.1

Type RM Length L Ch R = 1 ,6565.1,348.5,348.5,348.5
XS GIS Cut Line= 3
      1850842.09       898483.56      1850891.05       898381.70
      1850926.40       898284.33
BEGIN DESCRIPTION:
Jones Creek 13.0
END DESCRIPTION:
#Sta/Elev= 24
  4877.9  684.47  4889.6  683.34  4899.1  682.17  4912.5  679.69  4916.6  678.87
  4920.3  678.36  4933.5  676.17  4951.8  674.18    4965  671.41  4990.9  670.55
  4996.4  670.14  4999.6  667.14  5000.4  667.14  5003.6  670.14  5005.2  670.66
  5021.4  671.28  5026.2   671.5  5039.8  672.77  5054.2  676.36  5058.3  677.56
  5068.2  679.06  5076.2  681.37  5079.9  682.82  5094.5  686.11
#Mann= 3 , 1 , 0
 4877.90    0.12       0  4996.4   0.045       0  5003.6    0.13       0
Bank Sta=4996.40,5003.60
Exp/Cntr=0.3,0.1

Type RM Length L Ch R = 1 ,6216.6,549.4,549.4,549.4
XS GIS Cut Line= 3
      1851210.66       898552.68      1851207.69       898436.94
      1851193.93       898340.60
BEGIN DESCRIPTION:
Jones Creek 12.0
END DESCRIPTION:
#Sta/Elev= 29
  4880.2  680.08  4883.1  679.87  4896.4  679.17  4904.2  677.78  4908.2  677.51
  4911.6  677.08  4927.8  675.68  4937.6  674.71  4945.9  674.09    4949  673.79
  4962.7  671.87  4970.6  671.04  4982.8  668.88  4983.2  668.82    4996  666.78
  4999.6  663.78  5000.4  663.78  5003.6  666.78  5010.5  667.93  5013.9  667.97
  5017.5  668.14  5030.1  668.48  5047.7  669.92    5057  670.45  5061.6  671.03
  5069.7  673.67  5076.2  676.67    5082  678.11  5093.3  682.06
#Mann= 3 , 1 , 0
 4880.20    0.12       0    4996   0.045       0  5003.6    0.13       0
Bank Sta=4996.00,5003.60
Exp/Cntr=0.5,0.3

Type RM Length L Ch R = 1 ,5667.2,41,41,41
XS GIS Cut Line= 3
      1851577.87       898712.93      1851730.80       898424.06
      1851953.15       897949.52
BEGIN DESCRIPTION:
Upstream Section of Bridge/Culvert/Weir
END DESCRIPTION:
#Sta/Elev= 30
  4687.6  680.66  4703.9  679.47  4762.5  676.75  4816.9  672.93  4882.6  667.07
  4893.8  665.11  4920.4  665.75  4936.2  665.62  4944.9  664.89  4966.5  665.37
  4987.5  663.85  4990.9  658.05    5009  658.05  5012.5  663.85    5038  664.07
  5059.1  665.36  5079.5  664.24  5140.6   663.4  5166.9  664.02  5183.4   663.4
  5218.1   663.4  5221.2  666.37  5225.9  669.39  5241.4  671.29  5305.8  675.26
  5321.9  675.56  5359.3  677.54  5423.2  679.28  5479.2  680.49  5538.5  681.01
#Mann= 3 , 1 , 0
 4687.60    0.13       0  4987.5    0.04       0  5012.5    0.13       0
#XS Ineff= 2 , 0
       0    4975   665.5    5025       0   665.5
Bank Sta=4987.50,5012.50
Exp/Cntr=0.5,0.3

Type RM Length L Ch R = 3 ,5646.7,,,
BEGIN DESCRIPTION:
Altamahaw Race Track Rd TOR
Structure ID: NCF-0169
Approximate Survey Structure
END DESCRIPTION:
Bridge Culvert--1,0,-1,-1, 0
Deck Dist Width WeirC Skew NumUp NumDn MinLoCord MaxHiCord MaxSubmerge Is_Ogee
10,21,2.6,, 54, 54,,,0.95,0,1,1,,
  4687.6  4703.9  4720.6  4731.7  4762.5    4797  4806.4  4816.9  4839.7  4865.2
  4881.4  4882.6  4893.8  4899.7  4920.4  4933.6  4936.2  4944.9  4966.5 4986.41
  4986.5 5013.39  5013.5  5026.7    5038  5046.7  5059.1  5079.5  5089.8  5104.2
  5140.6  5154.4  5166.9  5183.4  5185.5  5199.6  5218.1  5221.2  5225.9  5241.4
  5260.8  5269.1  5285.3  5305.8  5321.9  5332.9  5359.3  5401.2  5409.1  5423.2
  5451.4  5463.5  5479.2  5538.5
  680.11  678.93  678.13  677.51  676.21  673.72  672.95  672.39  670.26  669.08
  667.89  667.88  667.75  667.65  666.76  666.16  666.13     666     666     666
     666     666     666     666     666     666     666     666     666  666.37
   666.8  666.91  667.06  667.28  667.31  667.72  668.49  668.67  668.94  670.75
  671.85  672.18  673.14  674.72  675.02  675.67     677  678.03  678.36  678.74
  679.31  679.44  679.95  680.46
  680.11  678.92  678.12   677.5   676.2  673.71  672.94  672.38  670.25     668
  666.62  666.52  664.56  664.48   665.2  665.09  665.07  664.34  664.82  663.38
   664.6   664.6  663.31   663.5  663.52  664.28  664.81  663.69  663.56  663.38
  662.85  663.24  663.47  662.85  662.85  662.85  662.85  665.82  668.84  670.74
  671.84  672.17  673.13  674.71  675.01  675.66  676.99  678.02  678.35  678.73
   679.3  679.43  679.94  680.46
  4687.6  4703.9  4720.6  4731.7  4762.5    4797  4806.4  4816.9  4839.7  4865.2
  4881.4  4882.6  4893.8  4899.7  4920.4  4933.6  4936.2  4944.9  4966.5 4986.41
  4986.5 5013.39  5013.5  5026.7    5038  5046.7  5059.1  5079.5  5089.8  5104.2
  5140.6  5154.4  5166.9  5183.4  5185.5  5199.6  5218.1  5221.2  5225.9  5241.4
  5260.8  5269.1  5285.3  5305.8  5321.9  5332.9  5359.3  5401.2  5409.1  5423.2
  5451.4  5463.5  5479.2  5538.5
  680.11  678.93  678.13  677.51  676.21  673.72  672.95  672.39  670.26  669.08
  667.89  667.88  667.75  667.65  666.76  666.16  666.13     666     666     666
     666     666     666     666     666     666     666     666     666  666.37
   666.8  666.91  667.06  667.28  667.31  667.72  668.49  668.67  668.94  670.75
  671.85  672.18  673.14  674.72  675.02  675.67     677  678.03  678.36  678.74
  679.31  679.44  679.95  680.46
  679.86  678.67  677.87  677.25  675.95  673.46  672.69  672.13     670  667.75
  666.37  666.27  664.31  664.23  664.95  664.84  664.82  664.09  664.57  663.13
  664.35  664.35  663.06  663.25  663.27  664.03  664.56  663.44  663.31  663.13
   662.6  662.99  663.22   662.6   662.6   662.6   662.6  665.57  668.59  670.49
  671.59  671.92  672.88  674.46  674.76  675.41  676.74  677.77   678.1  678.48
  679.05  679.18  679.69  680.21
Abutment Skew #Up #Dn=, 2 , 2
 4986.30 4991.00
  664.60  657.50
 4986.30 4991.00
  664.35  657.25
Abutment Skew #Up #Dn=, 2 , 2
 5009.00 5013.59
  657.50  664.60
 5009.00 5013.59
  657.25  664.35
BR Coef= 1 , 1 , 0 ,1.25, 0 ,,,0.8,0,2,0,
Wspro=,,,, 1 ,,,, 0 ,,,, 0 ,,,,-1 ,-1 ,-1 , 0 , 0 , 0 , 0 , 0
BC Design=,, 0 ,, 0 ,,,,,,
BR U #Sta/Elev= 120
  4687.6  680.11    4695  679.57  4703.9  678.92  4707.3  678.76  4715.7  678.35
  4720.6  678.12  4731.7   677.5  4762.5   676.2  4762.8  676.18  4778.1  675.07
    4797  673.71  4806.4  672.94  4812.2  672.63  4816.3  672.41  4816.9  672.38
  4824.1  671.71  4825.8  671.52  4829.2  671.21  4839.7  670.25  4852.8  669.05
  4865.2     668  4881.4  666.62  4882.6  666.52  4893.8  664.56  4898.8  664.49
  4899.7  664.48  4918.4  665.13  4920.4   665.2  4933.6  665.09  4936.2  665.07
  4940.9  664.68  4944.9  664.34  4945.1  664.34  4965.1   664.8  4966.1  664.82
  4966.5  664.82 4986.41  663.38  4986.5  663.37  4987.5   663.3  4990.9   657.5
    4991   657.5    5000   657.5  5008.9   657.5    5009   657.5  5012.5   663.3
 5013.39  663.31  5013.5  663.31  5026.7   663.5    5038  663.52  5046.7  664.28
  5059.1  664.81  5079.5  663.69  5089.8  663.56  5104.2  663.38  5110.6   663.3
  5125.2  663.11  5128.5  663.05  5133.8  662.96  5140.6  662.85  5154.4  663.24
  5156.2  663.27  5166.9  663.47  5183.4  662.85  5185.5  662.85  5199.6  662.85
  5216.3  662.85  5218.1  662.85  5221.2  665.82  5225.9  668.84  5233.7  669.81
  5236.1   670.1  5238.9  670.45  5241.4  670.74  5258.7  671.72  5260.8  671.84
    5265  672.01  5269.1  672.17    5274  672.46  5281.4   672.9  5285.3  673.13
  5295.9  673.95  5297.9  674.11  5303.3  674.53  5304.7  674.63  5305.4  674.68
  5305.8  674.71  5306.5  674.73  5314.3  674.87  5321.9  675.01  5330.9  675.54
  5332.9  675.66  5346.1   676.3    5353   676.7  5356.8  676.87  5359.3  676.99
  5363.8  677.11  5366.8  677.19  5379.1  677.51  5383.5  677.62  5385.1  677.64
  5391.3  677.79  5395.4  677.88  5398.1  677.95  5401.2  678.02  5409.1  678.35
  5423.2  678.73  5428.1  678.83  5444.3  679.16  5451.4   679.3  5453.8  679.33
  5460.3   679.4  5463.5  679.43  5475.4  679.82  5476.5  679.85  5479.2  679.94
  5507.2  680.19  5509.7  680.21  5522.8  680.32  5526.7  680.36  5538.5  680.46
BR U #Mann= 3
 4687.60    0.13  4987.5    0.04  5012.5    0.13
BR U Banks=4987.50,5012.50
BR D #Sta/Elev= 120
  4687.6  679.86    4695  679.32  4703.9  678.67  4707.3  678.51  4715.7   678.1
  4720.6  677.87  4731.7  677.25  4762.5  675.95  4762.8  675.93  4778.1  674.82
    4797  673.46  4806.4  672.69  4812.2  672.38  4816.3  672.16  4816.9  672.13
  4824.1  671.46  4825.8  671.27  4829.2  670.96  4839.7     670  4852.8   668.8
  4865.2  667.75  4881.4  666.37  4882.6  666.27  4893.8  664.31  4898.8  664.24
  4899.7  664.23  4918.4  664.88  4920.4  664.95  4933.6  664.84  4936.2  664.82
  4940.9  664.43  4944.9  664.09  4945.1  664.09  4965.1  664.55  4966.1  664.57
  4966.5  664.57 4986.41  663.13  4986.5  663.12  4987.5  663.05  4990.9  657.25
    4991  657.25    5000  657.25  5008.9  657.25    5009  657.25  5012.5  663.05
 5013.39  663.06  5013.5  663.06  5026.7  663.25    5038  663.27  5046.7  664.03
  5059.1  664.56  5079.5  663.44  5089.8  663.31  5104.2  663.13  5110.6  663.05
  5125.2  662.86  5128.5   662.8  5133.8  662.71  5140.6   662.6  5154.4  662.99
  5156.2  663.02  5166.9  663.22  5183.4   662.6  5185.5   662.6  5199.6   662.6
  5216.3   662.6  5218.1   662.6  5221.2  665.57  5225.9  668.59  5233.7  669.56
  5236.1  669.85  5238.9   670.2  5241.4  670.49  5258.7  671.47  5260.8  671.59
    5265  671.76  5269.1  671.92    5274  672.21  5281.4  672.65  5285.3  672.88
  5295.9   673.7  5297.9  673.86  5303.3  674.28  5304.7  674.38  5305.4  674.43
  5305.8  674.46  5306.5  674.48  5314.3  674.62  5321.9  674.76  5330.9  675.29
  5332.9  675.41  5346.1  676.05    5353  676.45  5356.8  676.62  5359.3  676.74
  5363.8  676.86  5366.8  676.94  5379.1  677.26  5383.5  677.37  5385.1  677.39
  5391.3  677.54  5395.4  677.63  5398.1   677.7  5401.2  677.77  5409.1   678.1
  5423.2  678.48  5428.1  678.58  5444.3  678.91  5451.4  679.05  5453.8  679.08
  5460.3  679.15  5463.5  679.18  5475.4  679.57  5476.5   679.6  5479.2  679.69
  5507.2  679.94  5509.7  679.96  5522.8  680.07  5526.7  680.11  5538.5  680.21
BR D #Mann= 3
 4687.60    0.13  4987.5    0.04  5012.5    0.13
BR D Banks=4987.50,5012.50

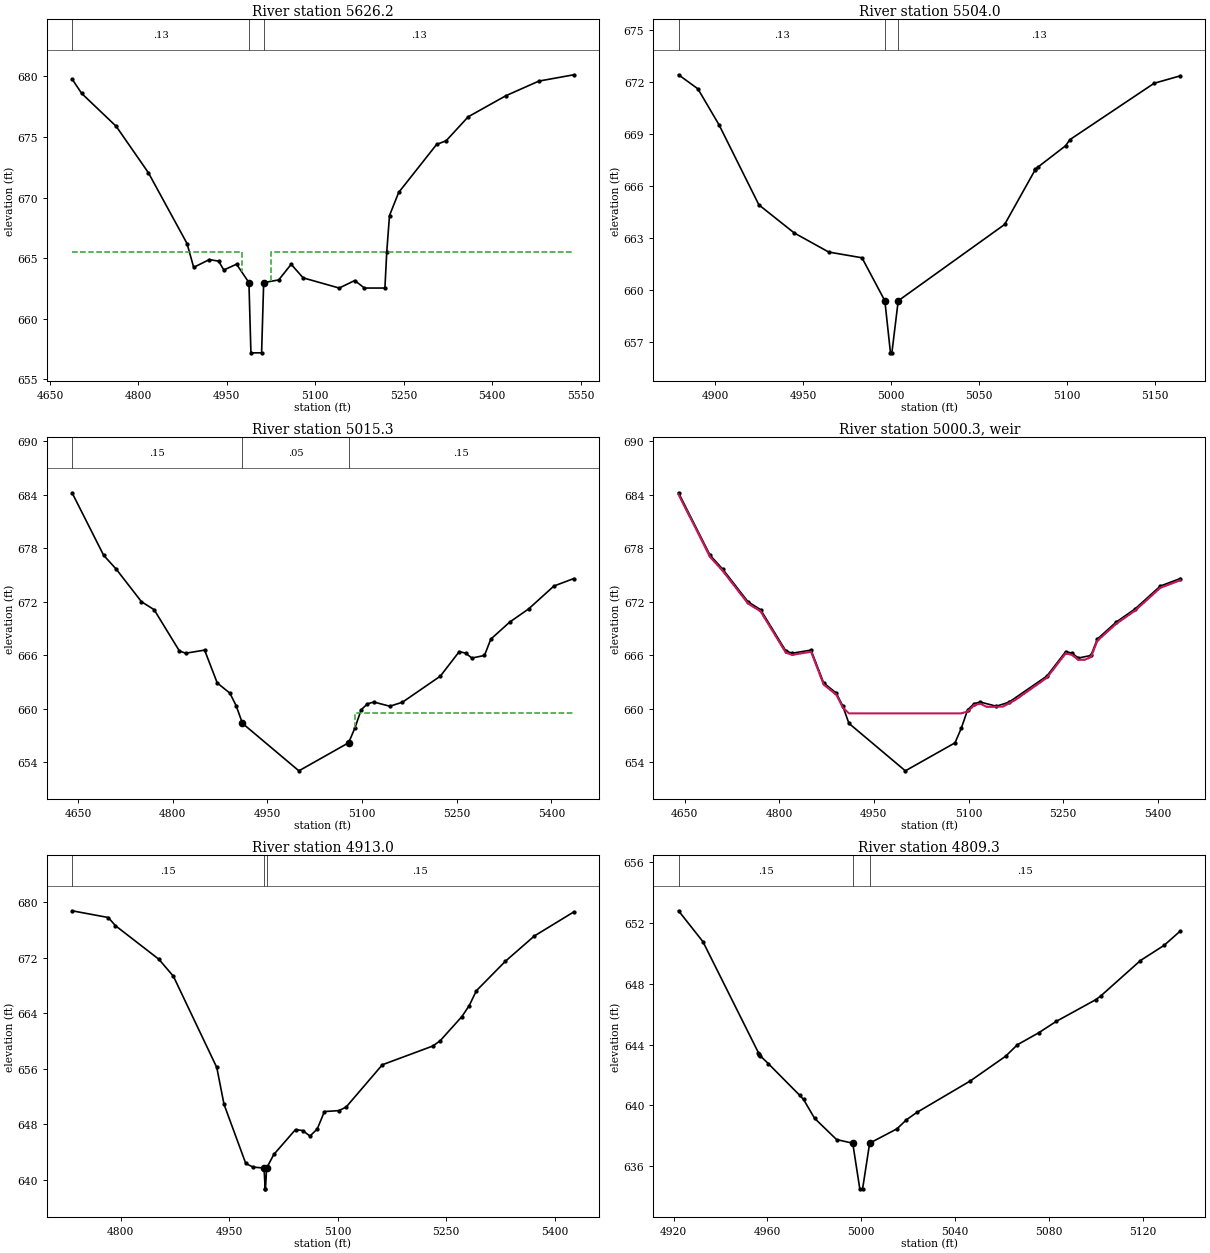
Type RM Length L Ch R = 1 ,5626.2,122.2,122.2,122.2
XS GIS Cut Line= 3
      1851609.77       898738.69      1851762.70       898449.82
      1851985.05       897975.28
BEGIN DESCRIPTION:
Downstream Section of Bridge/Culvert/Weir
END DESCRIPTION:
#Sta/Elev= 30
  4687.6  679.79  4703.9   678.6  4762.5  675.88  4816.9  672.06  4882.6   666.2
  4893.8  664.24  4920.4  664.88  4936.2  664.75  4944.9  664.02  4966.5   664.5
  4987.5  662.98  4990.9  657.18    5009  657.18  5012.5  662.98    5038   663.2
  5059.1  664.49  5079.5  663.37  5140.6  662.53  5166.9  663.15  5183.4  662.53
  5218.1  662.53  5221.2   665.5  5225.9  668.52  5241.4  670.42  5305.8  674.39
  5321.9  674.69  5359.3  676.67  5423.2  678.41  5479.2  679.62  5538.5  680.14
#Mann= 3 , 1 , 0
 4687.60    0.13       0  4987.5    0.04       0  5012.5    0.13       0
#XS Ineff= 2 , 0
       0    4975   665.5    5025       0   665.5
Bank Sta=4987.50,5012.50
Exp/Cntr=0.5,0.3

Type RM Length L Ch R = 1 ,5504.0,488.7,488.7,488.7
XS GIS Cut Line= 3
      1851777.81       898663.48      1851825.72       898570.85
      1851903.54       898407.42
BEGIN DESCRIPTION:
Jones Creek 11.0
END DESCRIPTION:
#Sta/Elev= 19
  4879.1  672.39  4890.1  671.58  4902.1  669.51  4924.8  664.89  4944.9  663.27
  4964.5  662.17  4983.4  661.84  4996.4  659.36  4999.6  656.36  5000.4  656.36
    5004  659.36  5064.5  663.76  5081.7  666.88    5082  666.93  5083.7  667.09
  5099.2   668.3  5101.6  668.65  5149.5   671.9  5164.4  672.33
#Mann= 3 , 1 , 0
 4879.10    0.13       0  4996.4    0.05       0    5004    0.13       0
Bank Sta=4996.40,5004.00
Exp/Cntr=0.3,0.1

Type RM Length L Ch R = 1 ,5015.3,102.3,102.3,102.3
XS GIS Cut Line= 4
      1852155.64       898846.11      1852284.37       898516.01
      1852329.91       898368.00      1852314.88       898082.47
BEGIN DESCRIPTION:
Upstream Section of Bridge/Culvert/Weir
END DESCRIPTION:
#Sta/Elev= 30
  4640.5  684.22  4690.5  677.22  4710.5  675.66  4750.5  672.01  4770.5  671.12
  4810.5   666.5  4820.5  666.24  4850.5  666.59  4870.5  662.91  4890.5  661.77
  4900.5  660.36  4910.5  658.38  4999.9  653.06  5078.6   656.2  5088.6  657.85
  5098.6   659.9  5108.6  660.57  5118.6  660.77    5144   660.3    5164  660.75
    5224  663.67    5254  666.42    5264  666.25    5274   665.7    5294  665.99
    5304  667.82    5334  669.73    5364  671.21    5404  673.77  5435.6  674.61
#Mann= 3 , 1 , 0
 4640.50    0.15       0  4910.5    0.05       0  5078.6    0.15       0
#XS Ineff= 2 , 0
       0  4900.5   659.5  5088.6       0   659.5
Bank Sta=4910.50,5078.60
Exp/Cntr=0.5,0.3

Type RM Length L Ch R = 5 ,5000.3,,,
BEGIN DESCRIPTION:
Unnamed Dam (Jones)
Structure ID: Unnamed Dam
Approximate Survey Structure
END DESCRIPTION:
#Inline Weir SE= 30
  4640.5  684.03  4690.5  677.03  4710.5  675.47  4750.5  671.82  4770.5  670.93
  4810.5  666.31  4820.5  666.05  4850.5  666.41  4870.5  662.73  4890.5  661.59
  4900.5  660.18  4910.5   659.5  5088.6   659.5  5098.6  659.72  5108.6  660.39
  5118.6  660.59  5128.6  660.24    5154  660.25    5174     661    5224  663.48
    5254  666.23    5264  666.06    5274  665.51    5284  665.51    5294   665.8
    5304  667.63    5334  669.54    5364  671.02    5404  673.58  5435.6  674.42
IW Dist,WD,Coef,Skew,MaxSub,Min_El,Is_Ogee,SpillHt,DesHd
10.0,10.0,3.0,,0.95,, 0 ,,,1.0,1.0,

Type RM Length L Ch R = 1 ,4913.0,103.7,103.7,103.7
XS GIS Cut Line= 3
      1852308.47       898780.77      1852390.44       898514.35
      1852520.24       898120.40
BEGIN DESCRIPTION:
Unnamed Dam DS
END DESCRIPTION:
#Sta/Elev= 30
  4732.9  678.77  4782.9   677.8  4792.9  676.62  4852.9  671.78  4872.9  669.34
  4932.9  656.19  4942.9  650.88  4972.9  642.37  4982.9  641.83  4998.2   641.7
  4999.8   638.7  5000.2   638.7  5001.8   641.7  5011.7  643.65  5041.7  647.24
  5051.7   647.1  5061.7   646.3  5071.7  647.32  5081.7  649.84  5101.7  649.97
  5111.7  650.49  5161.7  656.58  5231.7  659.29  5241.7  660.05  5271.7  663.53
  5281.7  665.09  5291.7  667.25  5331.7  671.49  5371.7  675.13  5426.4  678.61
#Mann= 3 , 1 , 0
 4732.90    0.15       0  4998.2    0.05       0  5001.8    0.15       0
Bank Sta=4998.20,5001.80
Exp/Cntr=0.5,0.3

Type RM Length L Ch R = 1 ,4809.3,309.3,309.3,309.3
XS GIS Cut Line= 3
      1852450.17       898602.35      1852488.38       898546.81
      1852507.41       898401.47
BEGIN DESCRIPTION:
Jones Creek 10.0
END DESCRIPTION:
#Sta/Elev= 28
  4922.1   652.8  4932.5  650.77  4956.2  643.46  4956.5  643.37  4956.6  643.32
    4957  643.26  4960.4  642.75  4973.7  640.68  4975.4   640.4  4980.1  639.16
  4989.5  637.76  4996.4  637.52  4999.4  634.52  5000.6  634.52  5003.6  637.52
  5015.3  638.47  5019.3  639.06  5023.7  639.54  5046.5  641.61  5061.6  643.24
  5066.6  643.99  5075.7  644.78  5083.2  645.53  5100.1  646.96  5102.1  647.19
  5119.1  649.53  5129.2  650.53  5136.1  651.47
#Mann= 3 , 1 , 0
 4922.10    0.15       0  4996.4    0.05       0  5003.6    0.15       0
Bank Sta=4996.40,5003.60
Exp/Cntr=0.3,0.1

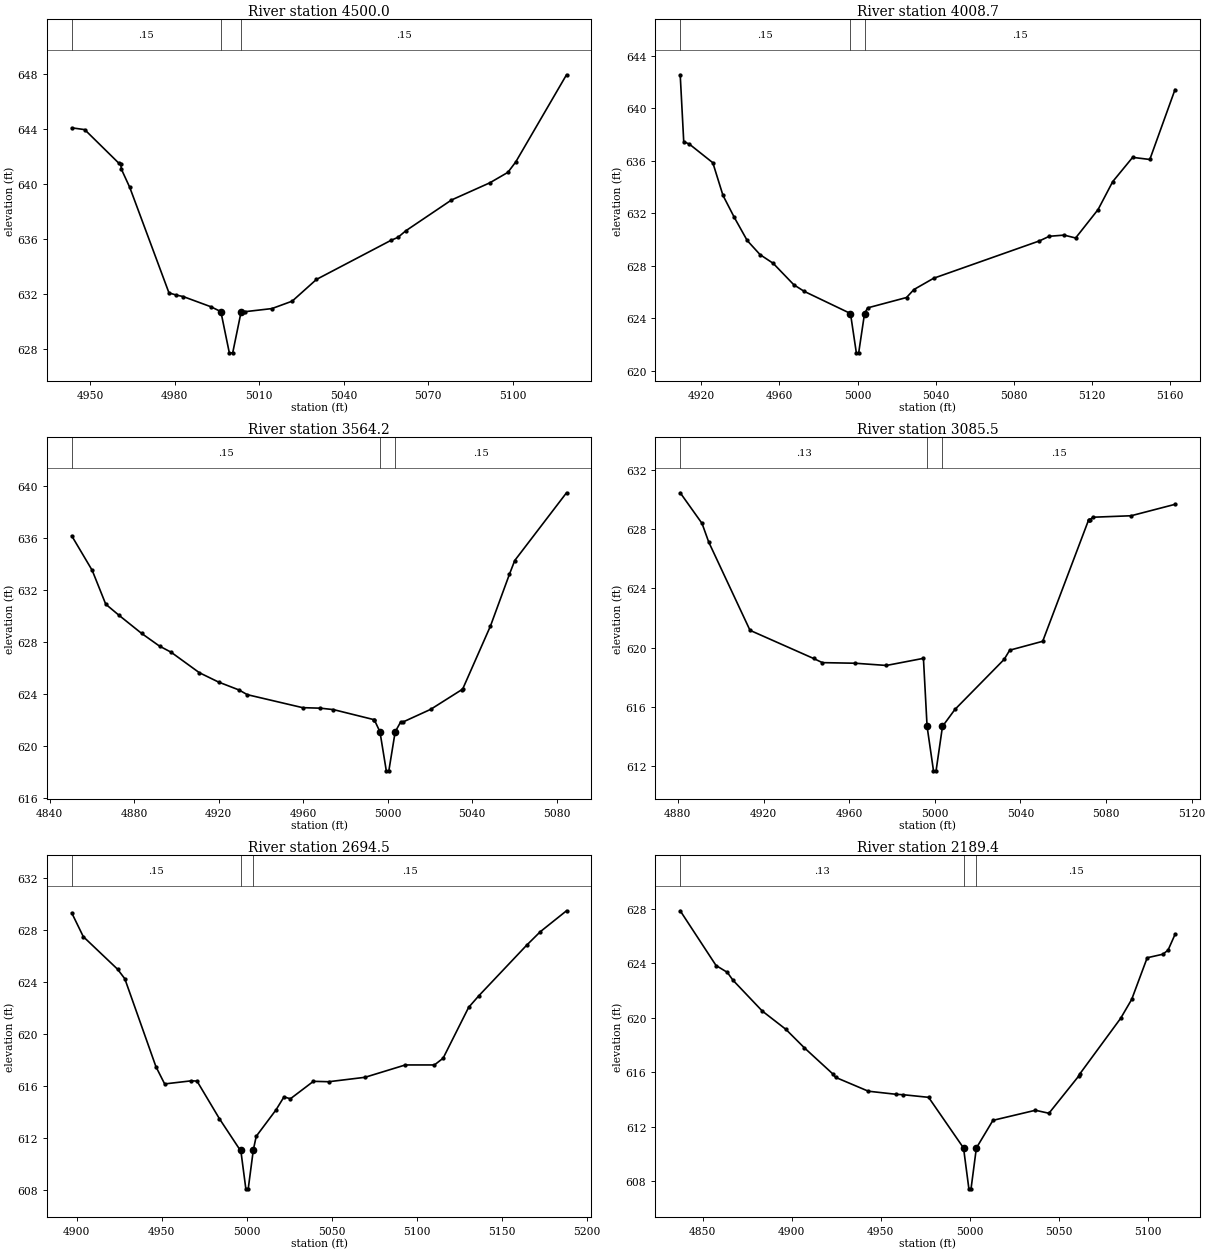
Type RM Length L Ch R = 1 ,4500.0,491.3,491.3,491.3
XS GIS Cut Line= 3
      1852701.83       898776.81      1852705.37       898720.42
      1852767.35       898618.83
BEGIN DESCRIPTION:
Jones Creek 9.0
END DESCRIPTION:
#Sta/Elev= 26
  4943.5  644.06  4948.1  643.93  4960.1  641.51  4960.9   641.4  4961.1  641.06
  4964.1  639.72    4978  632.05  4980.5   631.9  4983.1  631.78  4992.9  631.04
  4996.4  630.69  4999.4  627.69  5000.6  627.69  5003.6  630.69  5004.8  630.68
  5014.5  630.91  5021.7  631.45  5030.3  633.03  5056.7  635.87  5059.2  636.09
    5062  636.57  5078.2  638.81  5091.8  640.06  5098.2  640.82    5101  641.58
    5119  647.92
#Mann= 3 , 1 , 0
 4943.50    0.15       0  4996.4    0.05       0  5003.6    0.15       0
Bank Sta=4996.40,5003.60
Exp/Cntr=0.3,0.1

Type RM Length L Ch R = 1 ,4008.7,444.5,444.5,444.5
XS GIS Cut Line= 3
      1853153.05       898936.37      1853164.77       898845.53
      1853198.67       898687.32
BEGIN DESCRIPTION:
Jones Creek 8.0
END DESCRIPTION:
#Sta/Elev= 28
  4909.2  642.57    4911  637.47  4913.9  637.28  4925.9  635.86  4931.1  633.37
  4936.9  631.69  4943.5  629.93  4950.1  628.85  4956.8  628.19  4967.4  626.55
  4972.7  626.05  4996.4  624.36  4999.4  621.36  5000.6  621.36  5003.6  624.36
  5005.2  624.79  5025.1  625.58  5028.9  626.19    5039  627.05  5093.2   629.9
  5098.2  630.25  5105.8  630.34  5111.7  630.12  5123.2  632.29  5130.7  634.42
  5140.9  636.27  5149.7  636.11  5162.6  641.44
#Mann= 3 , 1 , 0
 4909.20    0.15       0  4996.4    0.05       0  5003.6    0.15       0
Bank Sta=4996.40,5003.60
Exp/Cntr=0.3,0.1

Type RM Length L Ch R = 1 ,3564.2,478.7,478.7,478.7
XS GIS Cut Line= 3
      1853570.86       898942.55      1853580.22       898787.16
      1853542.26       898718.41
BEGIN DESCRIPTION:
Jones Creek 7.0
END DESCRIPTION:
#Sta/Elev= 29
  4850.5  636.18  4860.2  633.52  4866.6  630.92    4873  630.05  4883.6  628.67
  4892.1  627.69  4897.5  627.23  4910.9  625.65    4920  624.93  4929.7  624.32
  4933.6  623.96  4959.8  622.96  4968.2  622.92  4974.4  622.81  4993.5  622.04
  4993.8     622  4996.4   621.1  4999.4   618.1  5000.6   618.1  5003.6   621.1
  5006.2  621.86  5007.2  621.85  5020.4  622.83    5035  624.33  5035.6  624.41
  5048.7  629.24  5057.7  633.23  5060.2  634.28  5084.7  639.49
#Mann= 3 , 1 , 0
 4850.50    0.15       0  4996.4    0.05       0  5003.6    0.15       0
Bank Sta=4996.40,5003.60
Exp/Cntr=0.3,0.1

Type RM Length L Ch R = 1 ,3085.5,391,391,391
XS GIS Cut Line= 3
      1853940.90       898825.19      1854057.48       898728.79
      1854015.97       898660.60
BEGIN DESCRIPTION:
Jones Creek 6.0
END DESCRIPTION:
#Sta/Elev= 23
  4881.1  630.45  4891.3  628.38  4894.4  627.13  4913.7  621.17  4943.4  619.27
  4947.5  618.99  4962.8  618.95  4977.4   618.8  4994.7  619.28  4996.4  614.69
  4999.4  611.69  5000.6  611.69  5003.6  614.69  5009.4  615.83  5032.4  619.21
    5035  619.83  5050.4  620.43  5071.8   628.6    5072  628.61  5072.3   628.6
  5073.8   628.8  5091.7   628.9  5112.2  629.67
#Mann= 3 , 1 , 0
 4881.10    0.13       0  4996.4    0.05       0  5003.6    0.15       0
Bank Sta=4996.40,5003.60
Exp/Cntr=0.3,0.1

Type RM Length L Ch R = 1 ,2694.5,505.1,505.1,505.1
XS GIS Cut Line= 3
      1854037.04       899185.72      1854091.81       899079.00
      1854204.82       898951.00
BEGIN DESCRIPTION:
Jones Creek 5.0
END DESCRIPTION:
#Sta/Elev= 29
  4897.1  629.35  4903.9  627.52    4924  625.02  4928.3  624.28  4946.6  617.51
  4951.7  616.19  4967.4  616.43  4970.7  616.41  4983.9  613.51    4996  611.11
  4996.4  611.12  4999.4  608.12  5000.8  608.12  5003.8  611.12  5005.5  612.16
  5017.1  614.19  5021.8  615.19  5025.6  615.05  5039.1  616.39  5048.1  616.36
  5069.4   616.7  5093.1  617.65  5110.2  617.65  5115.3  618.17  5130.3  622.08
  5136.2  622.96  5164.3  626.85  5172.4   627.9  5187.8  629.51
#Mann= 3 , 1 , 0
 4897.10    0.15       0  4996.4    0.05       0  5003.8    0.15       0
Bank Sta=4996.40,5003.80
Exp/Cntr=0.3,0.1

Type RM Length L Ch R = 1 ,2189.4,617,617,617
XS GIS Cut Line= 3
      1854361.72       899383.86      1854469.49       899260.98
      1854529.00       899163.68
BEGIN DESCRIPTION:
Jones Creek 4.0
END DESCRIPTION:
#Sta/Elev= 28
  4837.5  627.86  4857.6  623.84  4863.9  623.34  4867.1  622.76  4883.5   620.5
  4896.7  619.16  4907.1   617.8    4923  615.89  4924.6  615.63    4943  614.61
  4958.8  614.38  4962.7  614.35  4976.8  614.16  4996.4  610.44  4999.4  607.44
  5000.6  607.44  5003.6  610.44  5012.9  612.47  5036.7  613.21  5044.3  612.99
  5061.1  615.74  5061.5  615.86  5084.5  619.96  5090.7  621.35  5099.4  624.41
  5108.2  624.67  5111.1  624.97    5115  626.12
#Mann= 3 , 1 , 0
 4837.50    0.13       0  4996.4    0.05       0  5003.6    0.15       0
Bank Sta=4996.40,5003.60
Exp/Cntr=0.3,0.1

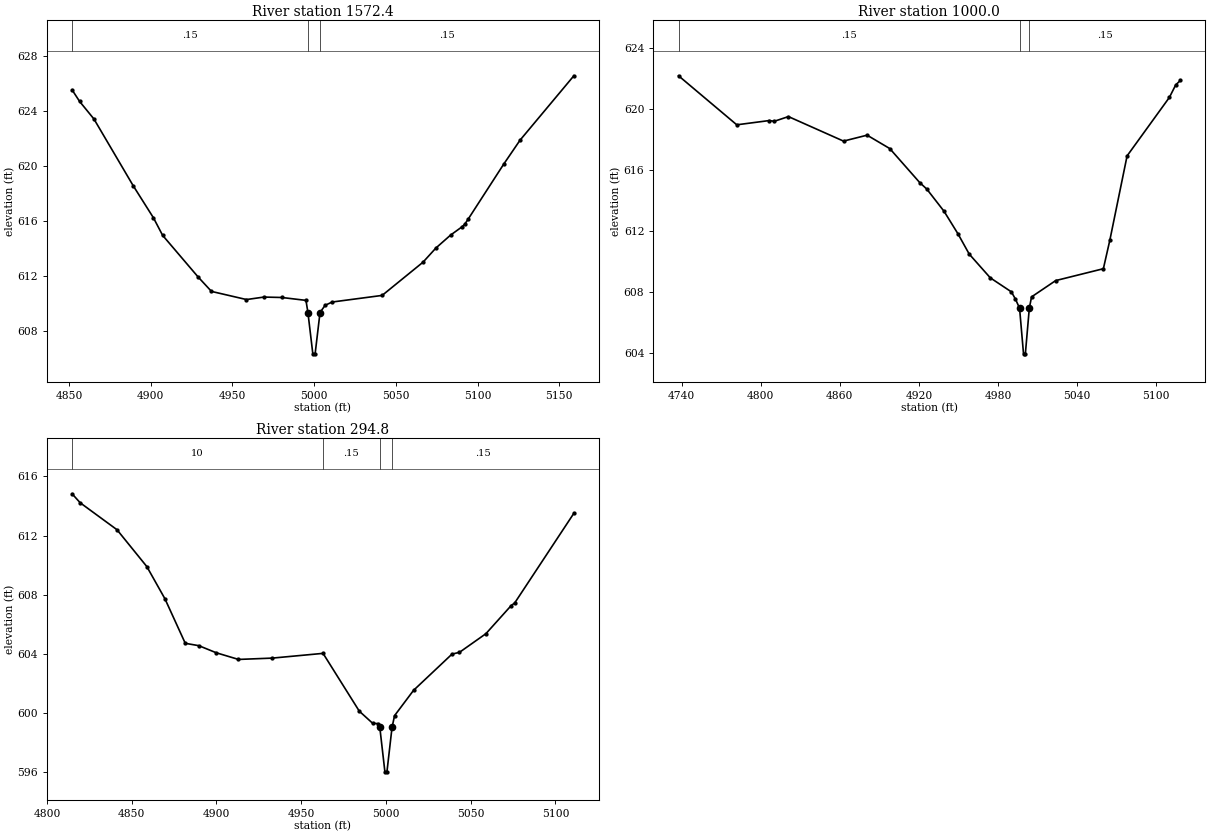
Type RM Length L Ch R = 1 ,1572.4,572.4,572.4,572.4
XS GIS Cut Line= 3
      1854891.67       899650.63      1854977.65       899521.92
      1854975.84       899369.72
BEGIN DESCRIPTION:
Jones Creek 3.0
END DESCRIPTION:
#Sta/Elev= 28
  4851.9  625.52  4856.5  624.68  4865.3   623.4  4889.3  618.56  4901.7  616.23
  4907.3  614.96    4929  611.94  4937.2  610.89  4958.6   610.3  4969.3  610.48
  4980.2  610.45    4995  610.24  4996.2  609.36  4999.2  606.36  5000.6  606.36
  5003.6  609.36  5006.7  609.88    5011  610.12  5041.6   610.6  5066.6  613.01
  5074.5  614.04  5083.5  614.98  5090.5  615.58  5092.1  615.76  5094.2  616.13
    5116  620.13    5126  621.87  5158.9  626.54
#Mann= 3 , 1 , 0
 4851.90    0.15       0  4996.2    0.05       0  5003.6    0.15       0
Bank Sta=4996.20,5003.60
Exp/Cntr=0.3,0.1

Type RM Length L Ch R = 1 ,1000.0,705.2,705.2,705.2
XS GIS Cut Line= 3
      1855266.40       899728.58      1855357.65       899482.56
      1855350.73       899364.36
BEGIN DESCRIPTION:
Jones Creek 2.0
END DESCRIPTION:
#Sta/Elev= 28
  4737.6  622.18  4781.8  618.96  4806.5  619.24  4810.2  619.19    4821   619.5
  4862.8  617.89  4880.7  618.28  4897.9   617.4  4920.6  615.17    4926  614.74
  4939.1  613.28  4949.6  611.81  4958.2  610.47  4974.2  608.91  4990.2  607.99
  4993.3  607.51  4996.4  606.92  4999.4  603.92  5000.8  603.92  5003.8  606.92
  5005.5  607.66  5023.8  608.73    5060  609.51  5064.9  611.38    5078  616.92
  5110.1  620.76  5114.9  621.58  5118.4  621.87
#Mann= 3 , 1 , 0
 4737.60    0.15       0  4996.4    0.05       0  5003.8    0.15       0
Bank Sta=4996.40,5003.80
Exp/Cntr=0.3,0.1

Type RM Length L Ch R = 1 ,294.8,0,0,0
XS GIS Cut Line= 3
      1855588.96       900050.99      1855754.30       899987.16
      1855816.84       899886.07
BEGIN DESCRIPTION:
Jones Creek 1.0
END DESCRIPTION:
#Sta/Elev= 26
  4814.8  614.83  4819.6  614.22  4841.3   612.4  4858.9  609.91  4869.6  607.73
  4881.6  604.72  4889.6  604.56  4899.9  604.08    4913  603.63    4933  603.72
  4962.9  604.04  4984.3  600.13  4992.2  599.31  4995.4  599.29  4996.4  599.03
  4999.4  596.03  5000.6  596.03  5003.6  599.03  5005.1  599.83  5016.3  601.54
    5039  603.99  5043.4  604.11    5059  605.37  5073.9  607.27    5076  607.45
  5110.9  613.51
#Mann= 4 , 1 , 0
 4814.80      10       0  4962.9    0.15       0  4996.4    0.05       0
  5003.6    0.15       0
Bank Sta=4996.40,5003.60
Exp/Cntr=0.3,0.1

Chan Stop Cuts=-1