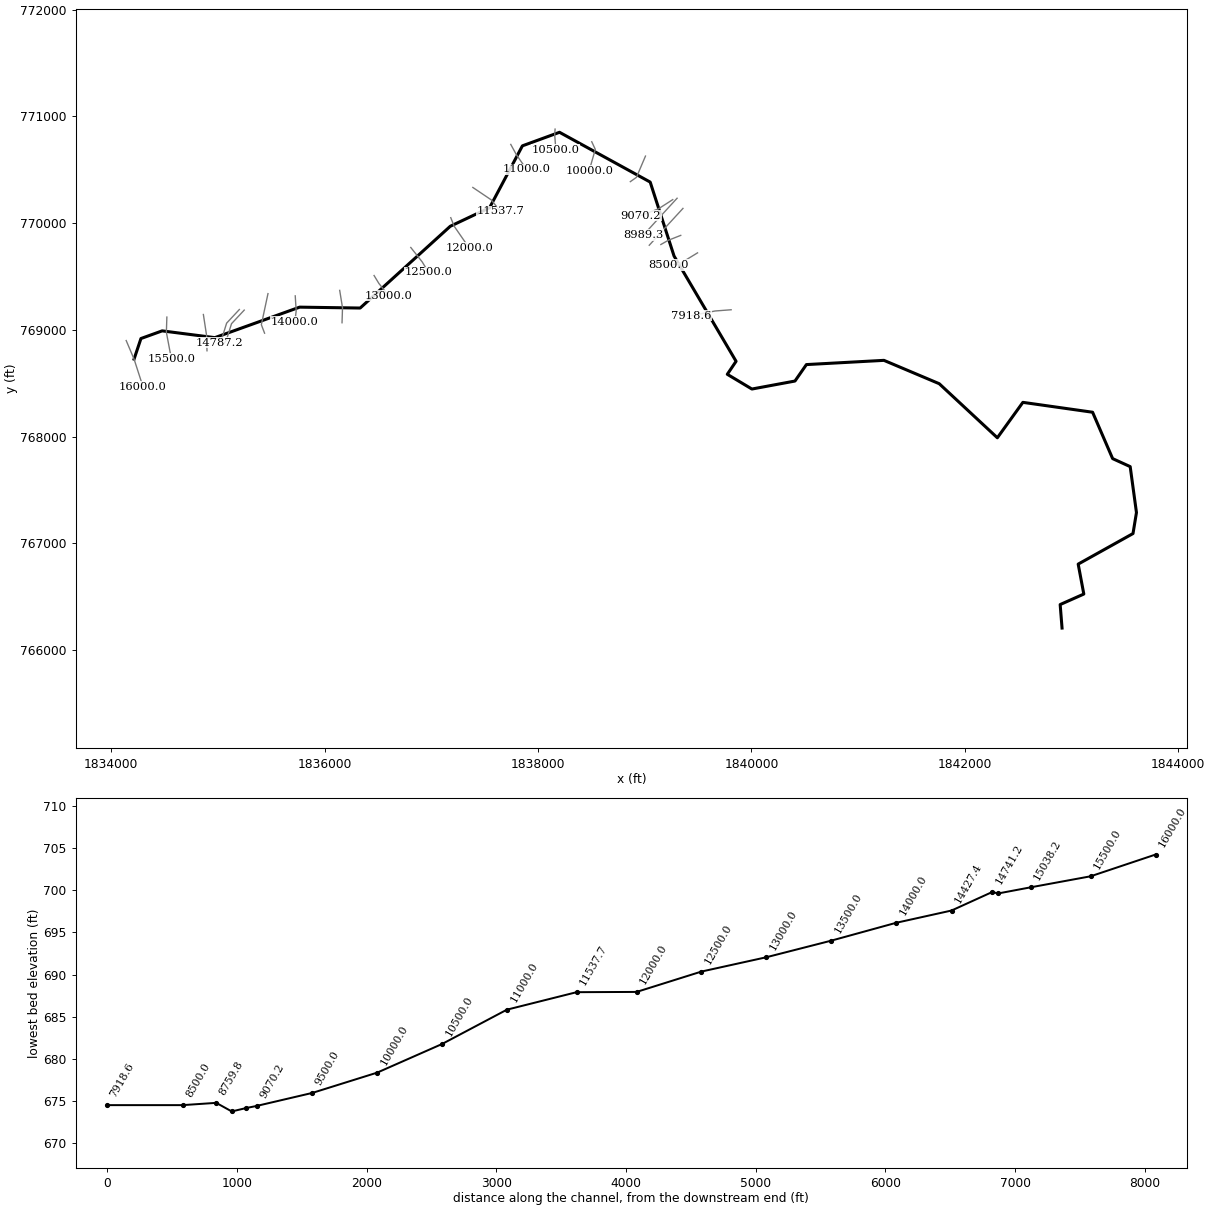
--- NORTH PRONG CREEK.PRJ (project) ---

Proj Title=North Prong Creek
Current Plan=p01
Default Exp/Contr=0.3,0.1
English Units
Geom File=g01
Flow File=f01
Plan File=p01
Y Axis Title=Elevation
X Axis Title(PF)=Main Channel Distance
X Axis Title(XS)=Station
BEGIN DESCRIPTION:
####(Watershed Name)####
NORTH PRONG CREEK
HCFCD Unit X###-##-##
(Flood Hazard, Floodway) Model
10, 2, 1, 0.2% Event
Filename:  N:\NC_flood\60273\Approximates\Eng\Rocky_River\Eng\North Prong Creek\North Prong Creek.prj
Prepared by:  ________     Date: ________
Reviewed by:  ________     Date: ________
STATUS (Draft RAS, SVSQ, FINAL)
END DESCRIPTION:
DSS Export Rating Curves= 0
DSS Export Rating Curve Sorted= 0
DSS Export Volume Flow Curves= 0
DXF OffsetX= 0
DXF OffsetY= 0
DXF ScaleX= 1
DXF ScaleY= 10

--- North Prong Creek.p01 (plan) ---

Plan Title=100-Year-Single
Program Version=3.10
Short Identifier=Plan01
Geom File=g01
Flow File=f01
Subcritical Flow
K Sum by GR= 0
Std Step Tol= 0.01
Critical Tol= 0.01
Num of Std Step Trials= 20
Max Error Tol= 0.3
Flow Tol Ratio= 0.001
Split Flow NTrial= 30
Split Flow Tol= 0.02
Split Flow Ratio= 0.02
Log Output Level= 0
Friction Slope Method= 1
Unsteady Friction Slope Method= 2
Parabolic Critical Depth
Global Vel Dist= 0 , 0 , 0
Global Log Level= 0
CheckData=True
Encroach Param=-1 ,0,0, 2
Encroach River=NorthProngCreek
Encroach Reach=Reach - 1
Encroach Node=16000.0
       1 4917.65 5012.75
Encroach Node=15500.0
       1 4963.05 5091.15
Encroach Node=15038.2
       1 4934.14 5059.16
Encroach Node=14787.2
       1  4979.5  5021.5
Encroach Node=14764.2
       1  4979.5  5021.5
Encroach Node=14741.2
       1  4979.5  5021.5
Encroach Node=14427.4
       1 4869.23    5016
Encroach Node=14000.0
       1 4964.81 5035.25
Encroach Node=13500.0
       1 4934.19 5056.65
Encroach Node=13000.0
       1 4984.78 5087.03
Encroach Node=12500.0
       1 4924.35 5027.22
Encroach Node=12000.0
       1    4983 5146.21
Encroach Node=11537.7
       1 4887.28  5042.1
Encroach Node=11000.0
       1 4958.62 5088.52
Encroach Node=10500.0
       1 4984.38 5065.31
Encroach Node=10000.0
       1 4984.36 5150.24
Encroach Node=9500.0
       1 4883.77 5009.82
Encroach Node=9070.2
       1 4902.28 5015.78
Encroach Node=8989.3
       1 4983.55 5016.67
Encroach Node=8934.3
       1 4983.55 5016.67
Encroach Node=8879.3
       1 4983.55 5016.67
Encroach Node=8759.8
       1    4960    5029
Encroach Node=8500.0
       1 4881.29  5010.9
Encroach Node=7918.6
       1 4940.61 5127.56
Encroach Node=7500.0
       1 4948.56 5108.03
Encroach Node=7000.0
       1 4837.73    5015
Encroach Node=6500.0
       1 4827.74    5020
Encroach Node=5991.5
       1 4928.25 5046.21
Encroach Node=5504.5
       1    4950    5050
Encroach Node=5000.0
       1    4965    5046
Encroach Node=4500.0
       1    4965 5020.82
Encroach Node=4000.0
       1 4903.13    5016
Encroach Node=3500.0
       1    4950 5119.89
Encroach Node=3037.5
       1 4951.38 5013.29
Encroach Node=2500.0
       1 4949.25 5060.85
Encroach Node=2000.0
       1 4859.81 5016.11
Encroach Node=1500.0
       1 4964.79 5172.76
Encroach Node=1034.4
       1    4909    5100
Encroach Node=932.2
       1    4900  5017.5
Encroach Node=911.7
       1    4900  5017.5
Encroach Node=891.2
       1    4900  5017.5
Encroach Node=665.8
       1 4829.53 5029.23
Computation Interval=1HOUR
Output Interval=1HOUR
Run HTab= 0
Run UNet= 0
Run PostProcess= 0
UNET Theta= 1
UNET Theta Warmup= 1
UNET ZTol= 0.02
UNET ZSATol= 0.05
UNET MxIter= 20
UNET MaxInSteps= 1
UNET DtIC= 0
UNET DtMin= 0
UNET MaxCRTS= 20
UNET WFStab= 2
UNET SFStab= 1
UNET WFX= 1
UNET SFX= 1
UNET DSS MLevel= 4
UNET Convert EG Bridges=-1
UNET Use Existing IB Tables=-1
UNET Froude Reduction=False
UNET Froude Limit= 1
UNET Froude Power= 10
Instantaneous Interval=1HOUR
Write IC File= 0
Echo Input=False
Echo Output=False
Write Detailed= 0

--- North Prong Creek.f01 (steady flow) ---

Flow Title= 100-Year-Single
Program Version=3.10
Number of Profiles= 2
Profile Names=100-Year,100-yr FW
River Rch & RM=NorthProngCreek,Reach - 1       ,16000.0
     803     803
River Rch & RM=NorthProngCreek,Reach - 1       ,14000
     946     946
River Rch & RM=NorthProngCreek,Reach - 1       ,9500
    1388    1388
River Rch & RM=NorthProngCreek,Reach - 1       ,9070.2
    1535    1535
River Rch & RM=NorthProngCreek,Reach - 1       ,2000.0
    1848    1848
Boundary for River Rch & Prof#=NorthProngCreek,Reach - 1       , 1
Up Type= 0
Dn Type= 3
Dn Slope=0.0043
Boundary for River Rch & Prof#=NorthProngCreek,Reach - 1       , 2
Up Type= 0
Dn Type= 1
Dn Known WS=657.68
DSS Import GetInterval= 0
DSS Import GetPeak= 0
DSS Import FillOption= 0

--- NORTH PRONG CREEK.g01 (geometry) ---

Geom Title=Geom 01 by CodeH2 for Windows

River Reach=NorthProngCreek,Reach - 1
Reach XY= 30
      1834214.25       768726.27      1834278.75       768919.06
       1834477.5       768990.81      1834971.38       768927.38
      1835766.13          769213      1836333.25       769204.69
      1837177.62        769970.5      1837546.12       770144.31
      1837853.75       770723.81       1838201.5       770850.75
      1839051.37       770384.37         1839275       769691.75
      1839856.25       768705.87         1839774       768584.06
       1840004.5       768446.06      1840408.25       768520.87
      1840515.37       768675.06         1841242       768714.69
      1841760.25       768495.94      1842304.87        767989.5
      1842544.25       768321.25       1843197.5       768228.75
      1843385.37       767794.25      1843549.88       767719.38
      1843608.62       767289.19      1843576.25        767092.5
       1843062.5       766806.25      1843115.25       766525.81
      1842893.62       766427.44      1842911.25       766207.25

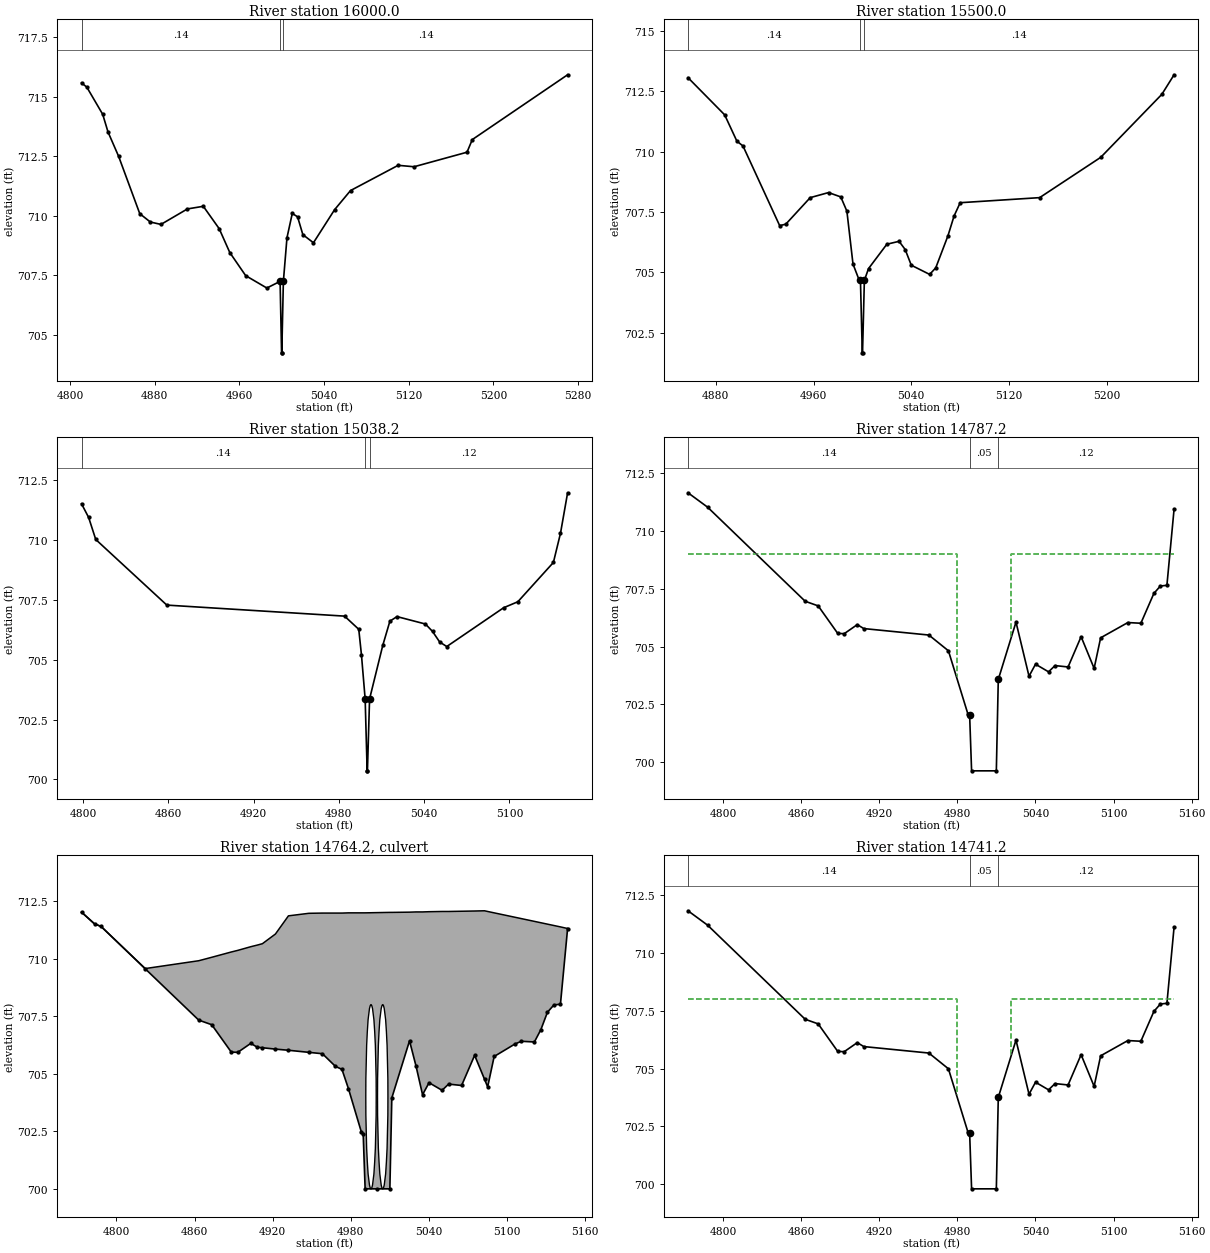
Type RM Length L Ch R = 1 ,16000.0,500,500,500
XS GIS Cut Line= 3
      1834140.33       768900.22      1834214.26       768726.27
      1834297.35       768469.38
BEGIN DESCRIPTION:
North Prong Creek 32.0
END DESCRIPTION:
#Sta/Elev= 30
    4811  715.58    4816   715.4    4831  714.26    4836  713.52    4846   712.5
    4866  710.09    4876  709.74    4886  709.64    4911  710.29    4926   710.4
    4941  709.46    4951  708.46    4966  707.49    4986  706.97  4998.5  707.25
  4999.9  704.25  5000.1  704.25  5001.6  707.25    5005  709.08    5010   710.1
    5015  709.96    5020  709.21    5030  708.87    5050  710.26    5065  711.06
    5110  712.12    5125  712.06    5175  712.67    5180   713.2    5270  715.92
#Mann= 3 , 1 , 0
 4811.00    0.14       0  4998.5    0.05       0  5001.6    0.14       0
Bank Sta=4998.50,5001.60
Exp/Cntr=0.3,0.1

Type RM Length L Ch R = 1 ,15500.0,461.8,461.8,461.8
XS GIS Cut Line= 3
      1834521.62       769120.07      1834517.02       768977.45
      1834564.30       768726.87
BEGIN DESCRIPTION:
North Prong Creek 31.0
END DESCRIPTION:
#Sta/Elev= 30
  4857.3  713.07  4887.3  711.53  4897.3  710.44  4902.3  710.24  4932.3  706.94
  4937.3     707  4957.3   708.1  4972.3  708.31  4982.3  708.13  4987.3  707.54
  4992.3  705.35  4997.3  704.69  4998.4  704.67  4999.9  701.67  5000.1  701.67
  5001.6  704.67    5005  705.16    5020  706.17    5030  706.29    5035  705.95
    5040   705.3    5055  704.92    5060  705.19    5070  706.52    5075  707.34
    5080  707.89    5145   708.1    5195  709.77    5245  712.38    5255  713.19
#Mann= 3 , 1 , 0
 4857.30    0.14       0  4998.4    0.05       0  5001.6    0.14       0
Bank Sta=4998.40,5001.60
Exp/Cntr=0.3,0.1

Type RM Length L Ch R = 1 ,15038.2,251,251,251
XS GIS Cut Line= 3
      1834863.86       769144.04      1834893.63       768949.49
      1834897.73       768804.47
BEGIN DESCRIPTION:
North Prong Creek 30.0
END DESCRIPTION:
#Sta/Elev= 23
    4799  711.51    4804  710.94    4809  710.02    4859  707.28    4984  706.82
    4994  706.27  4995.9   705.2  4998.5  703.36  4999.9  700.36  5000.1  700.36
  5001.6  703.36  5010.9   705.6  5015.9  706.61  5020.9   706.8  5040.9  706.49
  5045.9  706.18  5050.9  705.74  5055.9  705.55  5095.9  707.17  5105.9  707.42
  5130.9  709.06  5135.9  710.28  5140.9  711.97
#Mann= 3 , 1 , 0
 4799.00    0.14       0  4998.5    0.05       0  5001.6    0.12       0
Bank Sta=4998.50,5001.60
Exp/Cntr=0.5,0.3

Type RM Length L Ch R = 1 ,14787.2,46,46,46
XS GIS Cut Line= 4
      1835200.95       769190.73      1835081.72       769063.30
      1835032.95       768906.99      1835012.38       768878.62
BEGIN DESCRIPTION:
Upstream Section of Bridge/Culvert/Weir
END DESCRIPTION:
#Sta/Elev= 30
  4773.2  711.65  4788.2  711.03  4863.2  706.96  4873.2  706.76  4888.2  705.57
  4893.2  705.56  4903.2  705.95  4908.2  705.78  4958.2   705.5  4973.2  704.82
  4988.2  702.08  4989.5  702.03    4991  699.63    5010  699.63  5011.5  703.58
  5025.1  706.06  5035.1  703.72  5040.1  704.24  5050.1  703.91  5055.1  704.18
  5065.1  704.12  5075.1  705.43  5085.1  704.06  5090.1  705.38    5111  706.04
    5121  706.01    5131   707.3    5136  707.62    5141  707.65  5146.5  710.94
#Mann= 3 , 1 , 0
 4773.20    0.14       0  4989.5    0.05       0  5011.5    0.12       0
#XS Ineff= 2 , 0
       0  4979.5     709  5021.5       0     709
Bank Sta=4989.50,5011.50
Exp/Cntr=0.5,0.3

Type RM Length L Ch R = 2 ,14764.2,,,
BEGIN DESCRIPTION:
Private Rd
Structure ID: NCF-0859
Approximate Survey Structure
END DESCRIPTION:
Bridge Culvert--1,0,-1,-1, 0
Deck Dist Width WeirC Skew NumUp NumDn MinLoCord MaxHiCord MaxSubmerge Is_Ogee
10,26,3,,43,43,,,0.95,0,1,1,,
  4773.2  4783.2  4788.2  4822.1  4863.2  4873.2  4888.2  4893.2  4903.2  4908.2
  4912.1  4922.1  4932.1  4947.7  4958.2  4968.2  4973.2  4978.2  4988.2  4989.5
    4991    5000    5010  5011.5  5025.1  5030.1  5035.1  5040.1  5050.1  5055.1
  5065.1  5075.1  5082.7  5085.1  5090.1    5106    5111    5121    5126    5131
    5136    5141  5146.5
  712.02  711.51   711.4  709.57  709.91  710.06  710.29  710.36  710.52  710.59
  710.65  711.07  711.86  711.97  711.98  711.98  711.98  711.99  711.99  711.99
  711.99     712  712.01  712.01  712.02  712.03  712.03  712.04  712.05  712.05
  712.06  712.07  712.08  712.05  711.99   711.8  711.74  711.62  711.56   711.5
  711.44  711.38  711.31
  712.02  711.51   711.4  709.56  707.33  707.13  705.94  705.93  706.32  706.15
  706.13  706.07  706.02  705.93  705.87  705.32  705.19  704.35  702.45   702.4
     700     700     700  703.95  706.43  705.33  704.09  704.61  704.28  704.55
  704.49   705.8  704.76  704.43  705.75  706.29  706.41  706.38  706.92  707.67
  707.99  708.02  711.31
  4773.2  4783.2  4788.2  4822.1  4863.2  4873.2  4888.2  4893.2  4903.2  4908.2
  4912.1  4922.1  4932.1  4947.7  4958.2  4968.2  4973.2  4978.2  4988.2  4989.5
    4991    5000    5010  5011.5  5025.1  5030.1  5035.1  5040.1  5050.1  5055.1
  5065.1  5075.1  5082.7  5085.1  5090.1    5106    5111    5121    5126    5131
    5136    5141  5146.5
  712.02  711.51   711.4  709.57  709.91  710.06  710.29  710.36  710.52  710.59
  710.65  711.07  711.86  711.97  711.98  711.98  711.98  711.99  711.99  711.99
  711.99     712  712.01  712.01  712.02  712.03  712.03  712.04  712.05  712.05
  712.06  712.07  712.08  712.05  711.99   711.8  711.74  711.62  711.56   711.5
  711.44  711.38  711.31
  711.89  711.38  711.27  709.43   707.2     707  705.81   705.8  706.19  706.02
     706  705.94  705.89   705.8  705.74  705.19  705.06  704.22  702.32  702.27
  699.87  699.87  699.87  703.82   706.3   705.2  703.96  704.48  704.15  704.42
  704.36  705.67  704.63   704.3  705.62  706.16  706.28  706.25  706.79  707.54
  707.86  707.89  711.18
BR Coef= 1 , 0 , 0 ,1.25, 0 ,,,0.8,-1,2,0,
Wspro=,,,, 1 ,,,, 0 ,,,, 0 ,,,,-1 ,-1 ,-1 , 0 , 0 , 0 , 0 , 0
Culvert=1,8.0,,26.0,0.015,0.2,1.0,1,2,700.00,4995.51,699.87,4995.51,Culvert #1  ,0,10
Culvert=1,8.0,,26.0,0.015,0.2,1.0,1,2,700.00,5004.51,699.87,5004.51,Culvert #2  ,0,10
BC Design=,, 0 ,, 0 ,,,,,,
BR U #Sta/Elev= 43
  4773.2  712.02  4783.2  711.51  4788.2   711.4  4822.1  709.56  4863.2  707.33
  4873.2  707.13  4888.2  705.94  4893.2  705.93  4903.2  706.32  4908.2  706.15
  4912.1  706.13  4922.1  706.07  4932.1  706.02  4947.7  705.93  4958.2  705.87
  4968.2  705.32  4973.2  705.19  4978.2  704.35  4988.2  702.45  4989.5   702.4
    4991     700    5000     700    5010     700  5011.5  703.95  5025.1  706.43
  5030.1  705.33  5035.1  704.09  5040.1  704.61  5050.1  704.28  5055.1  704.55
  5065.1  704.49  5075.1   705.8  5082.7  704.76  5085.1  704.43  5090.1  705.75
    5106  706.29    5111  706.41    5121  706.38    5126  706.92    5131  707.67
    5136  707.99    5141  708.02  5146.5  711.31
BR U #Mann= 3
 4773.20    0.14  4989.5    0.05  5011.5    0.12
BR U Banks=4989.50,5011.50
BR D #Sta/Elev= 43
  4773.2  711.89  4783.2  711.38  4788.2  711.27  4822.1  709.43  4863.2   707.2
  4873.2     707  4888.2  705.81  4893.2   705.8  4903.2  706.19  4908.2  706.02
  4912.1     706  4922.1  705.94  4932.1  705.89  4947.7   705.8  4958.2  705.74
  4968.2  705.19  4973.2  705.06  4978.2  704.22  4988.2  702.32  4989.5  702.27
    4991  699.87    5000  699.87    5010  699.87  5011.5  703.82  5025.1   706.3
  5030.1   705.2  5035.1  703.96  5040.1  704.48  5050.1  704.15  5055.1  704.42
  5065.1  704.36  5075.1  705.67  5082.7  704.63  5085.1   704.3  5090.1  705.62
    5106  706.16    5111  706.28    5121  706.25    5126  706.79    5131  707.54
    5136  707.86    5141  707.89  5146.5  711.18
BR D #Mann= 3
 4773.20    0.14  4989.5    0.05  5011.5    0.12
BR D Banks=4989.50,5011.50

Type RM Length L Ch R = 1 ,14741.2,313.8,313.8,313.8
XS GIS Cut Line= 4
      1835246.63       769185.31      1835127.40       769057.88
      1835078.63       768901.57      1835058.06       768873.20
BEGIN DESCRIPTION:
Downstream Section of Bridge/Culvert/Weir
END DESCRIPTION:
#Sta/Elev= 30
  4773.2  711.82  4788.2   711.2  4863.2  707.13  4873.2  706.93  4888.2  705.74
  4893.2  705.73  4903.2  706.12  4908.2  705.95  4958.2  705.67  4973.2  704.99
  4988.2  702.25  4989.5   702.2    4991   699.8    5010   699.8  5011.5  703.75
  5025.1  706.23  5035.1  703.89  5040.1  704.41  5050.1  704.08  5055.1  704.35
  5065.1  704.29  5075.1   705.6  5085.1  704.23  5090.1  705.55    5111  706.21
    5121  706.18    5131  707.47    5136  707.79    5141  707.82  5146.5  711.11
#Mann= 3 , 1 , 0
 4773.20    0.14       0  4989.5    0.05       0  5011.5    0.12       0
#XS Ineff= 2 , 0
       0  4979.5     708  5021.5       0     708
Bank Sta=4989.50,5011.50
Exp/Cntr=0.5,0.3

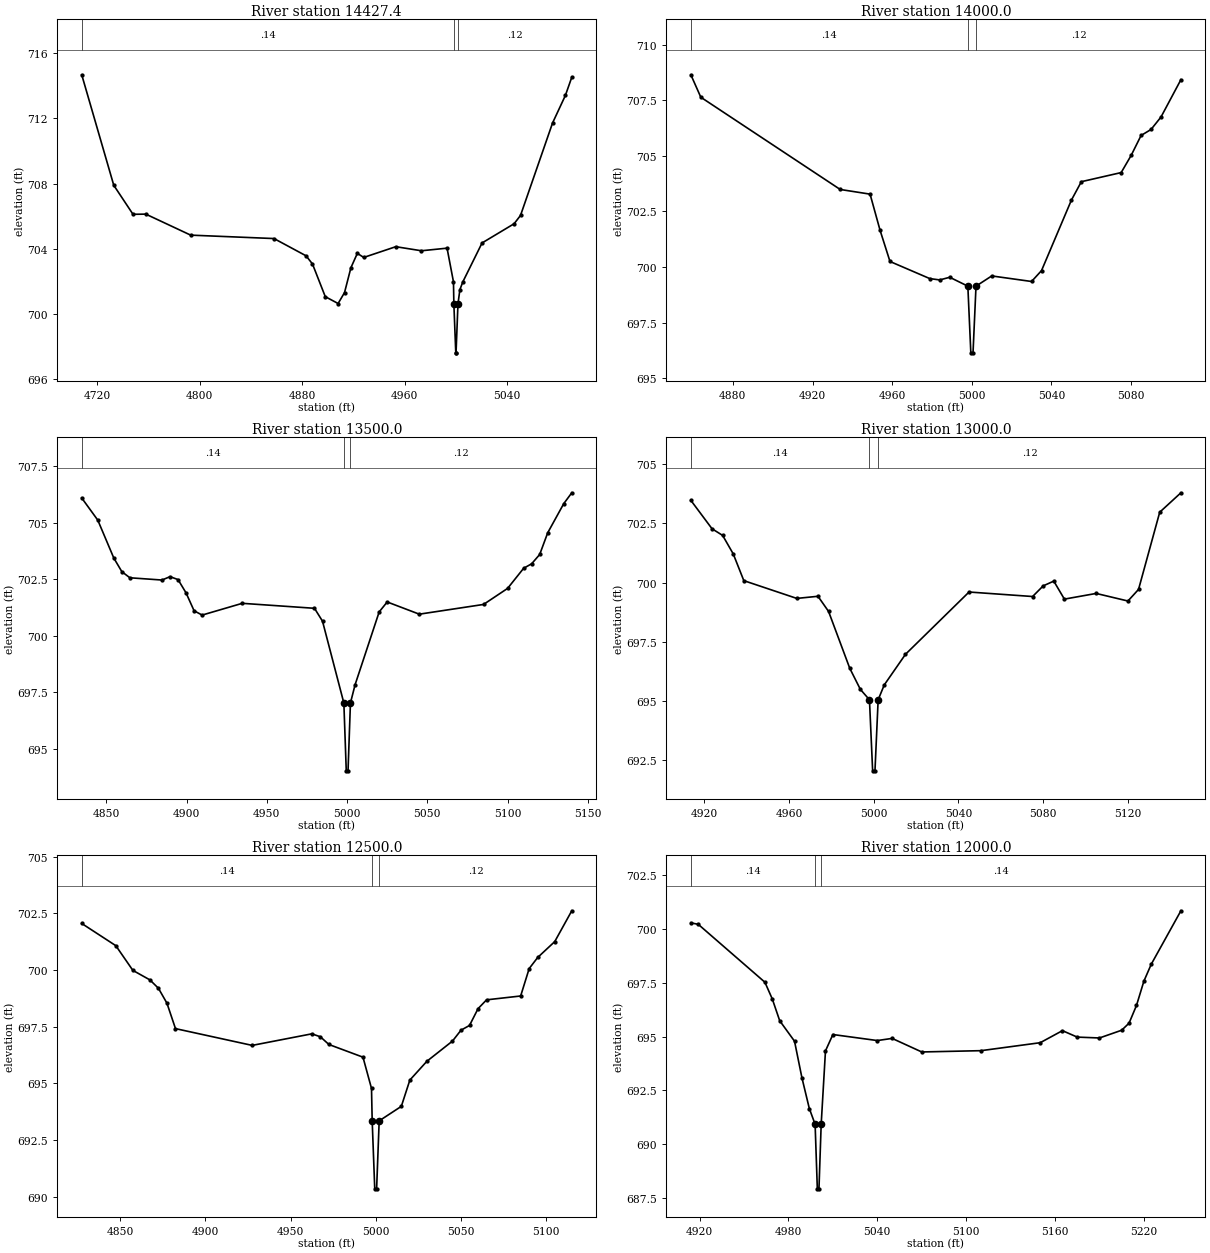
Type RM Length L Ch R = 1 ,14427.4,427.4,427.4,427.4
XS GIS Cut Line= 3
      1835469.26       769339.46      1835407.08       769048.76
      1835437.29       768969.29
BEGIN DESCRIPTION:
North Prong Creek 29.0
END DESCRIPTION:
#Sta/Elev= 30
  4708.1  714.68  4733.1  707.89  4748.1  706.11  4758.1  706.12  4793.1  704.83
  4858.1  704.62  4883.1  703.56  4888.1  703.06  4898.1  701.05  4908.1  700.63
  4913.1   701.3  4918.1  702.83  4923.1  703.71  4928.1  703.46  4953.1  704.12
  4973.1  703.87  4993.1  704.03  4998.1  701.96  4998.4   700.6  4999.9   697.6
  5000.1   697.6  5001.6   700.6  5003.1  701.48  5005.4  701.96  5020.4  704.35
  5045.4  705.53  5050.4  706.04  5075.4  711.72  5085.4  713.41  5090.4  714.53
#Mann= 3 , 1 , 0
 4708.10    0.14       0  4998.4    0.05       0  5001.6    0.12       0
Bank Sta=4998.40,5001.60
Exp/Cntr=0.3,0.1

Type RM Length L Ch R = 1 ,14000.0,500,500,500
XS GIS Cut Line= 3
      1835724.79       769318.69      1835733.51       769177.89
      1835721.35       769073.57
BEGIN DESCRIPTION:
North Prong Creek 28.0
END DESCRIPTION:
#Sta/Elev= 24
  4858.9  708.65  4863.9  707.64  4933.9  703.49  4948.9  703.28  4953.9  701.66
  4958.9  700.25  4978.9  699.48  4983.9  699.42  4988.9  699.54    4998  699.14
  4999.5  696.14  5000.6  696.14  5002.1  699.14    5010   699.6    5030  699.35
    5035  699.84    5050  703.01    5055  703.84    5075  704.25    5080  705.02
    5085  705.92    5090  706.19    5095  706.75    5105  708.43
#Mann= 3 , 1 , 0
 4858.90    0.14       0    4998    0.05       0  5002.1    0.12       0
Bank Sta=4998.00,5002.10
Exp/Cntr=0.3,0.1

Type RM Length L Ch R = 1 ,13500.0,500,500,500
XS GIS Cut Line= 3
      1836141.37       769370.04      1836167.87       769206.88
      1836163.28       769066.95
BEGIN DESCRIPTION:
North Prong Creek 27.0
END DESCRIPTION:
#Sta/Elev= 30
  4834.7  706.09  4844.7  705.11  4854.7  703.43  4859.7  702.83  4864.7  702.56
  4884.7  702.46  4889.7  702.61  4894.7  702.48  4899.7  701.89  4904.7   701.1
  4909.7  700.91  4934.7  701.43  4979.7  701.21  4984.7  700.64    4998  697.02
  4999.5  694.02  5000.6  694.02  5002.1  697.02    5005  697.83    5020  701.05
    5025  701.49    5045  700.95    5085  701.38    5100  702.09    5110  702.98
    5115  703.18    5120  703.59    5125  704.55    5135  705.84    5140  706.32
#Mann= 3 , 1 , 0
 4834.70    0.14       0    4998    0.05       0  5002.1    0.12       0
Bank Sta=4998.00,5002.10
Exp/Cntr=0.3,0.1

Type RM Length L Ch R = 1 ,13000.0,500,500,500
XS GIS Cut Line= 3
      1836463.53       769509.24      1836508.37       769435.51
      1836598.65       769322.03
BEGIN DESCRIPTION:
North Prong Creek 26.0
END DESCRIPTION:
#Sta/Elev= 26
  4913.7  703.47  4923.7  702.27  4928.7  701.99  4933.7  701.21  4938.7  700.08
  4963.7  699.33  4973.7  699.42  4978.7  698.78  4988.7  696.38  4993.7  695.49
    4998  695.05  4999.5  692.05  5000.6  692.05  5002.1  695.05    5005  695.68
    5015  696.97    5045   699.6    5075  699.41    5080  699.86    5085  700.06
    5090   699.3    5105  699.54    5120  699.22    5125  699.71    5135  702.97
    5145  703.79
#Mann= 3 , 1 , 0
 4913.70    0.14       0    4998    0.05       0  5002.1    0.12       0
Bank Sta=4998.00,5002.10
Exp/Cntr=0.3,0.1

Type RM Length L Ch R = 1 ,12500.0,500,500,500
XS GIS Cut Line= 3
      1836807.65       769771.73      1836914.81       769636.56
      1836974.54       769538.29
BEGIN DESCRIPTION:
North Prong Creek 25.0
END DESCRIPTION:
#Sta/Elev= 30
  4827.5  702.06  4847.5  701.08  4857.5  699.99  4867.5  699.57  4872.5   699.2
  4877.5  698.54  4882.5  697.42  4927.5  696.68  4962.5  697.19  4967.5  697.06
  4972.5  696.72  4992.5  696.16  4997.5  694.78  4997.9  693.35  4999.4  690.35
  5000.5  690.35    5002  693.35    5015  693.99    5020  695.15    5030  695.98
    5045  696.87    5050  697.35    5055  697.56    5060   698.3    5065  698.69
    5085  698.86    5090  700.07    5095  700.56    5105  701.26    5115  702.62
#Mann= 3 , 1 , 0
 4827.50    0.14       0  4997.9    0.05       0    5002    0.12       0
Bank Sta=4997.90,5002.00
Exp/Cntr=0.3,0.1

Type RM Length L Ch R = 1 ,12000.0,462.3,462.3,462.3
XS GIS Cut Line= 3
      1837182.34       770050.79      1837214.27       769971.05
      1837353.49       769769.45
BEGIN DESCRIPTION:
North Prong Creek 24.0
END DESCRIPTION:
#Sta/Elev= 28
  4914.1  700.29  4919.1  700.22  4964.1  697.53  4969.1  696.75  4974.1  695.74
  4984.1  694.79  4989.1  693.09  4994.1  691.66    4998  690.93  4999.5  687.93
  5000.6  687.93  5002.1  690.93    5005  694.34    5010   695.1    5040  694.82
    5050  694.92    5070  694.29    5110  694.35    5150  694.72    5165  695.28
    5175  694.98    5190  694.94    5205   695.3    5210  695.63    5215  696.45
    5220  697.58    5225  698.37    5245  700.85
#Mann= 3 , 1 , 0
 4914.10    0.14       0    4998    0.05       0  5002.1    0.14       0
Bank Sta=4998.00,5002.10
Exp/Cntr=0.3,0.1

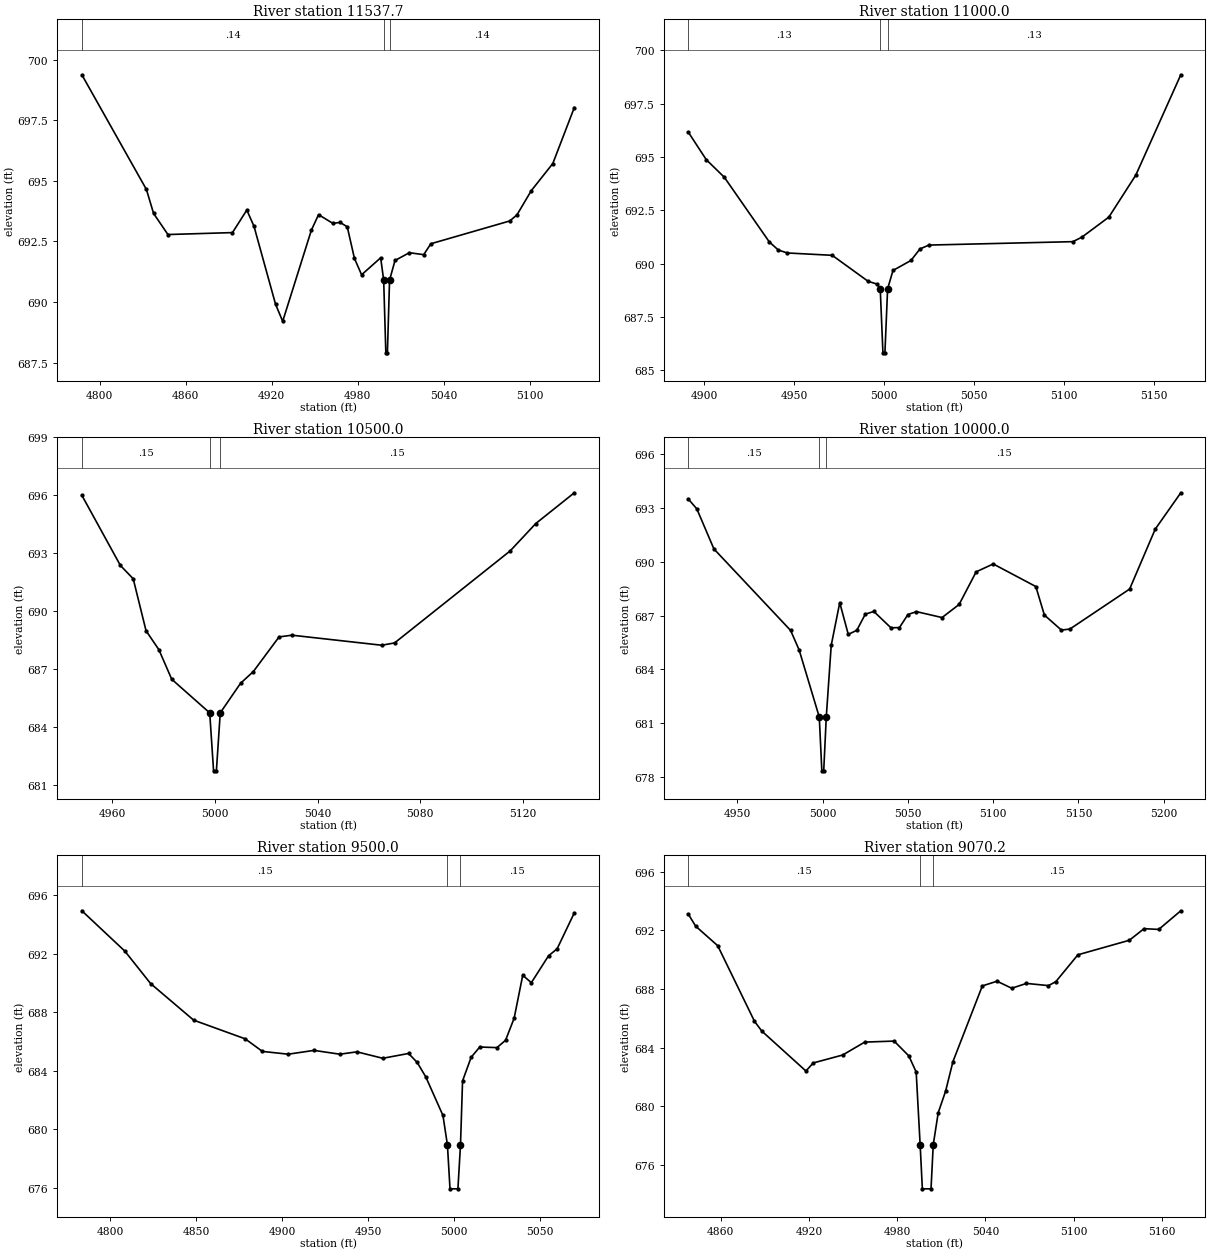
Type RM Length L Ch R = 1 ,11537.7,537.7,537.7,537.7
XS GIS Cut Line= 3
      1837389.09       770334.09      1837561.88       770217.72
      1837645.98       770112.14
BEGIN DESCRIPTION:
North Prong Creek 23.0
END DESCRIPTION:
#Sta/Elev= 30
  4787.6  699.37  4832.6  694.64  4837.6  693.65  4847.6  692.78  4892.6  692.86
  4902.6  693.79  4907.6  693.12  4922.6  689.91  4927.6   689.2  4947.6  692.96
  4952.6   693.6  4962.6  693.24  4967.6  693.28  4972.6   693.1  4977.6   691.8
  4982.6  691.12  4995.9  691.82    4998   690.9  4999.5   687.9  5000.6   687.9
  5002.1   690.9  5005.9  691.71  5015.9  692.03  5025.9  691.95  5030.9   692.4
  5085.9  693.34  5090.9  693.59  5100.9  694.59  5115.9  695.71  5130.9  698.02
#Mann= 3 , 1 , 0
 4787.60    0.14       0    4998    0.05       0  5002.1    0.14       0
Bank Sta=4998.00,5002.10
Exp/Cntr=0.3,0.1

Type RM Length L Ch R = 1 ,11000.0,500,500,500
XS GIS Cut Line= 3
      1837744.66       770737.19      1837796.81       770641.70
      1837890.81       770506.10
BEGIN DESCRIPTION:
North Prong Creek 22.0
END DESCRIPTION:
#Sta/Elev= 22
  4891.2  696.16  4901.2  694.87  4911.2  694.05  4936.2  691.02  4941.2  690.64
  4946.2   690.5  4971.2  690.39  4991.2  689.17  4996.2  689.04  4997.9  688.82
  4999.4  685.82  5000.5  685.82    5002  688.82    5005  689.68    5015  690.15
    5020  690.69    5025  690.87    5105  691.03    5110  691.24    5125  692.18
    5140  694.15    5165  698.85
#Mann= 3 , 1 , 0
 4891.20    0.13       0  4997.9    0.05       0    5002    0.13       0
Bank Sta=4997.90,5002.00
Exp/Cntr=0.3,0.1

Type RM Length L Ch R = 1 ,10500.0,500,500,500
XS GIS Cut Line= 3
      1838160.14       770880.56      1838156.19       770828.90
      1838166.98       770689.33
BEGIN DESCRIPTION:
North Prong Creek 21.0
END DESCRIPTION:
#Sta/Elev= 19
  4948.2     696  4963.2  692.37  4968.2  691.68  4973.2  688.99  4978.2  688.01
  4983.2  686.48    4998  684.74  4999.5  681.74  5000.6  681.74  5002.1  684.74
    5010  686.27    5015  686.88    5025  688.67    5030  688.76    5065  688.24
    5070  688.36    5115  693.12    5125  694.54    5140  696.13
#Mann= 3 , 1 , 0
 4948.20    0.15       0    4998    0.05       0  5002.1    0.15       0
Bank Sta=4998.00,5002.10
Exp/Cntr=0.3,0.1

Type RM Length L Ch R = 1 ,10000.0,500,500,500
XS GIS Cut Line= 3
      1838503.54       770762.28      1838536.90       770690.89
      1838479.02       770489.03
BEGIN DESCRIPTION:
North Prong Creek 20.0
END DESCRIPTION:
#Sta/Elev= 30
  4921.2   693.5  4926.2  692.95  4936.2  690.72  4981.2  686.17  4986.2  685.08
    4998  681.34  4999.5  678.34  5000.6  678.34  5002.1  681.34    5005  685.34
    5010  687.72    5015  685.95    5020  686.18    5025  687.08    5030  687.23
    5040  686.32    5045  686.33    5050  687.06    5055  687.22    5070  686.89
    5080  687.62    5090  689.44    5100  689.88    5125  688.62    5130  687.03
    5140  686.19    5145  686.25    5180  688.48    5195  691.82    5210  693.85
#Mann= 3 , 1 , 0
 4921.20    0.15       0    4998    0.05       0  5002.1    0.15       0
Bank Sta=4998.00,5002.10
Exp/Cntr=0.3,0.1

Type RM Length L Ch R = 1 ,9500.0,429.8,429.8,429.8
XS GIS Cut Line= 3
      1839007.11       770627.80      1838922.41       770428.66
      1838865.15       770388.39
BEGIN DESCRIPTION:
North Prong Creek 19.0
END DESCRIPTION:
#Sta/Elev= 30
  4783.6  694.95  4808.6  692.19  4823.6  689.97  4848.6  687.47  4878.6  686.19
  4888.6  685.33  4903.6  685.14  4918.6   685.4  4933.6  685.14  4943.6   685.3
  4958.6  684.86  4973.6  685.19  4978.6  684.58  4983.6  683.59  4993.6  680.95
  4996.2  678.93  4997.7  675.93  5002.3  675.93  5003.8  678.93    5005  683.31
    5010  684.93    5015  685.63    5025  685.59    5030  686.09    5035   687.6
    5040  690.54    5045  690.03    5055  691.87    5060  692.35    5070  694.81
#Mann= 3 , 1 , 0
 4783.60    0.15       0  4996.2    0.05       0  5003.8    0.15       0
Bank Sta=4996.20,5003.80
Exp/Cntr=0.3,0.1

Type RM Length L Ch R = 1 ,9070.2,80.9,80.9,80.9
XS GIS Cut Line= 3
      1839262.48       770219.82      1839127.82       770133.50
      1838964.36       770070.82
BEGIN DESCRIPTION:
North Prong Creek 18.0
END DESCRIPTION:
#Sta/Elev= 30
  4837.9   693.1  4842.9  692.28  4857.9  690.95  4882.9   685.8  4887.9  685.13
  4917.9  682.41  4922.9  682.96  4942.9   683.5  4957.9  684.38  4977.9  684.45
  4987.9  683.44  4992.9  682.34  4995.6  677.38  4997.1  674.38    5003  674.38
  5004.5  677.38  5007.9  679.57  5012.9  681.03  5017.9  683.05  5037.9  688.21
  5047.9  688.53  5057.9  688.05  5067.9  688.38  5082.9  688.23  5087.9   688.5
  5102.9  690.33  5137.9  691.32  5147.9  692.11  5157.9  692.06  5172.9  693.33
#Mann= 3 , 1 , 0
 4837.90    0.15       0  4995.6    0.05       0  5004.5    0.15       0
Bank Sta=4995.60,5004.50
Exp/Cntr=0.5,0.3

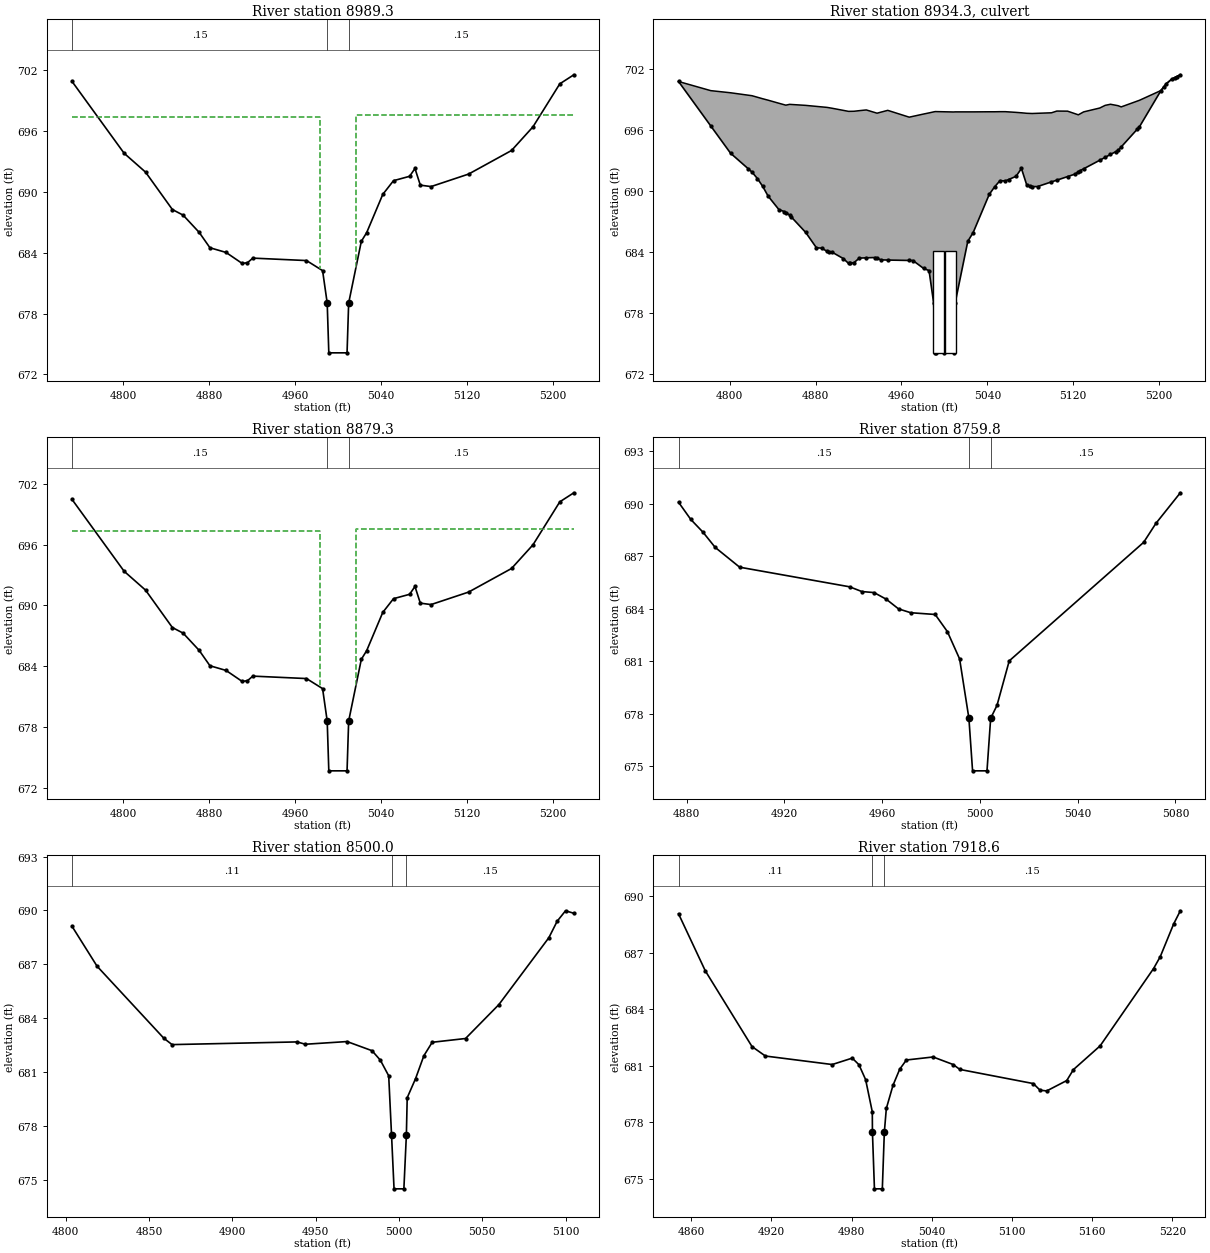
Type RM Length L Ch R = 1 ,8989.3,110,110,110
XS GIS Cut Line= 3
      1839303.56       770233.12      1839135.86       770050.99
      1838987.69       769888.18
BEGIN DESCRIPTION:
Upstream Section of Bridge/Culvert/Weir
END DESCRIPTION:
#Sta/Elev= 30
  4752.2  700.83  4800.7  693.77  4820.7  691.91  4845.7  688.23  4855.7  687.68
  4870.7  685.98  4880.7  684.47  4895.7  684.01  4910.7  682.93  4915.7     683
  4920.7  683.45  4970.7  683.21  4985.7  682.22    4990  679.03  4991.5  674.13
  5008.5  674.13    5010  679.03  5021.8   685.1  5026.8  685.96  5041.8  689.72
  5051.8  691.07  5066.8   691.5  5071.8  692.27  5076.8  690.63  5086.8  690.49
  5121.8  691.72  5161.8  694.04  5181.8  696.37  5206.8   700.6  5219.9  701.49
#Mann= 3 , 1 , 0
 4752.20    0.15       0    4990    0.05       0    5010    0.15       0
#XS Ineff= 2 , 0
       0 4983.33  697.29 5016.67       0  697.52
Bank Sta=4990.00,5010.00
Exp/Cntr=0.5,0.3

Type RM Length L Ch R = 2 ,8934.3,,,
BEGIN DESCRIPTION:
NC HWY 49 N
Structure ID: NCF-0860
Approximate Survey Structure
END DESCRIPTION:
Bridge Culvert--1,0,-1,-1, 0
Deck Dist Width WeirC Skew NumUp NumDn MinLoCord MaxHiCord MaxSubmerge Is_Ogee
10,90,3,, 59, 59,,,0.95,0,1,1,,
  4752.2  4782.2  4800.7  4820.7  4825.7  4830.7  4835.7  4845.7  4852.2  4855.7
  4870.7  4880.7  4885.7  4890.7  4895.7  4905.7  4910.7  4915.7  4920.7  4927.2
  4935.7  4937.2  4940.7  4947.2  4967.2  4970.7  4980.7  4985.7    4990  4991.5
  5008.5    5010  5021.8  5026.8  5041.8  5046.8  5051.8  5056.8  5066.8  5071.8
  5076.8  5081.8  5086.8  5099.8  5104.8  5114.8  5121.8  5124.8  5129.8  5144.8
  5149.8  5154.8  5161.8  5164.8  5181.8  5201.8  5206.8  5211.8  5219.9
   700.8   699.9  699.69   699.4  699.25   699.1  698.96  698.66  698.47  698.55
  698.45  698.35   698.3  698.25  698.16  697.96  697.86  697.87  697.93     698
  697.73  697.68  697.78  697.96  697.29  697.37   697.6  697.71  697.81  697.84
   697.8  697.81  697.81  697.81  697.82  697.82  697.83  697.83  697.76  697.72
  697.67  697.65  697.67  697.72  697.89  697.88  697.63  697.52  697.81  698.19
  698.45  698.56  698.42   698.3  698.95  699.91  700.58  701.03  701.46
   700.8  696.43  693.74  691.88  691.25  690.47  689.52   688.2   687.9  687.65
  685.95  684.44   684.4  684.08  683.98  683.38   682.9  682.97  683.42  683.45
  683.48  683.41  683.25  683.23  683.19  683.18   682.4  682.19     679   674.1
   674.1     679  685.07  685.93  689.69  690.43  691.04  691.01  691.47  692.24
   690.6  690.46  690.46  690.92  691.09  691.44  691.69   691.9  692.21  693.05
  693.33  693.62  694.01  694.36  696.34   699.9  700.57  701.02  701.46
  4752.2  4782.2  4800.7  4820.7  4825.7  4830.7  4835.7  4845.7  4852.2  4855.7
  4870.7  4880.7  4885.7  4890.7  4895.7  4905.7  4910.7  4915.7  4920.7  4927.2
  4935.7  4937.2  4940.7  4947.2  4967.2  4970.7  4980.7  4985.7    4990  4991.5
  5008.5    5010  5021.8  5026.8  5041.8  5046.8  5051.8  5056.8  5066.8  5071.8
  5076.8  5081.8  5086.8  5099.8  5104.8  5114.8  5121.8  5124.8  5129.8  5144.8
  5149.8  5154.8  5161.8  5164.8  5181.8  5201.8  5206.8  5211.8  5219.9
   700.8   699.9  699.69   699.4  699.25   699.1  698.96  698.66  698.47  698.55
  698.45  698.35   698.3  698.25  698.16  697.96  697.86  697.87  697.93     698
  697.73  697.68  697.78  697.96  697.29  697.37   697.6  697.71  697.81  697.84
   697.8  697.81  697.81  697.81  697.82  697.82  697.83  697.83  697.76  697.72
  697.67  697.65  697.67  697.72  697.89  697.88  697.63  697.52  697.81  698.19
  698.45  698.56  698.42   698.3  698.95  699.91  700.58  701.03  701.46
  700.35  695.98  693.29  691.43   690.8  690.02  689.07  687.75  687.45   687.2
   685.5  683.99  683.95  683.63  683.53  682.93  682.45  682.52  682.97     683
  683.03  682.96   682.8  682.78  682.74  682.73  681.95  681.74  678.55  673.65
  673.65  678.55  684.62  685.48  689.24  689.98  690.59  690.56  691.02  691.79
  690.15  690.01  690.01  690.47  690.64  690.99  691.24  691.45  691.76   692.6
  692.88  693.17  693.56  693.91  695.89  699.45  700.12  700.57  701.01
BR Coef= 1 , 0 , 0 ,1.25, 0 ,,,0.8,-1,2,0,
Wspro=,,,, 1 ,,,, 0 ,,,, 0 ,,,,-1 ,-1 ,-1 , 0 , 0 , 0 , 0 , 0
Culvert=2,10.0,10.0,90.0,0.015,0.4,1.0,8,1,674.10,4994.51,673.65,4994.51,Culvert #1  ,0,10
Culvert=2,10.0,10.0,90.0,0.015,0.4,1.0,8,1,674.10,5005.51,673.65,5005.51,Culvert #2  ,0,10
BC Design=,, 0 ,, 0 ,,,,,,
BR U #Sta/Elev= 74
  4752.2   700.8  4782.2  696.43  4800.7  693.74  4817.2  692.21  4820.7  691.88
  4825.7  691.25  4830.7  690.47  4835.7  689.52  4845.7   688.2  4850.7     688
  4852.2   687.9  4855.7  687.65  4857.2  687.48  4870.7  685.95  4880.7  684.44
  4885.7   684.4  4890.7  684.08  4892.2  684.05  4895.7  683.98  4905.7  683.38
  4910.7   682.9  4912.2  682.92  4915.7  682.97  4920.7  683.42  4927.2  683.45
  4935.7  683.48  4937.2  683.41  4940.7  683.25  4947.2  683.23  4967.2  683.19
  4970.7  683.18  4980.7   682.4  4985.7  682.19    4990     679  4991.5   674.1
  4992.2   674.1    5000   674.1  5008.5   674.1    5010     679  5021.8  685.07
  5026.8  685.93  5041.8  689.69  5046.8  690.43  5051.8  691.04  5056.8  691.01
  5059.8  691.15  5066.8  691.47  5071.8  692.24  5076.8   690.6  5079.8  690.52
  5081.8  690.46  5086.8  690.46  5099.8  690.92  5104.8  691.09  5114.8  691.44
  5121.8  691.69  5124.8   691.9  5126.8  692.04  5129.8  692.21  5144.8  693.05
  5149.8  693.33  5154.8  693.62  5159.8   693.9  5161.8  694.01  5164.8  694.36
  5179.8  696.11  5181.8  696.34  5201.8   699.9  5204.8   700.3  5206.8  700.57
  5211.8  701.02  5214.8  701.18  5216.8  701.29  5219.9  701.46
BR U #Mann= 3
 4752.20    0.15    4990    0.05    5010    0.15
BR U Banks=4990.00,5010.00
BR D #Sta/Elev= 74
  4752.2  700.35  4782.2  695.98  4800.7  693.29  4817.2  691.76  4820.7  691.43
  4825.7   690.8  4830.7  690.02  4835.7  689.07  4845.7  687.75  4850.7  687.55
  4852.2  687.45  4855.7   687.2  4857.2  687.03  4870.7   685.5  4880.7  683.99
  4885.7  683.95  4890.7  683.63  4892.2   683.6  4895.7  683.53  4905.7  682.93
  4910.7  682.45  4912.2  682.47  4915.7  682.52  4920.7  682.97  4927.2     683
  4935.7  683.03  4937.2  682.96  4940.7   682.8  4947.2  682.78  4967.2  682.74
  4970.7  682.73  4980.7  681.95  4985.7  681.74    4990  678.55  4991.5  673.65
  4992.2  673.65    5000  673.65  5008.5  673.65    5010  678.55  5021.8  684.62
  5026.8  685.48  5041.8  689.24  5046.8  689.98  5051.8  690.59  5056.8  690.56
  5059.8   690.7  5066.8  691.02  5071.8  691.79  5076.8  690.15  5079.8  690.07
  5081.8  690.01  5086.8  690.01  5099.8  690.47  5104.8  690.64  5114.8  690.99
  5121.8  691.24  5124.8  691.45  5126.8  691.59  5129.8  691.76  5144.8   692.6
  5149.8  692.88  5154.8  693.17  5159.8  693.45  5161.8  693.56  5164.8  693.91
  5179.8  695.66  5181.8  695.89  5201.8  699.45  5204.8  699.85  5206.8  700.12
  5211.8  700.57  5214.8  700.73  5216.8  700.84  5219.9  701.01
BR D #Mann= 3
 4752.20    0.15    4990    0.05    5010    0.15
BR D Banks=4990.00,5010.00

Type RM Length L Ch R = 1 ,8879.3,119.5,119.5,119.5
XS GIS Cut Line= 3
      1839358.46       770137.80      1839190.76       769955.67
      1839042.59       769792.86
BEGIN DESCRIPTION:
Downstream Section of Bridge/Culvert/Weir
END DESCRIPTION:
#Sta/Elev= 30
  4752.2  700.43  4800.7  693.37  4820.7  691.51  4845.7  687.83  4855.7  687.28
  4870.7  685.58  4880.7  684.07  4895.7  683.61  4910.7  682.53  4915.7   682.6
  4920.7  683.05  4970.7  682.81  4985.7  681.82    4990  678.63  4991.5  673.73
  5008.5  673.73    5010  678.63  5021.8   684.7  5026.8  685.56  5041.8  689.32
  5051.8  690.67  5066.8   691.1  5071.8  691.87  5076.8  690.23  5086.8  690.09
  5121.8  691.32  5161.8  693.64  5181.8  695.97  5206.8   700.2  5219.9  701.09
#Mann= 3 , 1 , 0
 4752.20    0.15       0    4990    0.05       0    5010    0.15       0
#XS Ineff= 2 , 0
       0 4983.33  697.29 5016.67       0  697.52
Bank Sta=4990.00,5010.00
Exp/Cntr=0.5,0.3

Type RM Length L Ch R = 1 ,8759.8,259.8,259.8,259.8
XS GIS Cut Line= 3
      1839337.58       769885.20      1839221.01       769839.23
      1839151.47       769799.68
BEGIN DESCRIPTION:
North Prong Creek 17.5
END DESCRIPTION:
#Sta/Elev= 23
  4876.7  690.09  4881.7  689.11  4886.7  688.38  4891.7  687.51  4901.7  686.38
  4946.7  685.26  4951.7  684.99  4956.7  684.93  4961.7  684.55  4966.7     684
  4971.7  683.78  4981.7  683.68  4986.7   682.7  4991.7  681.14  4995.5  677.75
    4997  674.75  5002.9  674.75  5004.4  677.75    5007  678.49    5012  681.03
    5067   687.8    5072  688.88    5082  690.63
#Mann= 3 , 1 , 0
 4876.70    0.15       0  4995.5    0.05       0  5004.4    0.15       0
Bank Sta=4995.50,5004.40
Exp/Cntr=0.3,0.1

Type RM Length L Ch R = 1 ,8500.0,581.4,581.4,581.4
XS GIS Cut Line= 3
      1839495.20       769721.59      1839327.82       769619.42
      1839223.46       769607.82
BEGIN DESCRIPTION:
North Prong Creek 17.0
END DESCRIPTION:
#Sta/Elev= 24
  4803.9  689.11  4818.9  686.89  4858.9  682.88  4863.9  682.52  4938.9  682.67
  4943.9  682.54  4968.9  682.69  4983.9  682.18  4988.9  681.65  4993.9  680.78
  4995.6  677.48  4997.1  674.48    5003  674.48  5004.5  677.48    5005  679.56
    5010  680.62    5015   681.9    5020  682.65    5040  682.86    5060  684.75
    5090  688.48    5095   689.4    5100  689.98    5105  689.84
#Mann= 3 , 1 , 0
 4803.90    0.11       0  4995.6    0.05       0  5004.5    0.15       0
Bank Sta=4995.60,5004.50
Exp/Cntr=0.3,0.1

Type RM Length L Ch R = 1 ,7918.6,418.6,418.6,418.6
XS GIS Cut Line= 3
      1839810.19       769188.55      1839660.20       769177.12
      1839439.32       769133.91
BEGIN DESCRIPTION:
North Prong Creek 16.0
END DESCRIPTION:
#Sta/Elev= 30
  4850.5  689.06  4870.5  686.04  4905.5  682.02  4915.5  681.52  4965.5  681.07
  4980.5  681.41  4985.5  681.06  4990.5  680.27  4995.5  678.56  4995.6  677.48
  4997.1  674.48    5003  674.48  5004.5  677.48    5006  678.74    5011  679.97
    5016  680.82    5021  681.31    5041  681.47    5056  681.07    5061  680.81
    5116  680.06    5121  679.71    5126  679.67    5141  680.22    5146   680.8
    5166  682.06    5206  686.16    5211  686.79    5221  688.52    5226  689.22
#Mann= 3 , 1 , 0
 4850.50    0.11       0  4995.6    0.05       0  5004.5    0.15       0
Bank Sta=4995.60,5004.50
Exp/Cntr=0.3,0.1