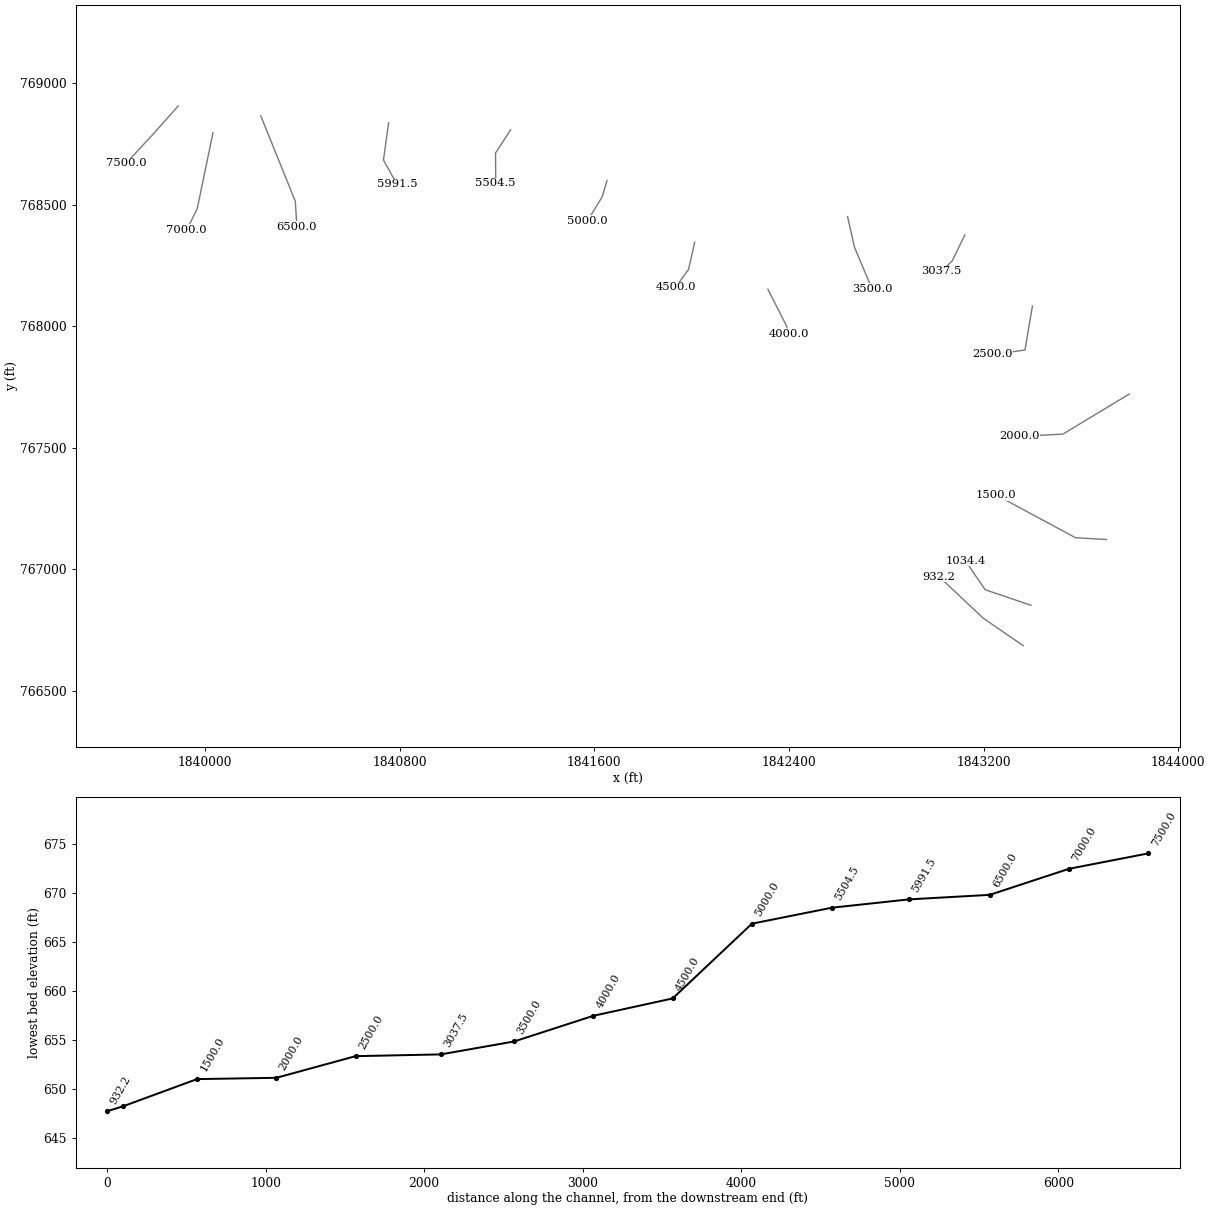
HEC-RAS study NORTH PRONG CREEK.PRJ: North Prong Creek

--- NORTH PRONG CREEK.g01 (geometry) --- (continued)

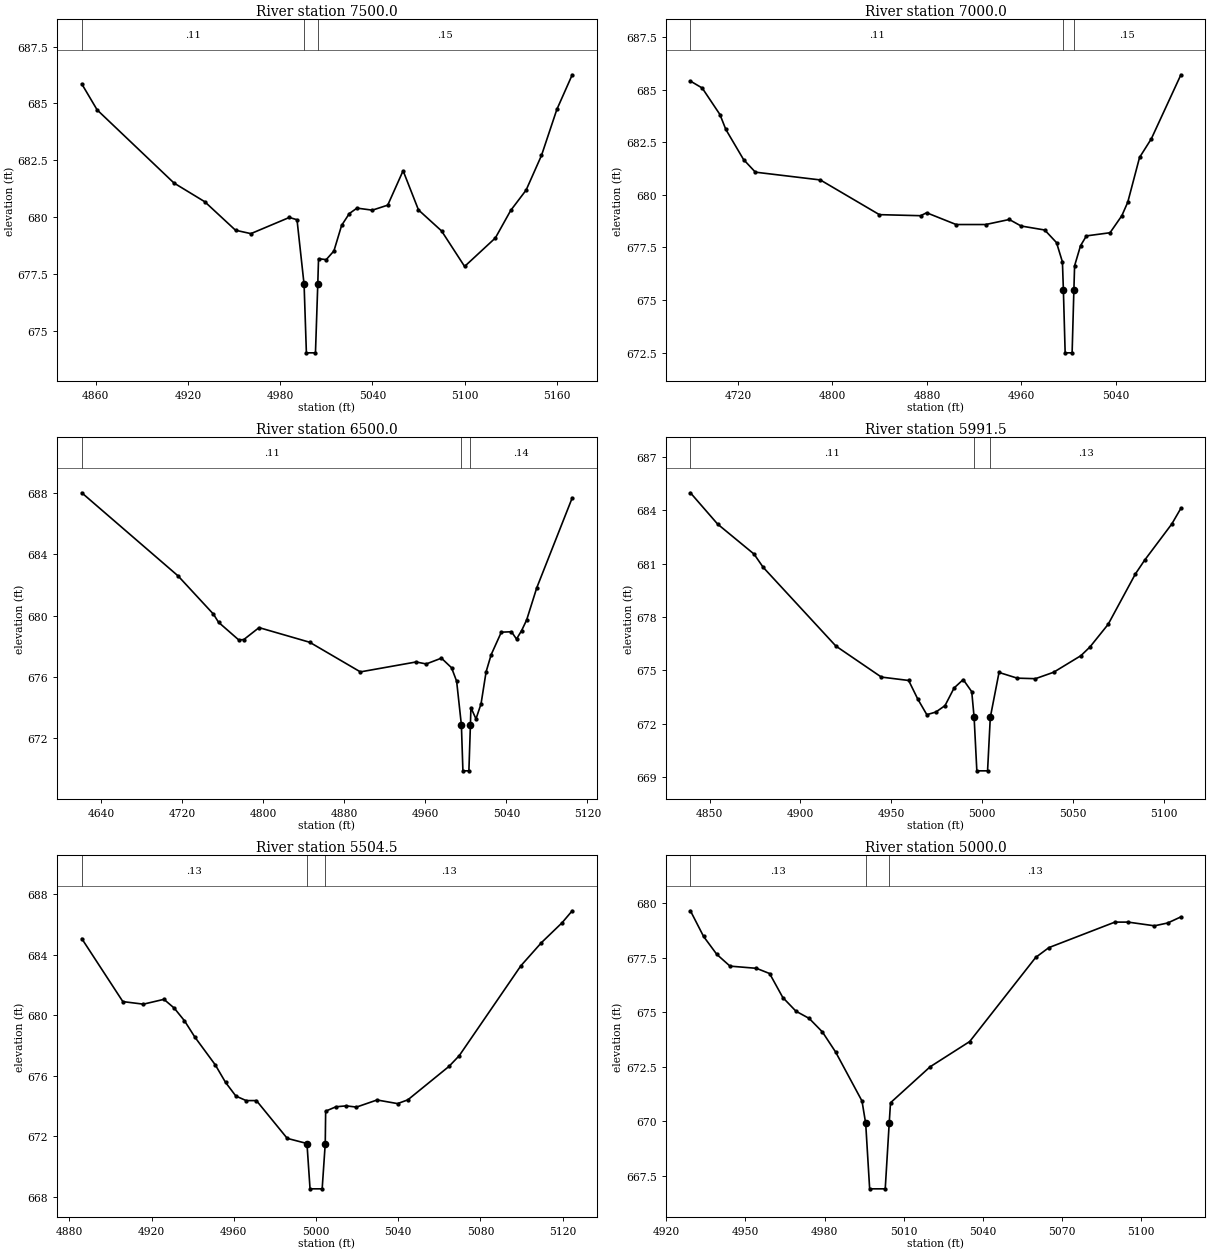
Type RM Length L Ch R = 1 ,7500.0,500,500,500
XS GIS Cut Line= 3
      1839888.84       768905.06      1839789.85       768793.69
      1839674.22       768669.08
BEGIN DESCRIPTION:
North Prong Creek 15.0
END DESCRIPTION:
#Sta/Elev= 30
    4851  685.86    4861  684.72    4911  681.51    4931  680.69    4951  679.44
    4961  679.29    4986     680    4991   679.9  4995.6  677.06  4997.1  674.06
    5003  674.06  5004.5  677.06    5005  678.19    5010  678.15    5015  678.53
    5020  679.65    5025  680.17    5030  680.41    5040  680.32    5050  680.54
    5060  682.05    5070  680.33    5085  679.41    5100  677.85    5120   679.1
    5130  680.31    5140   681.2    5150  682.72    5160  684.74    5170  686.26
#Mann= 3 , 1 , 0
 4851.00    0.11       0  4995.6    0.05       0  5004.5    0.15       0
Bank Sta=4995.60,5004.50
Exp/Cntr=0.3,0.1

Type RM Length L Ch R = 1 ,7000.0,500,500,500
XS GIS Cut Line= 3
      1840032.01       768795.28      1839966.97       768481.66
      1839924.23       768396.82
BEGIN DESCRIPTION:
North Prong Creek 14.0
END DESCRIPTION:
#Sta/Elev= 30
  4679.7  685.41  4689.7  685.08  4704.7  683.82  4709.7  683.11  4724.7  681.68
  4734.7  681.08  4789.7  680.71  4839.7  679.06  4874.7  679.01  4879.7  679.15
  4904.7  678.59  4929.7  678.59  4949.7  678.83  4959.7  678.52  4979.7  678.33
  4989.7  677.73  4994.7  676.81  4995.5  675.49    4997  672.49  5002.9  672.49
  5004.4  675.49    5005  676.63    5010  677.58    5015  678.05    5035   678.2
    5045  679.01    5050  679.65    5060  681.78    5070  682.67    5095  685.71
#Mann= 3 , 1 , 0
 4679.70    0.11       0  4995.5    0.05       0  5004.4    0.15       0
Bank Sta=4995.50,5004.40
Exp/Cntr=0.3,0.1

Type RM Length L Ch R = 1 ,6500.0,508.5,508.5,508.5
XS GIS Cut Line= 3
      1840228.55       768864.61      1840370.58       768513.12
      1840376.90       768408.31
BEGIN DESCRIPTION:
North Prong Creek 13.0
END DESCRIPTION:
#Sta/Elev= 30
  4620.9  688.04  4715.9   682.6  4750.9  680.09  4755.9  679.56  4775.9   678.4
  4780.9  678.43  4795.9  679.21  4845.9  678.25  4895.9  676.31  4950.9  676.96
  4960.9  676.83  4975.9  677.21  4985.9  676.58  4990.9   675.7  4995.6  672.83
  4997.1  669.83    5003  669.83  5004.5  672.83    5005  673.97    5010  673.23
    5015  674.22    5020  676.32    5025  677.44    5035  678.91    5045  678.94
    5050  678.46    5055  679.01    5060  679.71    5070  681.82    5105  687.71
#Mann= 3 , 1 , 0
 4620.90    0.11       0  4995.6    0.05       0  5004.5    0.14       0
Bank Sta=4995.60,5004.50
Exp/Cntr=0.3,0.1

Type RM Length L Ch R = 1 ,5991.5,487,487,487
XS GIS Cut Line= 3
      1840754.16       768836.31      1840732.93       768683.05
      1840788.66       768582.49
BEGIN DESCRIPTION:
North Prong Creek 12.0
END DESCRIPTION:
#Sta/Elev= 29
  4839.5  684.97  4854.5  683.21  4874.5  681.53  4879.5  680.79  4919.5  676.37
  4944.5  674.63  4959.5  674.44  4964.5   673.4  4969.5  672.52  4974.5  672.67
  4979.5  673.03  4984.5  674.02  4989.5  674.49  4994.2  673.81  4995.5  672.37
    4997  669.37  5002.9  669.37  5004.4  672.37  5009.2  674.89  5019.2  674.57
  5029.2  674.54  5039.2   674.9  5054.2  675.83  5059.2  676.32  5069.2  677.59
  5084.2  680.42  5089.2  681.18  5104.2  683.22  5109.2   684.1
#Mann= 3 , 1 , 0
 4839.50    0.11       0  4995.5    0.05       0  5004.4    0.13       0
Bank Sta=4995.50,5004.40
Exp/Cntr=0.3,0.1

Type RM Length L Ch R = 1 ,5504.5,504.5,504.5,504.5
XS GIS Cut Line= 3
      1841255.86       768807.28      1841193.74       768712.03
      1841194.57       768587.05
BEGIN DESCRIPTION:
North Prong Creek 11.0
END DESCRIPTION:
#Sta/Elev= 30
    4886  685.08    4906  680.91    4916  680.74    4926  681.06    4931  680.48
    4936  679.64    4941  678.57    4951  676.72    4956  675.56    4961  674.66
    4966  674.36    4971  674.36    4986  671.86  4995.6  671.52  4997.1  668.52
    5003  668.52  5004.5  671.52  5004.7  673.66  5009.7  673.95  5014.7  674.01
  5019.7  673.93  5029.7   674.4  5039.7  674.16  5044.7  674.41  5064.7  676.62
  5069.7  677.33  5099.7  683.28  5109.7  684.81  5119.7  686.12  5124.7  686.92
#Mann= 3 , 1 , 0
 4886.00    0.13       0  4995.6    0.05       0  5004.5    0.13       0
Bank Sta=4995.60,5004.50
Exp/Cntr=0.3,0.1

Type RM Length L Ch R = 1 ,5000.0,500,500,500
XS GIS Cut Line= 3
      1841652.15       768599.00      1841631.86       768531.17
      1841571.88       768433.05
BEGIN DESCRIPTION:
North Prong Creek 10.0
END DESCRIPTION:
#Sta/Elev= 26
  4929.2  679.65  4934.2  678.47  4939.2  677.65  4944.2  677.11  4954.2  677.01
  4959.2  676.77  4964.2  675.67  4969.2  675.04  4974.2  674.71  4979.2  674.09
  4984.2  673.17  4994.2  670.92  4995.6  669.89  4997.1  666.89    5003  666.89
  5004.5  669.89    5005  670.84    5020  672.49    5035  673.65    5060  677.51
    5065  677.96    5090  679.13    5095  679.13    5105  678.96    5110  679.09
    5115  679.37
#Mann= 3 , 1 , 0
 4929.20    0.13       0  4995.6    0.05       0  5004.5    0.13       0
Bank Sta=4995.60,5004.50
Exp/Cntr=0.3,0.1

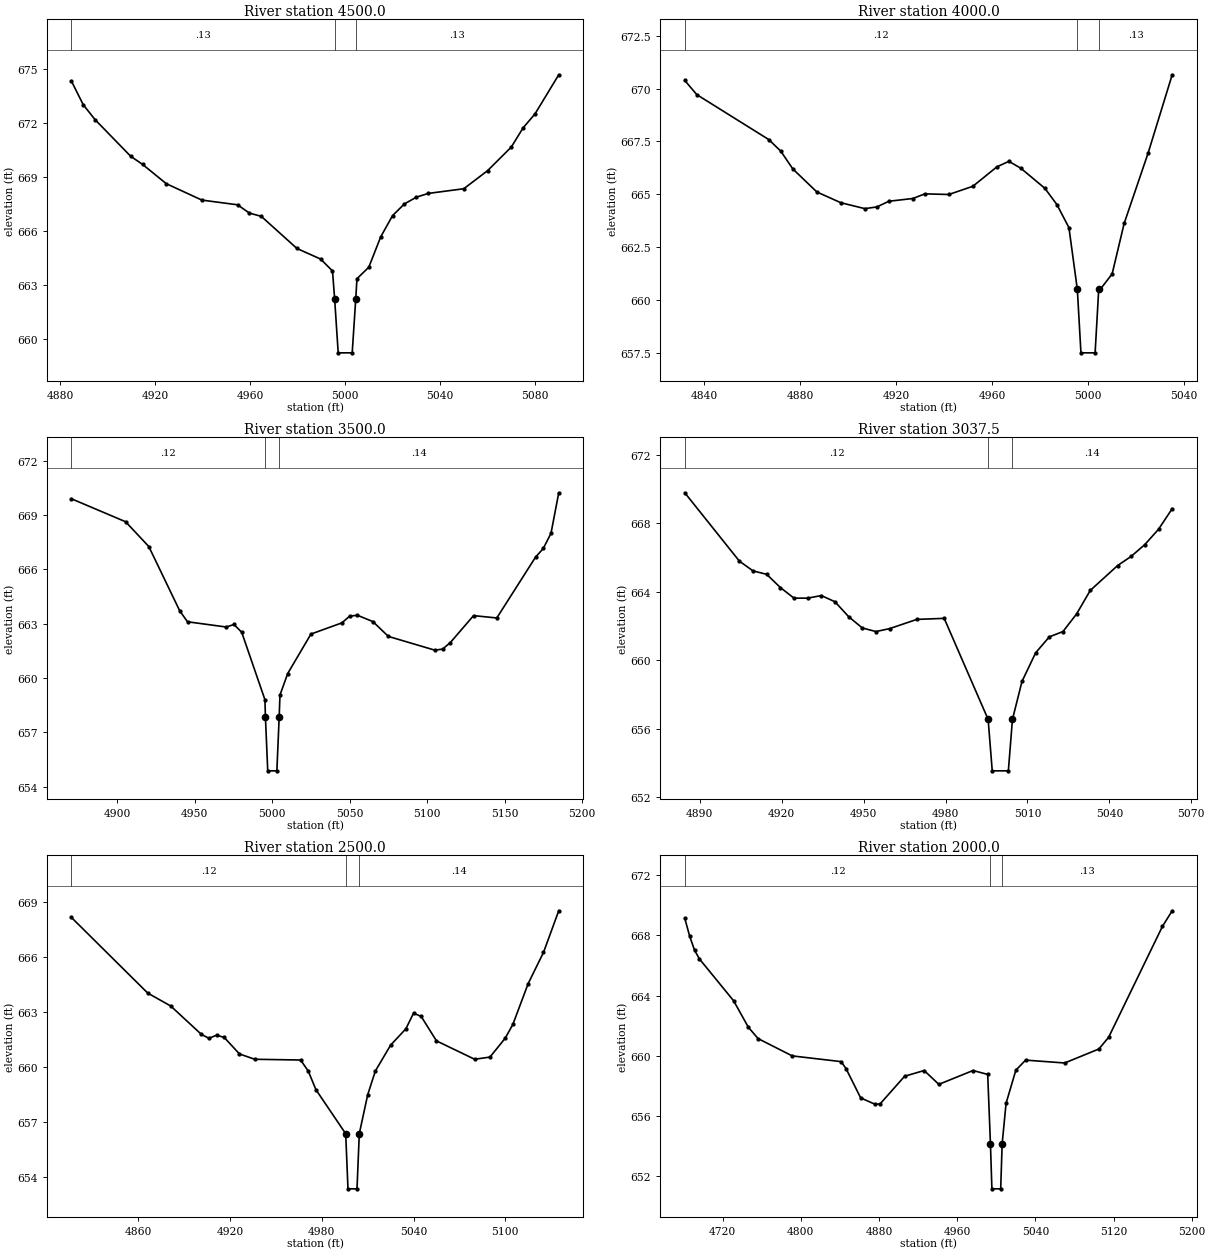
Type RM Length L Ch R = 1 ,4500.0,500,500,500
XS GIS Cut Line= 3
      1842012.46       768345.00      1841987.03       768232.54
      1841933.90       768159.90
BEGIN DESCRIPTION:
North Prong Creek 9.0
END DESCRIPTION:
#Sta/Elev= 30
  4884.7  674.34  4889.7  673.02  4894.7  672.19  4909.7  670.16  4914.7  669.71
  4924.7  668.64  4939.7  667.73  4954.7  667.47  4959.7  667.01  4964.7  666.83
  4979.7  665.05  4989.7  664.46  4994.7   663.8  4995.6  662.26  4997.1  659.26
    5003  659.26  5004.5  662.26    5005  663.37    5010  664.01    5015  665.69
    5020  666.87    5025  667.52    5030  667.89    5035   668.1    5050  668.36
    5060  669.36    5070  670.67    5075  671.74    5080  672.51    5090  674.68
#Mann= 3 , 1 , 0
 4884.70    0.13       0  4995.6    0.05       0  5004.5    0.13       0
Bank Sta=4995.60,5004.50
Exp/Cntr=0.3,0.1

Type RM Length L Ch R = 1 ,4000.0,500,500,500
XS GIS Cut Line= 3
      1842313.38       768151.94      1842389.36       768002.10
      1842398.81       767968.40
BEGIN DESCRIPTION:
North Prong Creek 8.0
END DESCRIPTION:
#Sta/Elev= 29
    4832  670.39    4837  669.72    4867  667.59    4872  667.04    4877   666.2
    4887  665.11    4897   664.6    4907  664.32    4912   664.4    4917  664.67
    4927   664.8    4932  665.02    4942  664.99    4952  665.38    4962   666.3
    4967  666.56    4972  666.23    4982  665.28    4987  664.51    4992  663.42
  4995.5  660.49    4997  657.49  5002.9  657.49  5004.4  660.49    5005  660.49
    5010  661.23    5015  663.62    5025  666.96    5035  670.66
#Mann= 3 , 1 , 0
 4832.00    0.12       0  4995.5    0.05       0  5004.4    0.13       0
Bank Sta=4995.50,5004.40
Exp/Cntr=0.3,0.1

Type RM Length L Ch R = 1 ,3500.0,462.5,462.5,462.5
XS GIS Cut Line= 3
      1842641.02       768450.48      1842669.55       768323.95
      1842741.61       768153.57
BEGIN DESCRIPTION:
North Prong Creek 7.0
END DESCRIPTION:
#Sta/Elev= 30
  4870.3  669.91  4905.3  668.64  4920.3  667.27  4940.3  663.71  4945.3  663.11
  4970.3  662.82  4975.3  662.96  4980.3  662.53  4995.3   658.8  4995.6  657.87
  4997.1  654.87    5003  654.87  5004.5  657.87    5005  659.06    5010  660.25
    5025  662.43    5045  663.05    5050  663.42    5055  663.47    5065  663.12
    5075   662.3    5105  661.54    5110   661.6    5115  661.96    5130  663.45
    5145  663.32    5170  666.68    5175  667.16    5180     668    5185  670.24
#Mann= 3 , 1 , 0
 4870.30    0.12       0  4995.6    0.05       0  5004.5    0.14       0
Bank Sta=4995.60,5004.50
Exp/Cntr=0.3,0.1

Type RM Length L Ch R = 1 ,3037.5,537.5,537.5,537.5
XS GIS Cut Line= 3
      1843123.16       768374.78      1843071.24       768268.31
      1843028.45       768226.19
BEGIN DESCRIPTION:
North Prong Creek 6.0
END DESCRIPTION:
#Sta/Elev= 30
  4884.5  669.78  4904.5  665.79  4909.5  665.22  4914.5  665.02  4919.5  664.25
  4924.5  663.63  4929.5  663.63  4934.5  663.78  4939.5  663.42  4944.5  662.55
  4949.5  661.89  4954.5  661.68  4959.5  661.85  4969.5  662.39  4979.5  662.45
  4995.6  656.55  4997.1  653.55    5003  653.55  5004.5  656.55    5008  658.77
    5013  660.44    5018  661.37    5023  661.68    5028  662.71    5033  664.08
    5043  665.53    5048  666.07    5053  666.76    5058  667.65    5063  668.85
#Mann= 3 , 1 , 0
 4884.50    0.12       0  4995.6    0.05       0  5004.5    0.14       0
Bank Sta=4995.60,5004.50
Exp/Cntr=0.3,0.1

Type RM Length L Ch R = 1 ,2500.0,500,500,500
XS GIS Cut Line= 3
      1843401.15       768083.02      1843370.39       767901.71
      1843236.64       767883.43
BEGIN DESCRIPTION:
North Prong Creek 5.0
END DESCRIPTION:
#Sta/Elev= 30
  4816.1  668.14  4866.1  664.02  4881.1  663.32  4901.1  661.78  4906.1  661.56
  4911.1  661.73  4916.1  661.61  4926.1  660.71  4936.1  660.42  4966.1  660.38
  4971.1  659.78  4976.1  658.77  4995.6  656.37  4997.1  653.37    5003  653.37
  5004.5  656.37    5010  658.49    5015  659.78    5025  661.19    5035  662.08
    5040  662.93    5045  662.75    5055  661.42    5080  660.42    5090  660.54
    5100  661.57    5105  662.32    5115  664.54    5125  666.23    5135   668.5
#Mann= 3 , 1 , 0
 4816.10    0.12       0  4995.6    0.05       0  5004.5    0.14       0
Bank Sta=4995.60,5004.50
Exp/Cntr=0.3,0.1

Type RM Length L Ch R = 1 ,2000.0,500,500,500
XS GIS Cut Line= 3
      1843799.51       767721.06      1843526.72       767556.08
      1843346.98       767546.43
BEGIN DESCRIPTION:
North Prong Creek 4.0
END DESCRIPTION:
#Sta/Elev= 30
  4681.2  669.13  4686.2  667.94  4691.2  667.01  4696.2  666.43  4731.2  663.65
  4746.2   661.9  4756.2  661.14  4791.2  659.99  4841.2  659.61  4846.2  659.15
  4861.2   657.2  4876.2  656.77  4881.2  656.81  4906.2  658.64  4926.2  659.02
  4941.2   658.1  4976.2  659.02  4991.2  658.76    4994  654.16  4995.5  651.16
  5004.5  651.16    5006  654.16    5010  656.84    5020  659.04    5030  659.71
    5070  659.52    5105  660.45    5115  661.23    5170  668.59    5180  669.63
#Mann= 3 , 1 , 0
 4681.20    0.12       0    4994    0.05       0    5006    0.13       0
Bank Sta=4994.00,5006.00
Exp/Cntr=0.3,0.1

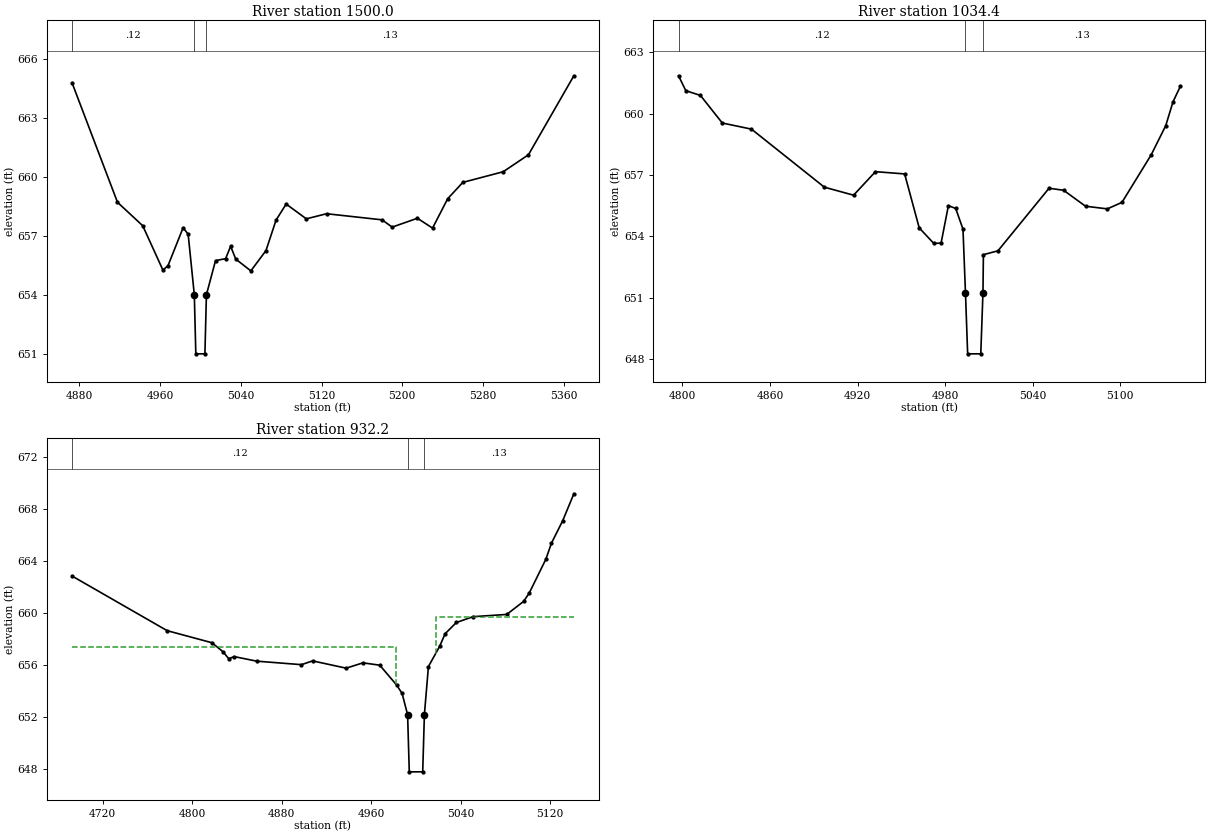
Type RM Length L Ch R = 1 ,1500.0,465.6,465.6,465.6
XS GIS Cut Line= 3
      1843704.63       767122.49      1843577.77       767130.05
      1843252.12       767305.72
BEGIN DESCRIPTION:
North Prong Creek 3.0
END DESCRIPTION:
#Sta/Elev= 30
  4872.9  664.78  4917.9  658.72  4942.9  657.53  4962.9  655.28  4967.9   655.5
  4982.9  657.43  4987.9   657.1    4994  654.03  4995.5  651.03  5004.5  651.03
    5006  654.03    5015  655.76    5025  655.86    5030  656.49    5035  655.84
    5050  655.24    5065  656.27    5075  657.82    5085  658.63    5105  657.88
    5125  658.14    5180  657.83    5190  657.46    5215  657.91    5230  657.41
    5245   658.9    5260  659.73    5300  660.27    5325  661.13    5370  665.14
#Mann= 3 , 1 , 0
 4872.90    0.12       0    4994    0.05       0    5006    0.13       0
Bank Sta=4994.00,5006.00
Exp/Cntr=0.3,0.1

Type RM Length L Ch R = 1 ,1034.4,102.2,102.2,102.2
XS GIS Cut Line= 3
      1843394.93       766852.28      1843206.45       766916.21
      1843124.99       767036.14
BEGIN DESCRIPTION:
North Prong Creek 2.0
END DESCRIPTION:
#Sta/Elev= 30
  4797.3  661.86  4802.3  661.13  4812.3   660.9  4827.3  659.55  4847.3  659.25
  4897.3  656.41  4917.3  656.02  4932.3  657.17  4952.3  657.06  4962.3  654.42
  4972.3  653.66  4977.3  653.68  4982.3  655.51  4987.3  655.37  4992.3  654.36
    4994  651.26  4995.5  648.26  5004.5  648.26    5006  651.26  5006.3  653.11
  5016.3   653.3  5051.3  656.36  5061.3  656.26  5076.3  655.48  5091.3  655.35
  5101.3  655.67  5121.3  657.99  5131.3  659.42  5136.3  660.59  5141.3  661.34
#Mann= 3 , 1 , 0
 4797.30    0.12       0    4994    0.05       0    5006    0.13       0
Bank Sta=4994.00,5006.00
Exp/Cntr=0.5,0.3

Type RM Length L Ch R = 1 ,932.2,41,41,41
XS GIS Cut Line= 3
      1843363.23       766685.98      1843198.76       766799.21
      1843017.51       766969.67
BEGIN DESCRIPTION:
Upstream Section of Bridge/Culvert/Weir
END DESCRIPTION:
#Sta/Elev= 30
  4692.6  662.84  4777.6  658.63  4817.6   657.7  4827.6     657  4832.6  656.47
  4837.6  656.63  4857.6  656.28  4897.6  656.01  4907.6   656.3  4937.6  655.74
  4952.6  656.15  4967.6  655.97  4982.6  654.45  4987.6  653.79  4992.5  652.15
    4994  647.75    5006  647.75  5007.5  652.15  5011.1  655.86  5021.1  657.42
  5026.1   658.4  5036.1  659.26  5051.1  659.71  5081.1  659.88  5096.1  660.88
  5101.1  661.51  5116.1  664.14  5121.1  665.38  5131.1   667.1  5141.1  669.18
#Mann= 3 , 1 , 0
 4692.60    0.12       0  4992.5    0.05       0  5007.5    0.13       0
#XS Ineff= 2 , 0
       0  4982.5  657.34  5017.5       0  659.65
Bank Sta=4992.50,5007.50
Exp/Cntr=0.5,0.3