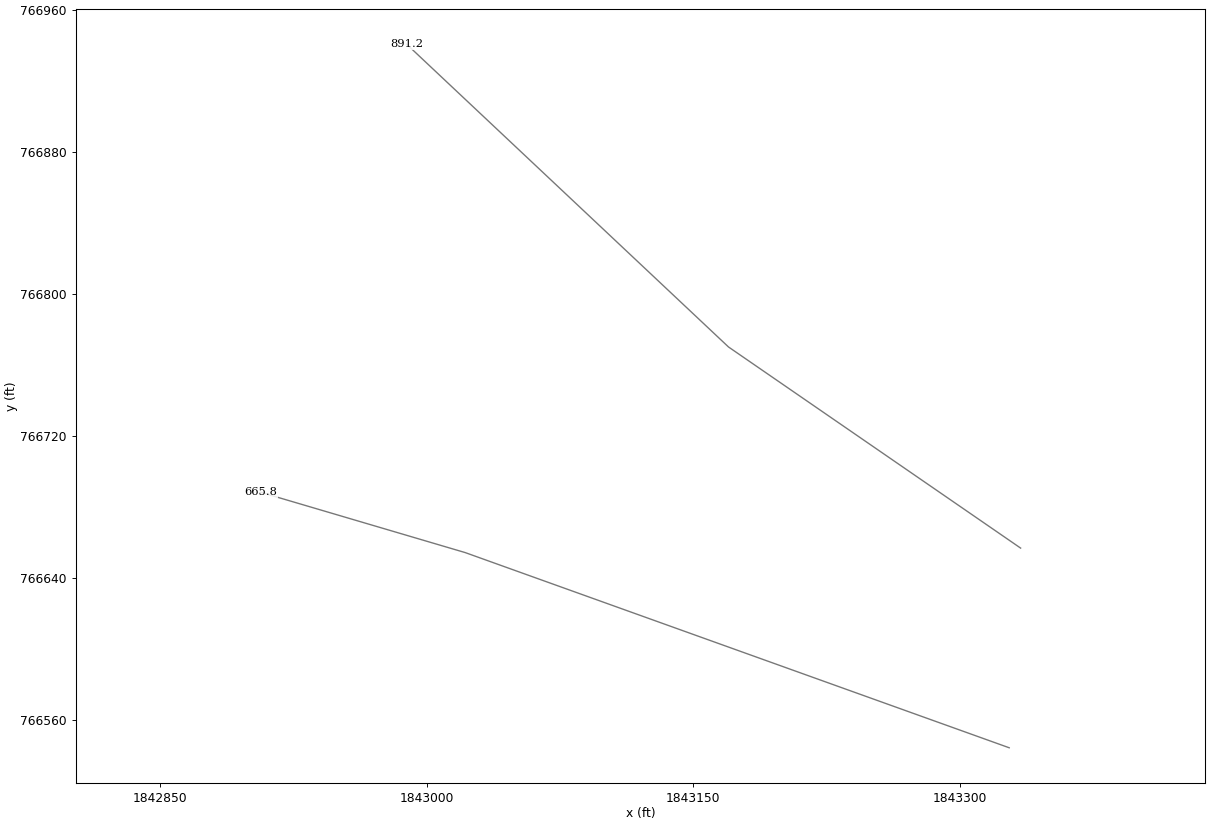
HEC-RAS study NORTH PRONG CREEK.PRJ: North Prong Creek

--- NORTH PRONG CREEK.g01 (geometry) --- (continued)

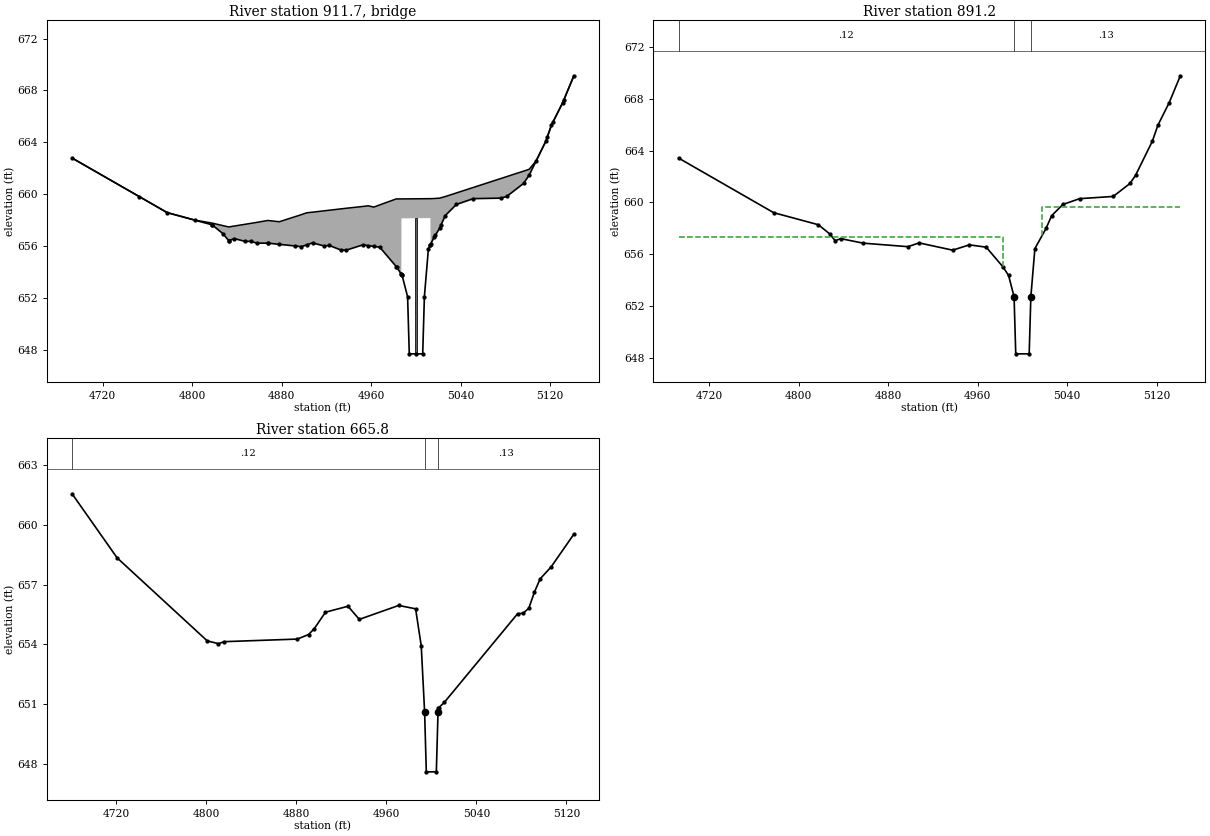
Type RM Length L Ch R = 3 ,911.7,,,
BEGIN DESCRIPTION:
Staley Store Rd
Structure ID: NCF-0060
Approximate Survey Structure
END DESCRIPTION:
Bridge Culvert--1,0,-1,-1, 0
Deck Dist Width WeirC Skew NumUp NumDn MinLoCord MaxHiCord MaxSubmerge Is_Ogee
10,21,2.6,, 42, 42,,,0.95,0,1,1,,
  4692.6  4777.6  4802.8  4817.6  4827.6  4832.6  4837.6  4847.6  4852.6  4857.6
  4867.6  4877.8  4897.6  4902.3  4907.6  4917.6  4922.6  4932.6  4937.6  4952.6
  4957.3  4962.3  4967.6  4982.3 4986.91    4987 5012.89    5013  5016.1  5021.1
  5026.1  5036.1  5051.1  5076.1  5081.1  5096.1  5101.1  5107.3  5116.1  5121.1
  5131.1  5141.1
  662.79  658.59     658  657.78  657.58  657.48  657.55  657.69  657.76  657.83
  657.98  657.88  658.43  658.57  658.62  658.72  658.77  658.87  658.92  659.06
  659.11  659.01  659.18  659.64  659.64  659.64  659.66  659.66  659.67   659.7
  659.82   660.1  660.52  661.22  661.36  661.78  661.92  662.56   664.1  665.34
  667.06  669.13
  662.79  658.58  657.99  657.65  656.95  656.42  656.58  656.36  656.38  656.23
  656.23  656.14  655.96   656.1  656.25  656.02  656.05  655.71  655.69   656.1
  656.04  655.98  655.92  654.43  653.83  658.14  658.16  656.14  656.67  657.37
  658.35  659.21  659.66   659.7  659.83  660.83  661.46  662.55  664.09  665.33
  667.05  669.13
  4692.6  4777.6  4802.8  4817.6  4827.6  4832.6  4837.6  4847.6  4852.6  4857.6
  4867.6  4877.8  4897.6  4902.3  4907.6  4917.6  4922.6  4932.6  4937.6  4952.6
  4957.3  4962.3  4967.6  4982.3 4986.91    4987 5012.89    5013  5016.1  5021.1
  5026.1  5036.1  5051.1  5076.1  5081.1  5096.1  5101.1  5107.3  5116.1  5121.1
  5131.1  5141.1
  662.79  658.59     658  657.78  657.58  657.48  657.55  657.69  657.76  657.83
  657.98  657.88  658.43  658.57  658.62  658.72  658.77  658.87  658.92  659.06
  659.11  659.01  659.18  659.64  659.64  659.64  659.66  659.66  659.67   659.7
  659.82   660.1  660.52  661.22  661.36  661.78  661.92  662.56   664.1  665.34
  667.06  669.13
  662.54  658.33  657.74   657.4   656.7  656.17  656.33  656.11  656.13  655.98
  655.98  655.89  655.71  655.85     656  655.77   655.8  655.46  655.44  655.85
  655.79  655.73  655.67  654.18  653.58  657.89  657.91  655.89  656.42  657.12
   658.1  658.96  659.41  659.45  659.58  660.58  661.21   662.3  663.84  665.08
   666.8  668.88
Pier Skew, UpSta & Num, DnSta & Num=,5000.0, 2 ,5000.0, 2 , 0 , 0 , 0 ,,
       1       1
   646.7  659.14
       1       1
  646.45  658.89
BR Coef= 1 , 1 , 0 ,1.25, 0 ,,,0.8,0,2,0,
Wspro=,,,, 1 ,,,, 0 ,,,, 0 ,,,,-1 ,-1 ,-1 , 0 , 0 , 0 , 0 , 0
BC Design=,, 0 ,, 0 ,,,,,,
BR U #Sta/Elev= 62
  4692.6  662.79  4752.8  659.81  4777.6  658.58  4802.8  657.99  4817.6  657.65
  4817.8  657.64  4827.6  656.95  4832.6  656.42  4832.8  656.43  4837.6  656.58
  4847.6  656.36  4852.6  656.38  4857.6  656.23  4867.6  656.23  4867.8  656.23
  4877.8  656.14  4892.3  656.01  4897.6  655.96  4902.3   656.1  4907.6  656.25
  4917.6  656.02  4922.6  656.05  4932.6  655.71  4937.6  655.69  4952.6   656.1
  4957.3  656.04  4962.3  655.98  4967.6  655.92  4982.3  654.43  4982.6   654.4
 4986.91  653.83    4987  653.82  4987.1  653.81  4987.6  653.74  4992.5   652.1
    4994   647.7    5000   647.7    5006   647.7  5007.5   652.1  5011.1  655.81
  5012.8   656.1 5012.89  656.12    5013  656.14  5016.1  656.67  5017.3  656.84
  5021.1  657.37  5022.3  657.61  5026.1  658.35  5036.1  659.21  5051.1  659.66
  5076.1   659.7  5081.1  659.83  5096.1  660.83  5101.1  661.46  5107.3  662.55
  5116.1  664.09  5117.3  664.39  5121.1  665.33  5122.3  665.54  5131.1  667.05
  5132.3   667.3  5141.1  669.13
BR U #Mann= 3
 4692.60    0.12  4992.5    0.05  5007.5    0.13
BR U Banks=4992.50,5007.50
BR D #Sta/Elev= 62
  4692.6  662.54  4752.8  659.56  4777.6  658.33  4802.8  657.74  4817.6   657.4
  4817.8  657.39  4827.6   656.7  4832.6  656.17  4832.8  656.18  4837.6  656.33
  4847.6  656.11  4852.6  656.13  4857.6  655.98  4867.6  655.98  4867.8  655.98
  4877.8  655.89  4892.3  655.76  4897.6  655.71  4902.3  655.85  4907.6     656
  4917.6  655.77  4922.6   655.8  4932.6  655.46  4937.6  655.44  4952.6  655.85
  4957.3  655.79  4962.3  655.73  4967.6  655.67  4982.3  654.18  4982.6  654.15
 4986.91  653.58    4987  653.57  4987.1  653.56  4987.6  653.49  4992.5  651.85
    4994  647.45    5000  647.45    5006  647.45  5007.5  651.85  5011.1  655.56
  5012.8  655.85 5012.89  655.87    5013  655.89  5016.1  656.42  5017.3  656.59
  5021.1  657.12  5022.3  657.36  5026.1   658.1  5036.1  658.96  5051.1  659.41
  5076.1  659.45  5081.1  659.58  5096.1  660.58  5101.1  661.21  5107.3   662.3
  5116.1  663.84  5117.3  664.14  5121.1  665.08  5122.3  665.29  5131.1   666.8
  5132.3  667.05  5141.1  668.88
BR D #Mann= 3
 4692.60    0.12  4992.5    0.05  5007.5    0.13
BR D Banks=4992.50,5007.50

Type RM Length L Ch R = 1 ,891.2,225.4,225.4,225.4
XS GIS Cut Line= 3
      1843334.36       766656.86      1843169.88       766770.09
      1842988.64       766940.56
BEGIN DESCRIPTION:
Downstream Section of Bridge/Culvert/Weir
END DESCRIPTION:
#Sta/Elev= 30
  4692.6  663.42  4777.6  659.21  4817.6  658.28  4827.6  657.58  4832.6  657.05
  4837.6  657.21  4857.6  656.86  4897.6  656.59  4907.6  656.88  4937.6  656.32
  4952.6  656.73  4967.6  656.55  4982.6  655.03  4987.6  654.37  4992.5  652.73
    4994  648.33    5006  648.33  5007.5  652.73  5011.1  656.44  5021.1     658
  5026.1  658.98  5036.1  659.84  5051.1  660.29  5081.1  660.46  5096.1  661.46
  5101.1  662.09  5116.1  664.72  5121.1  665.96  5131.1  667.68  5141.1  669.76
#Mann= 3 , 1 , 0
 4692.60    0.12       0  4992.5    0.05       0  5007.5    0.13       0
#XS Ineff= 2 , 0
       0  4982.5  657.34  5017.5       0  659.65
Bank Sta=4992.50,5007.50
Exp/Cntr=0.5,0.3

Type RM Length L Ch R = 1 ,665.8,0,0,0
XS GIS Cut Line= 3
      1843327.93       766544.46      1843021.61       766654.35
      1842906.45       766688.30
BEGIN DESCRIPTION:
North Prong Creek 1.0
END DESCRIPTION:
#Sta/Elev= 28
  4681.1  661.56  4721.1  658.34  4801.1  654.17  4811.1  654.03  4816.1  654.13
  4881.1  654.26  4891.1  654.49  4896.1  654.78  4906.1  655.61  4926.1  655.91
  4936.1  655.25  4971.1  655.95  4986.1  655.78  4991.1  653.92  4994.1  650.59
  4995.6  647.59  5004.5  647.59    5006  650.59  5006.1   650.8  5006.6  650.81
  5011.6  651.08  5076.6  655.53  5081.6  655.56  5086.6  655.81  5091.6  656.62
  5096.6  657.28  5106.6   657.9  5126.6  659.53
#Mann= 3 , 1 , 0
 4681.10    0.12       0  4994.1    0.05       0    5006    0.13       0
Bank Sta=4994.10,5006.00
Exp/Cntr=0.3,0.1

Chan Stop Cuts=-1