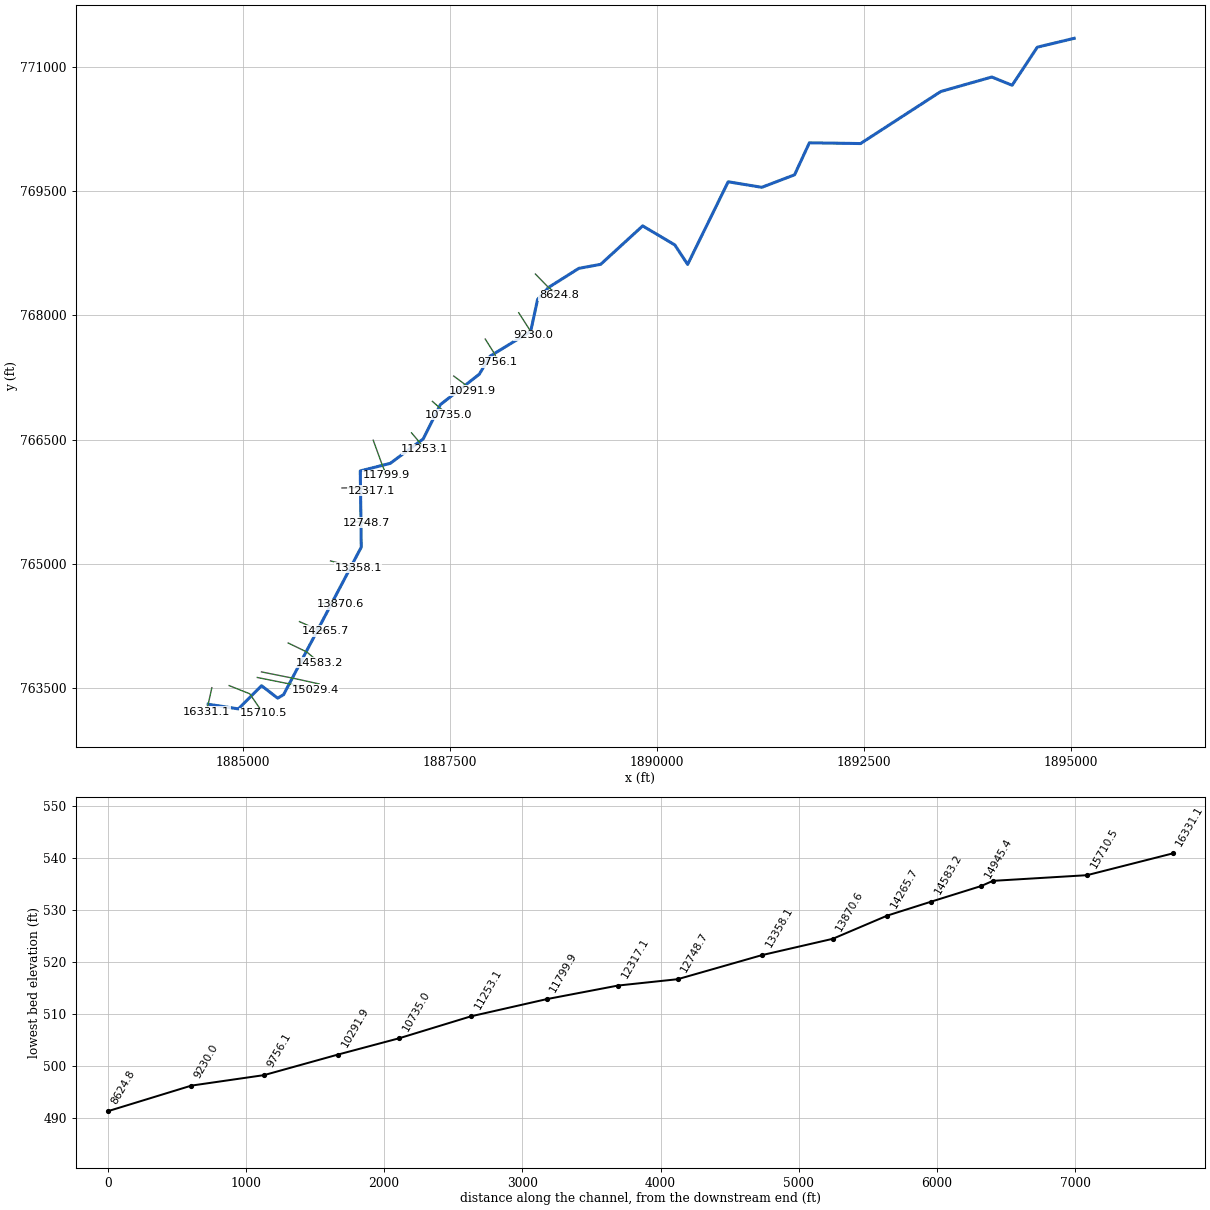
--- PINE HILL BRANCH.PRJ (project) ---

Proj Title=Pine Hill Branch
Current Plan=p01
Default Exp/Contr=0.3,0.1
English Units
Geom File=g01
Flow File=f01
Plan File=p01
Y Axis Title=Elevation
X Axis Title(PF)=Main Channel Distance
X Axis Title(XS)=Station
BEGIN DESCRIPTION:
####(Watershed Name)####
PINE HILL BRANCH
HCFCD Unit X###-##-##
(Flood Hazard, Floodway) Model
10, 2, 1, 0.2% Event
Filename:  N:\NC_flood\60273\Approximates\Eng\Haw-Big_Alamance\Eng\Pine Hill Branch\Pine Hill Branch.prj
Prepared by:  ________     Date: ________
Reviewed by:  ________     Date: ________
STATUS (Draft RAS, SVSQ, FINAL)
END DESCRIPTION:
DSS Export Rating Curves= 0
DSS Export Rating Curve Sorted= 0
DSS Export Volume Flow Curves= 0
DXF OffsetX= 0
DXF OffsetY= 0
DXF ScaleX= 1
DXF ScaleY= 10

--- PINE HILL BRANCH.p01 (plan) ---

Plan Title=100-Year-Single
Program Version=3.10
Short Identifier=Plan01
Geom File=g01
Flow File=f01
Subcritical Flow
K Sum by GR= 0
Std Step Tol= 0.01
Critical Tol= 0.01
Num of Std Step Trials= 20
Max Error Tol= 0.3
Flow Tol Ratio= 0.001
Split Flow NTrial= 30
Split Flow Tol= 0.02
Split Flow Ratio= 0.02
Log Output Level= 0
Friction Slope Method= 1
Unsteady Friction Slope Method= 2
Parabolic Critical Depth
Global Vel Dist= 0 , 0 , 0
Global Log Level= 0
CheckData=True
Encroach Param=-1 ,10,10, 2
Encroach River=Pine Hill Branch
Encroach Reach=Reach - 1
Encroach Node=16331.1
       4      .7
Encroach Node=15710.5
       4      .7
Encroach Node=15029.4
       4      .7
Encroach Node=14987.4
       4      .7
Encroach Node=14945.4
       4      .7
Encroach Node=14583.2
       4      .7
Encroach Node=14265.7
       4      .7
Encroach Node=13870.6
       4      .7
Encroach Node=13358.1
       4      .7
Encroach Node=12748.7
       4      .7
Encroach Node=12317.1
       4      .7
Encroach Node=11799.9
       4      .7
Encroach Node=11253.1
       4      .7
Encroach Node=10735.0
       4      .7
Encroach Node=10291.9
       4      .7
Encroach Node=9756.1
       4      .7
Encroach Node=9230.0
       4      .7
Encroach Node=8624.8
       4      .7
Encroach Node=7929.0
       4      .7
Encroach Node=7435.5
       4      .7
Encroach Node=7018.1
       4      .7
Encroach Node=6641.4
       4      .7
Encroach Node=6165.2
       4      .7
Encroach Node=6145.7
       4      .7
Encroach Node=6126.2
       4      .7
Encroach Node=5861.5
       4      .7
Encroach Node=5356.4
       4      .7
Encroach Node=4747.1
       4      .7
Encroach Node=4198.7
       4      .7
Encroach Node=3687.0
       4      .7
Encroach Node=3236.3
       4      .7
Encroach Node=2780.6
       4      .7
Encroach Node=2360.8
       4      .7
Encroach Node=1966.2
       4      .7
Encroach Node=1348.2
       4      .7
Encroach Node=901.3
       4      .7
Encroach Node=330.1
       4      .7
Computation Interval=1HOUR
Output Interval=1HOUR
Run HTab= 0
Run UNet= 0
Run PostProcess= 0
UNET Theta= 1
UNET Theta Warmup= 1
UNET ZTol= 0.02
UNET ZSATol= 0.05
UNET MxIter= 20
UNET MaxInSteps= 1
UNET DtIC= 0
UNET DtMin= 0
UNET MaxCRTS= 20
UNET WFStab= 2
UNET SFStab= 1
UNET WFX= 1
UNET SFX= 1
UNET DSS MLevel= 4
UNET Convert EG Bridges=-1
UNET Use Existing IB Tables=-1
UNET Froude Reduction=False
UNET Froude Limit= 1
UNET Froude Power= 10
Instantaneous Interval=1HOUR
Write IC File= 0
Echo Input=False
Echo Output=False
Write Detailed= 0

--- PINE HILL BRANCH.f01 (steady flow) ---

Flow Title= 100-Year-Single
Program Version=3.10
Number of Profiles= 2
Profile Names=100-Year,AFW
River Rch & RM=Pine Hill Branch,Reach - 1       ,16331.1
    1070    1070
River Rch & RM=Pine Hill Branch,Reach - 1       ,12748.7
    1320    1320
River Rch & RM=Pine Hill Branch,Reach - 1       ,7929
    2360    2360
River Rch & RM=Pine Hill Branch,Reach - 1       ,1966.2
    2500    2500
River Rch & RM=Pine Hill Branch,Reach - 1       ,330.1
    2750    2750
Boundary for River Rch & Prof#=Pine Hill Branch,Reach - 1       , 1
Up Type= 0
Dn Type= 3
Dn Slope=0.0056
DSS Import GetInterval= 0
DSS Import GetPeak= 0
DSS Import FillOption= 0

--- PINE HILL BRANCH.g01 (geometry) ---

Geom Title=Geom 01 by CodeH2 for Windows

River Reach=Pine Hill Branch,Reach - 1
Reach XY= 30
      1884581.95       763305.76      1884945.75       763249.75
       1885226.5       763529.19      1885421.38       763379.06
      1885492.63       763420.88      1886430.88       765201.44
         1886419          766121      1886781.25       766212.56
      1887179.25       766507.13      1887386.25       766921.13
         1887856       767287.38      1887987.38       767506.31
         1888477       767804.88      1888560.63          768191
         1888692       768334.31      1889058.25       768565.19
      1889322.38       768613.81       1889829.5       769077.56
      1890217.38       768848.31      1890372.63       768613.06
      1890862.13       769609.94         1891268          769543
      1891663.75       769693.94      1891842.63       770080.13
       1892460.5       770071.06      1893429.75       770699.13
      1894045.38       770873.88      1894291.75       770774.56
      1894595.63       771234.13      1895040.38       771340.75

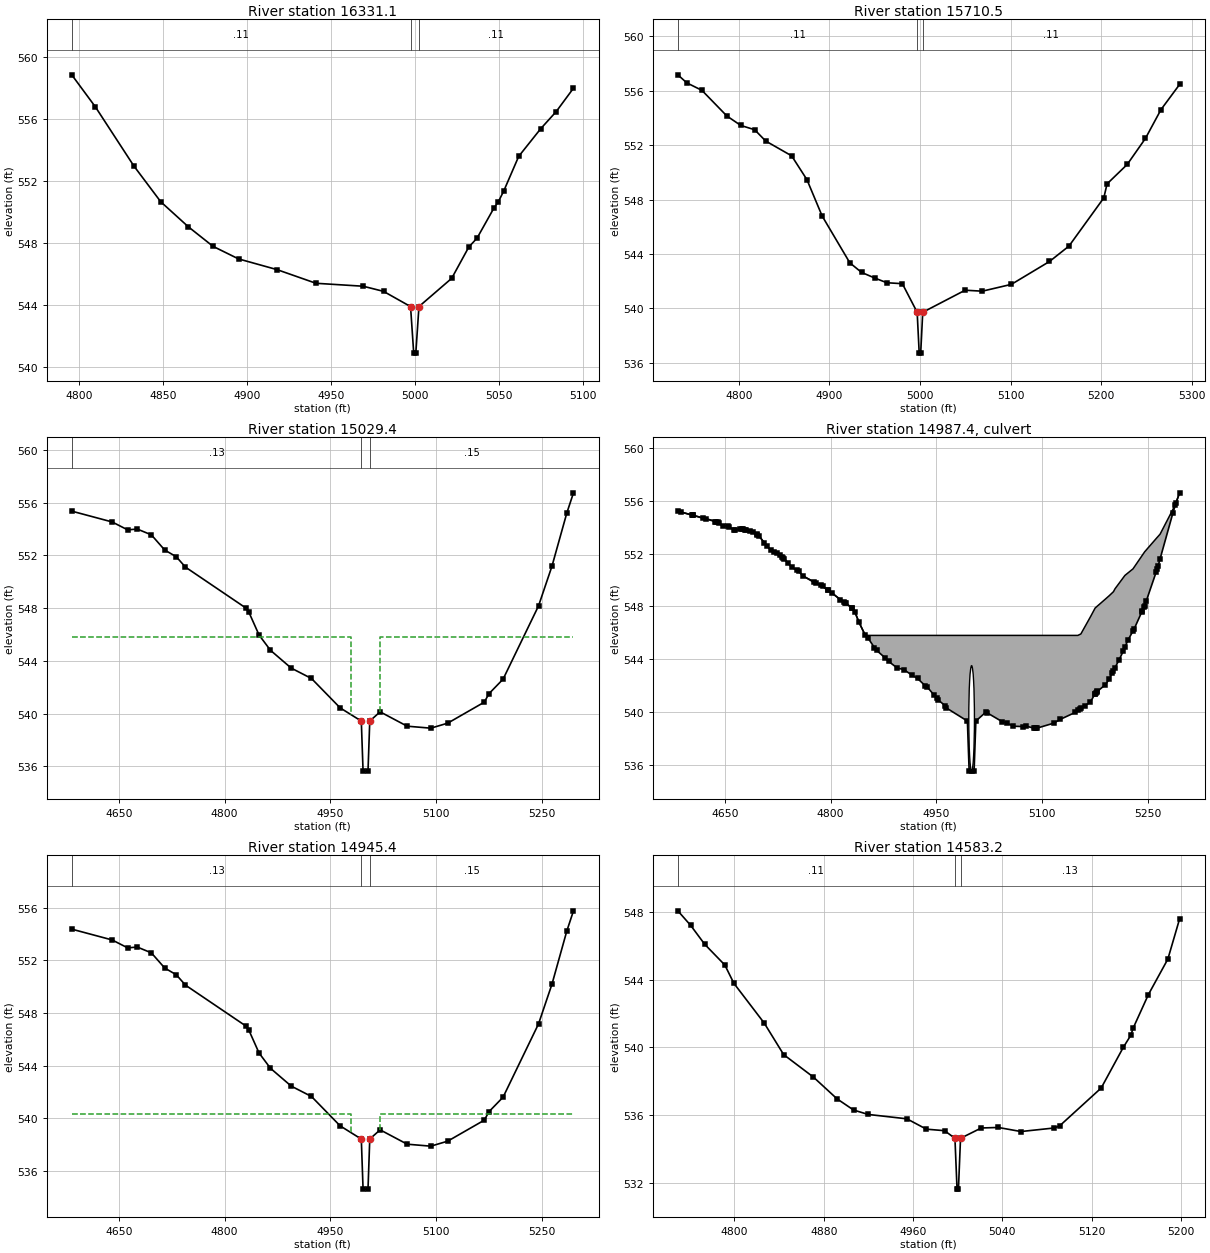
Type RM Length L Ch R = 1 ,16331.1,620.6,620.6,620.6
XS GIS Cut Line= 3
      1884626.47       763505.05      1884582.02       763305.77
      1884560.12       763213.82
BEGIN DESCRIPTION:
Pine Hill Branch 31.0
END DESCRIPTION:
#Sta/Elev= 25
  4795.8  558.84  4809.9  556.77  4832.7  552.98  4848.8  550.66  4865.2  549.05
  4879.9  547.79  4895.1  546.98    4918  546.29  4941.2  545.41  4969.3  545.22
  4981.4  544.89  4997.5  543.91 4999.38  540.91 5000.63  540.91  5002.5  543.91
    5022  545.73  5032.2  547.75  5037.1  548.32  5047.1  550.25  5049.8  550.67
    5053  551.36  5061.9  553.59    5075  555.37  5084.2  556.47  5094.5  557.98
#Mann= 3 , 1 , 0
 4795.80    0.11       0  4997.5   0.045       0  5002.5    0.11       0
Bank Sta=4997.50,5002.50
Exp/Cntr=0.3,0.1

Type RM Length L Ch R = 1 ,15710.5,681.1,681.1,681.1
XS GIS Cut Line= 3
      1884835.53       763530.46      1885084.12       763431.69
      1885246.46       763195.37
BEGIN DESCRIPTION:
Pine Hill Branch 30.0
END DESCRIPTION:
#Sta/Elev= 30
  4732.5  557.16  4742.4  556.57  4759.1  556.02  4786.6  554.14  4802.1  553.44
  4817.3  553.13  4829.5   552.3  4858.2  551.21  4875.1  549.46  4891.9  546.79
  4922.5  543.35  4935.4  542.65  4950.2  542.23  4963.3  541.89  4980.5  541.82
 4996.85  539.72  4999.1  536.72 5000.75  536.72    5003  539.72  5049.8  541.34
  5068.8  541.27  5100.9  541.77    5143  543.45  5164.5  544.58    5203  548.12
  5206.6  549.15  5228.9  550.58    5249  552.49  5266.2  554.61  5286.7  556.45
#Mann= 3 , 1 , 0
 4732.50    0.11       0 4996.85   0.045       0    5003    0.11       0
Bank Sta=4996.85,5003.00
Exp/Cntr=0.5,0.3

Type RM Length L Ch R = 1 ,15029.4,84,84,84
XS GIS Cut Line= 3
      1885175.49       763628.52      1885584.29       763546.80
      1885872.48       763483.30
BEGIN DESCRIPTION:
Upstream Section of Bridge/Culvert/Weir
END DESCRIPTION:
#Sta/Elev= 30
  4583.1  555.36  4640.4  554.54  4662.4  553.94  4676.1     554  4696.1  553.56
    4715  552.41  4731.4   551.9  4744.5  551.11  4829.9  548.02  4834.3  547.71
  4848.9  545.96  4865.1   544.8  4894.5  543.45  4923.3  542.66    4964  540.43
    4994  539.43  4996.5  535.63  5003.5  535.63    5006  539.43  5020.7  540.13
  5059.1  539.04  5092.6  538.89  5116.6  539.27  5168.4  540.86  5175.4  541.52
  5195.2  542.61  5245.5  548.17  5264.6  551.19  5285.7  555.23  5295.1  556.75
#Mann= 3 , 1 , 0
 4583.10    0.13       0    4994   0.045       0    5006    0.15       0
#XS Ineff= 2 , 0
       0    4980   545.8    5020       0   545.8
Bank Sta=4994.00,5006.00
Exp/Cntr=0.5,0.3

Type RM Length L Ch R = 2 ,14987.4,,,
BEGIN DESCRIPTION:
Pine Hill Branch - Clark Rd
Structure ID: NCF-2018
Approximate Survey Structure
END DESCRIPTION:
Bridge Culvert--1,0,-1,-1, 0
Deck Dist Width WeirC Skew NumUp NumDn MinLoCord MaxHiCord MaxSubmerge Is_Ogee
10,64,3,, 56, 59,,,0.95,0,1,1,,
  4583.1  4640.4  4646.7  4654.5  4662.4  4676.1    4695  4698.4  4709.3    4715
  4731.4  4744.5  4754.8  4761.1  4788.4  4829.9  4834.3  4840.3  4848.9  4852.6
  4865.1  4882.4  4894.5  4903.7  4923.3  4937.1  4951.1    4952  4962.9    4964
    4994  4996.5  5003.5    5006  5020.7  5043.8  5059.1  5077.1  5091.4  5116.6
  5150.7    5155  5168.4  5175.3  5189.9  5195.2  5201.3  5203.5  5217.5  5221.6
    5229  5245.5  5261.9  5267.4  5288.9  5295.1
  555.23  554.41  554.11  554.07  553.81  553.87  553.47  553.34  552.59  552.28
  551.77  550.98  550.66   550.3  549.53  547.89  547.58  546.78  545.83   545.8
   545.8   545.8   545.8   545.8   545.8   545.8   545.8   545.8   545.8   545.8
   545.8   545.8   545.8   545.8   545.8   545.8   545.8   545.8   545.8   545.8
   545.8  545.91  547.19  547.88  548.56  548.81  549.12  549.34  550.35  550.53
  550.85  552.14  553.15  553.48   555.7  556.62
  555.23  554.41  554.11  554.07  553.81  553.87  553.47  553.34  552.59  552.28
  551.77  550.98  550.66   550.3  549.53  547.89  547.58  546.78  545.83  545.63
  544.67  543.82  543.32  543.21  542.53  541.88  541.04  540.93  540.44   540.3
   539.3   535.5   535.5   539.3     540  539.24  538.91  538.92  538.75  539.14
  540.11  540.27  540.73  541.38  542.06  542.48  543.12  543.35  544.89  545.42
  546.13  548.04  550.61   551.6  555.66  556.62
  4583.1  4602.5  4605.2  4640.4  4646.7  4654.5  4662.4  4676.1    4695  4698.4
  4709.3    4715  4731.4  4744.5  4754.8  4761.1  4788.4  4829.9  4834.3  4840.3
  4848.9  4852.6  4865.1  4882.4  4894.5  4903.7  4923.3  4937.1  4951.1    4952
  4962.9    4964    4994  4996.5  5003.5    5006  5020.7  5043.8  5059.1  5077.1
  5091.4  5116.6  5150.7    5155  5168.4  5175.3  5189.9  5195.2  5201.3  5203.5
  5217.5  5221.6    5229  5245.5  5261.9  5267.4  5285.7    5290  5295.1
  555.07  554.89  554.75  554.26  553.96  553.92  553.66  553.72  553.32  553.19
  552.44  552.13  551.62  550.83  550.51  550.15  549.38  547.74  547.43  546.63
   545.8   545.8   545.8   545.8   545.8   545.8   545.8   545.8   545.8   545.8
   545.8   545.8   545.8   545.8   545.8   545.8   545.8   545.8   545.8   545.8
   545.8   545.8   545.8  545.91  547.19  547.88  548.56  548.81  549.12  549.34
  550.35  550.53  550.85  552.14  553.15  553.48  555.37  555.83  556.46
  554.91  554.62  554.58  554.09  553.79  553.75  553.49  553.55  553.15  553.02
  552.27  551.96  551.45  550.66  550.34  549.98  549.21  547.57  547.26  546.46
  545.51  545.31  544.35   543.5     543  542.89  542.21  541.56  540.72  540.61
  540.12  539.98  538.98  535.18  535.18  538.98  539.68  538.92  538.59   538.6
  538.43  538.82  539.79  539.95  540.41  541.06  541.74  542.16   542.8  543.03
  544.57   545.1  545.81  547.72  550.29  551.28  554.78  555.53   556.3
BR Coef= 1 , 0 , 0 ,1.25, 0 ,,,0.8,-1,2,0,
Wspro=,,,, 1 ,,,, 0 ,,,, 0 ,,,,-1 ,-1 ,-1 , 0 , 0 , 0 , 0 , 0
Culvert=1,8.0,,64.0,0.024,0.9,1.0,2,3,535.50,4999.99,535.18,4999.99,Culvert #1  ,0,10
BC Design=,, 0 ,, 0 ,,,,,,
BR U #Sta/Elev= 125
  4583.1  555.23  4587.5  555.16  4602.5  554.94    4604  554.92  4605.2   554.9
  4619.1  554.69  4622.7  554.64  4636.4  554.44  4637.6  554.42  4640.4  554.41
  4642.1  554.33  4646.7  554.11  4654.5  554.07  4656.4  554.01  4662.4  553.81
  4664.8  553.82  4671.7  553.85  4673.7  553.86  4676.1  553.87  4678.4  553.81
  4680.4  553.78  4685.1  553.72  4689.2  553.62    4695  553.47  4696.1  553.43
  4698.4  553.34  4705.5  552.85  4709.3  552.59    4715  552.28  4719.7  552.15
  4723.5  552.05  4728.1  551.89  4731.4  551.77  4732.8   551.7  4734.2  551.63
  4739.4   551.3  4744.5  550.98  4752.3  550.74  4754.8  550.66  4761.1   550.3
  4775.9  549.84  4779.1  549.76    4786  549.59  4788.4  549.53  4795.6  549.23
  4795.9  549.22  4801.9  549.03  4813.9   548.5    4819  548.35  4820.9  548.29
  4821.6  548.26  4829.8  547.89  4829.9  547.89  4834.3  547.58  4840.3  546.78
  4848.9  545.83  4852.6  545.63  4862.1  544.87  4865.1  544.67  4877.3  544.09
  4882.4  543.82  4894.5  543.32  4903.7  543.21  4915.4  542.78  4923.3  542.53
  4934.3  541.97  4937.1  541.88    4947  541.25  4951.1  541.04    4952  540.93
  4962.9  540.44    4964   540.3    4994   539.3  4996.5   535.5    5000   535.5
  5003.5   535.5    5006   539.3  5020.7     540  5022.5  539.91  5043.8  539.24
  5050.6  539.13  5059.1  538.91  5073.4  538.88  5077.1  538.92  5088.3  538.76
  5090.4  538.77  5091.4  538.75  5092.6  538.76  5116.6  539.14  5125.5  539.42
  5146.8  539.95  5150.7  540.11  5153.4  540.22    5155  540.27  5160.2  540.45
  5168.4  540.73  5175.3  541.38  5175.4  541.39  5176.6  541.46  5177.7  541.52
  5178.4  541.55  5189.9  542.06  5195.2  542.48  5199.5  542.93  5201.3  543.12
  5203.5  543.35  5209.2  543.94  5215.2   544.6  5217.5  544.89  5221.6  545.42
    5229  546.13  5230.5  546.27  5241.7  547.61  5242.1  547.66  5244.5  547.93
  5245.5  548.04  5247.9  548.42  5261.9  550.61  5263.1  550.84  5264.6  551.06
  5267.4   551.6  5285.7   555.1  5288.9  555.66    5290  555.85  5295.1  556.62
BR U #Mann= 3
 4583.10    0.13    4994   0.045    5006    0.15
BR U Banks=4994.00,5006.00
BR D #Sta/Elev= 125
  4583.1  554.91  4587.5  554.84  4602.5  554.62    4604   554.6  4605.2  554.58
  4619.1  554.37  4622.7  554.32  4636.4  554.12  4637.6   554.1  4640.4  554.09
  4642.1  554.01  4646.7  553.79  4654.5  553.75  4656.4  553.69  4662.4  553.49
  4664.8   553.5  4671.7  553.53  4673.7  553.54  4676.1  553.55  4678.4  553.49
  4680.4  553.46  4685.1   553.4  4689.2   553.3    4695  553.15  4696.1  553.11
  4698.4  553.02  4705.5  552.53  4709.3  552.27    4715  551.96  4719.7  551.83
  4723.5  551.73  4728.1  551.57  4731.4  551.45  4732.8  551.38  4734.2  551.31
  4739.4  550.98  4744.5  550.66  4752.3  550.42  4754.8  550.34  4761.1  549.98
  4775.9  549.52  4779.1  549.44    4786  549.27  4788.4  549.21  4795.6  548.91
  4795.9   548.9  4801.9  548.71  4813.9  548.18    4819  548.03  4820.9  547.97
  4821.6  547.94  4829.8  547.57  4829.9  547.57  4834.3  547.26  4840.3  546.46
  4848.9  545.51  4852.6  545.31  4862.1  544.55  4865.1  544.35  4877.3  543.77
  4882.4   543.5  4894.5     543  4903.7  542.89  4915.4  542.46  4923.3  542.21
  4934.3  541.65  4937.1  541.56    4947  540.93  4951.1  540.72    4952  540.61
  4962.9  540.12    4964  539.98    4994  538.98  4996.5  535.18    5000  535.18
  5003.5  535.18    5006  538.98  5020.7  539.68  5022.5  539.59  5043.8  538.92
  5050.6  538.81  5059.1  538.59  5073.4  538.56  5077.1   538.6  5088.3  538.44
  5090.4  538.45  5091.4  538.43  5092.6  538.44  5116.6  538.82  5125.5   539.1
  5146.8  539.63  5150.7  539.79  5153.4   539.9    5155  539.95  5160.2  540.13
  5168.4  540.41  5175.3  541.06  5175.4  541.07  5176.6  541.14  5177.7   541.2
  5178.4  541.23  5189.9  541.74  5195.2  542.16  5199.5  542.61  5201.3   542.8
  5203.5  543.03  5209.2  543.62  5215.2  544.28  5217.5  544.57  5221.6   545.1
    5229  545.81  5230.5  545.95  5241.7  547.29  5242.1  547.34  5244.5  547.61
  5245.5  547.72  5247.9   548.1  5261.9  550.29  5263.1  550.52  5264.6  550.74
  5267.4  551.28  5285.7  554.78  5288.9  555.34    5290  555.53  5295.1   556.3
BR D #Mann= 3
 4583.10    0.13    4994   0.045    5006    0.15
BR D Banks=4994.00,5006.00

Type RM Length L Ch R = 1 ,14945.4,362.2,362.2,362.2
XS GIS Cut Line= 3
      1885225.71       763695.86      1885634.51       763614.14
      1885922.70       763550.64
BEGIN DESCRIPTION:
Downstream Section of Bridge/Culvert/Weir
END DESCRIPTION:
#Sta/Elev= 30
  4583.1  554.37  4640.4  553.55  4662.4  552.95  4676.1  553.01  4696.1  552.57
    4715  551.42  4731.4  550.91  4744.5  550.12  4829.9  547.03  4834.3  546.72
  4848.9  544.97  4865.1  543.81  4894.5  542.46  4923.3  541.67    4964  539.44
    4994  538.44  4996.5  534.64  5003.5  534.64    5006  538.44  5020.7  539.14
  5059.1  538.05  5092.6   537.9  5116.6  538.28  5168.4  539.87  5175.4  540.53
  5195.2  541.62  5245.5  547.18  5264.6   550.2  5285.7  554.24  5295.1  555.76
#Mann= 3 , 1 , 0
 4583.10    0.13       0    4994   0.045       0    5006    0.15       0
#XS Ineff= 2 , 0
       0    4980  540.35    5020       0  540.35
Bank Sta=4994.00,5006.00
Exp/Cntr=0.5,0.3

Type RM Length L Ch R = 1 ,14583.2,317.5,317.5,317.5
XS GIS Cut Line= 3
      1885548.41       764044.58      1885774.13       763935.50
      1885926.20       763807.61
BEGIN DESCRIPTION:
Pine Hill Branch 29.0
END DESCRIPTION:
#Sta/Elev= 30
  4749.3  548.06  4760.8   547.2  4773.3  546.09  4791.4  544.86  4799.5  543.78
  4826.7  541.43  4844.1  539.57  4870.8  538.24  4891.9  536.96  4906.7   536.3
  4919.7  536.04  4954.5  535.78  4971.9  535.17  4988.2  535.08  4997.5  534.63
 4999.38  531.63 5000.63  531.63  5002.5  534.63  5021.1  535.24  5036.4  535.27
  5056.6  535.03  5086.4  535.24  5091.2  535.36  5128.5   537.6  5148.3     540
  5154.9   540.7  5157.3  541.16  5170.8  543.12  5188.2  545.21  5198.7  547.58
#Mann= 3 , 1 , 0
 4749.30    0.11       0  4997.5    0.05       0  5002.5    0.13       0
Bank Sta=4997.50,5002.50
Exp/Cntr=0.3,0.1

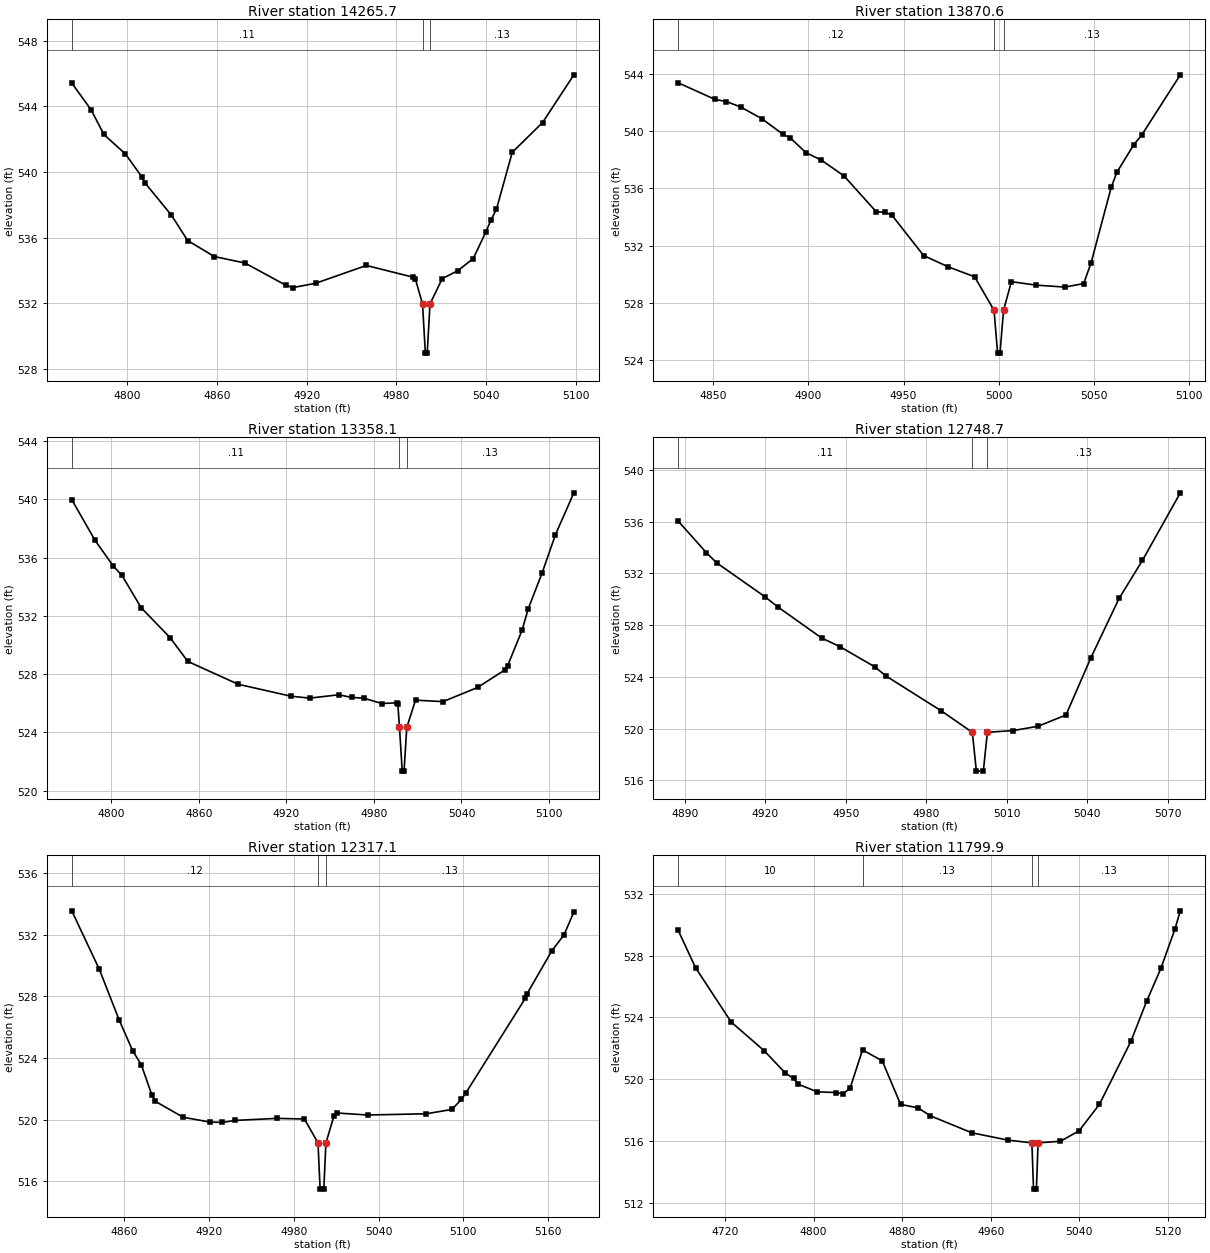
Type RM Length L Ch R = 1 ,14265.7,395.1,395.1,395.1
XS GIS Cut Line= 3
      1885684.87       764302.56      1885901.50       764206.19
      1885998.74       764189.28
BEGIN DESCRIPTION:
Pine Hill Branch 28.0
END DESCRIPTION:
#Sta/Elev= 29
  4762.9  545.43  4775.8   543.8  4784.4  542.29  4798.8   541.1  4809.8   539.7
  4812.1  539.31  4829.6  537.36  4840.4  535.82  4858.3  534.84  4878.7  534.45
  4906.1  533.09  4910.8  532.95    4926  533.21  4959.9   534.3  4990.9  533.59
  4992.7  533.48  4997.5  531.95 4999.38  528.95 5000.63  528.95  5002.5  531.95
  5010.7   533.5  5021.1  533.98  5031.4  534.72    5040  536.37  5043.3  537.08
  5046.9  537.72  5057.5   541.2  5077.8  543.02  5098.7  545.93
#Mann= 3 , 1 , 0
 4762.90    0.11       0  4997.5    0.05       0  5002.5    0.13       0
Bank Sta=4997.50,5002.50
Exp/Cntr=0.3,0.1

Type RM Length L Ch R = 1 ,13870.6,512.5,512.5,512.5
XS GIS Cut Line= 3
      1885917.34       764514.25      1886084.62       764532.63
      1886177.21       764510.02
BEGIN DESCRIPTION:
Pine Hill Branch 27.0
END DESCRIPTION:
#Sta/Elev= 30
  4831.7  543.39    4851  542.23    4857  542.08  4864.5   541.7  4875.6  540.88
  4886.7  539.79  4890.5  539.54  4898.7  538.51  4906.9  537.98  4918.7  536.88
  4935.6  534.38  4940.4  534.32  4943.9  534.13  4960.5  531.31  4973.4  530.52
  4987.3  529.82  4997.5  527.48 4999.38  524.48 5000.63  524.48  5002.5  527.48
  5006.6  529.48  5019.4  529.24  5034.8   529.1  5044.6  529.35  5048.5  530.82
    5059  536.07    5062  537.13  5070.9  539.07    5075  539.73  5095.3  543.95
#Mann= 3 , 1 , 0
 4831.70    0.12       0  4997.5    0.05       0  5002.5    0.13       0
Bank Sta=4997.50,5002.50
Exp/Cntr=0.3,0.1

Type RM Length L Ch R = 1 ,13358.1,609.4,609.4,609.4
XS GIS Cut Line= 3
      1886059.69       765035.06      1886279.63       764978.50
      1886393.45       764951.39
BEGIN DESCRIPTION:
Pine Hill Branch 26.0
END DESCRIPTION:
#Sta/Elev= 30
  4772.9  539.97  4788.9  537.17  4801.4  535.41  4807.3  534.77  4820.5  532.55
  4840.2  530.51  4852.4  528.87    4887   527.3  4923.2  526.48    4936  526.35
  4955.9  526.58  4964.7   526.4  4972.9  526.35  4985.4  525.98    4996  526.03
  4996.4  525.92  4997.5  524.34 4999.38  521.34 5000.63  521.34  5002.5  524.34
  5008.5  526.21  5027.3  526.11    5051  527.08  5069.8  528.29  5071.6  528.57
  5081.5  531.01  5085.8   532.5  5095.2  534.93  5104.4  537.57    5117  540.44
#Mann= 3 , 1 , 0
 4772.90    0.11       0  4997.5    0.05       0  5002.5    0.13       0
Bank Sta=4997.50,5002.50
Exp/Cntr=0.3,0.1

Type RM Length L Ch R = 1 ,12748.7,431.6,431.6,431.6
XS GIS Cut Line= 3
      1886310.71       765509.00      1886423.00       765503.94
      1886497.22       765495.52
BEGIN DESCRIPTION:
Pine Hill Branch 25.0
END DESCRIPTION:
#Sta/Elev= 21
  4887.6  536.04  4898.1   533.6  4901.9  532.82  4919.8  530.21  4924.9  529.38
    4941  527.01    4948  526.32  4960.8  524.78    4965  524.07  4985.7  521.36
  4997.2  519.71  4998.7  516.71  5001.3  516.71  5002.8  519.71  5012.5  519.85
  5021.7  520.18  5032.1  521.05  5041.4  525.49  5051.9  530.07  5060.6  533.01
  5074.7  538.23
#Mann= 3 , 1 , 0
 4887.60    0.11       0  4997.2    0.05       0  5002.8    0.13       0
Bank Sta=4997.20,5002.80
Exp/Cntr=0.3,0.1

Type RM Length L Ch R = 1 ,12317.1,517.2,517.2,517.2
XS GIS Cut Line= 3
      1886198.25       765915.21      1886375.12       765918.00
      1886549.35       765881.04
BEGIN DESCRIPTION:
Pine Hill Branch 24.0
END DESCRIPTION:
#Sta/Elev= 29
  4823.1  533.55  4842.6  529.75  4856.6  526.47  4866.1  524.48  4872.2  523.57
  4879.8  521.59  4882.3  521.18    4902  520.15    4921  519.84  4929.6  519.82
  4938.6  519.95    4968  520.08  4987.6  520.04  4997.2  518.49  4998.7  515.49
  5001.3  515.49  5002.8  518.49  5008.5  520.24  5010.7  520.43  5032.2   520.3
  5073.7  520.38  5091.8  520.66  5098.6  521.31  5101.8  521.74  5143.9  527.89
  5145.1  528.18  5162.3  530.92  5171.2     532  5178.1  533.47
#Mann= 3 , 1 , 0
 4823.10    0.12       0  4997.2    0.05       0  5002.8    0.13       0
Bank Sta=4997.20,5002.80
Exp/Cntr=0.3,0.1

Type RM Length L Ch R = 1 ,11799.9,546.8,546.8,546.8
XS GIS Cut Line= 3
      1886575.31       766491.52      1886685.63       766188.69
      1886735.91       766067.40
BEGIN DESCRIPTION:
Pine Hill Branch 23.0
END DESCRIPTION:
#Sta/Elev= 30
  4677.7  529.63  4693.3  527.22  4725.6  523.69  4755.3  521.84  4774.6  520.38
  4781.9  520.04  4786.1  519.67  4803.3  519.17  4820.2  519.13  4826.6  519.04
    4833  519.42  4844.2  521.89    4862  521.18  4878.6  518.36  4894.5  518.13
  4905.5  517.62  4942.9  516.52    4976  516.04  4997.2  515.87  4998.7  512.87
  5001.3  512.87  5002.8  515.87    5023  515.97  5039.9  516.65  5058.2  518.36
  5086.7  522.45  5100.8  525.03  5113.8  527.18  5126.4  529.71  5131.3   530.9
#Mann= 4 , 1 , 0
 4677.70      10       0  4844.2    0.13       0  4997.2    0.05       0
  5002.8    0.13       0
Bank Sta=4997.20,5002.80
Exp/Cntr=0.3,0.1

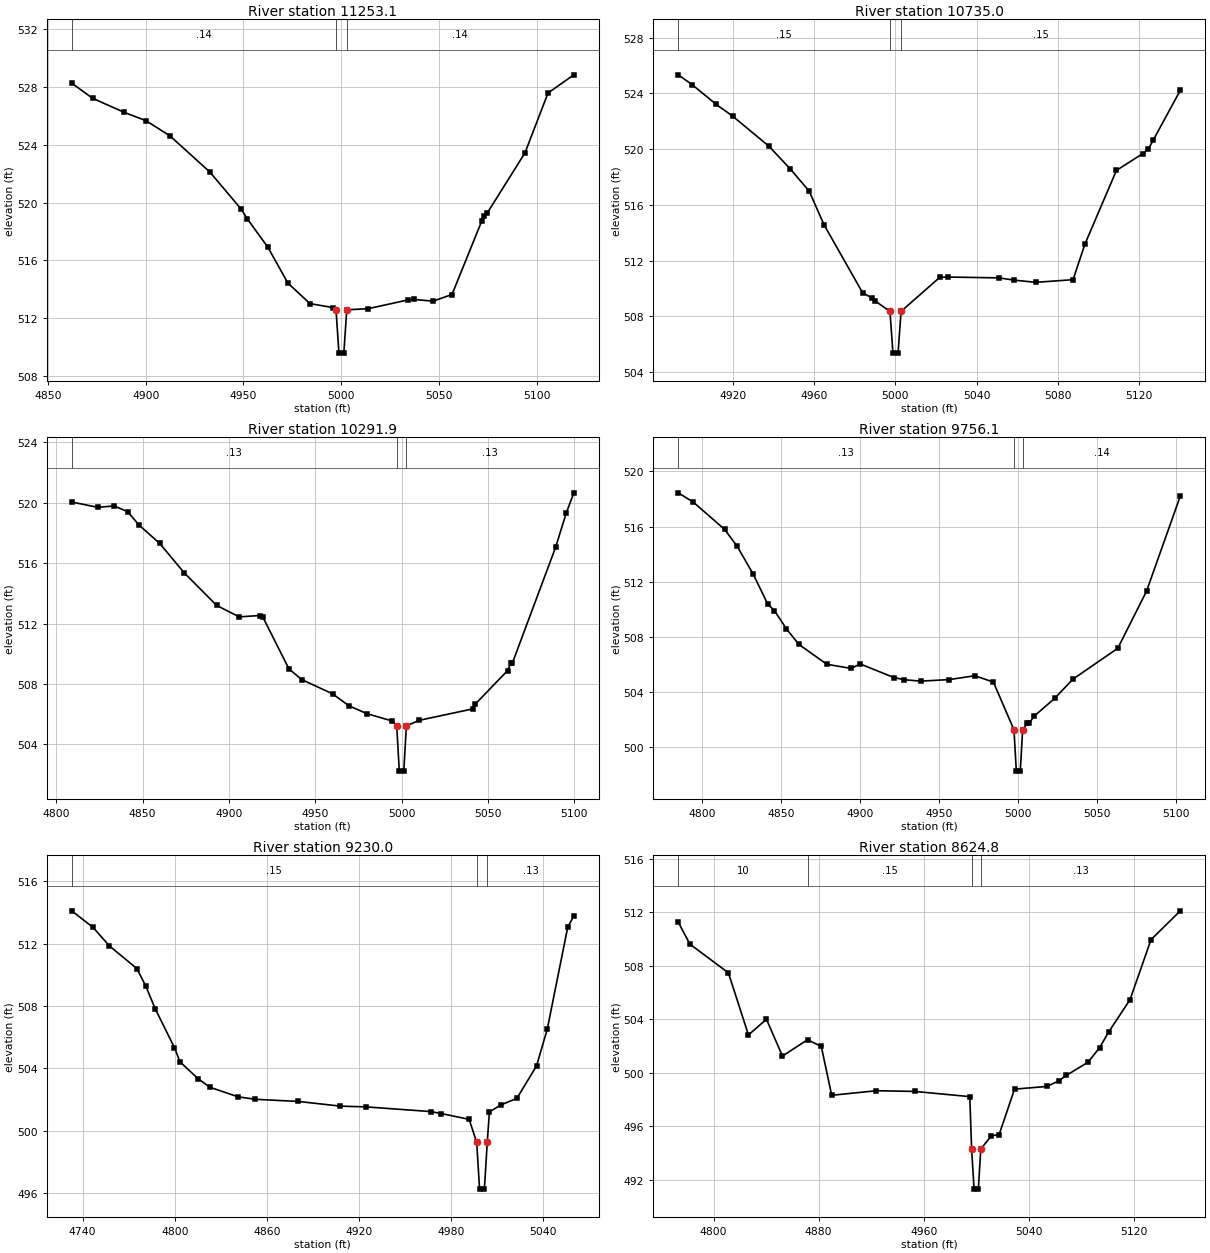
Type RM Length L Ch R = 1 ,11253.1,518.1,518.1,518.1
XS GIS Cut Line= 3
      1887038.05       766580.07      1887127.50       766475.25
      1887199.71       766380.79
BEGIN DESCRIPTION:
Pine Hill Branch 22.0
END DESCRIPTION:
#Sta/Elev= 27
  4862.2  528.27  4872.8  527.23    4889  526.25  4900.2  525.67  4912.4  524.62
  4932.7  522.13  4948.8  519.55    4952  518.86  4962.5   516.9  4972.7  514.42
    4984     513  4995.9  512.72  4997.3  512.57  4998.8  509.57  5001.3  509.57
  5002.8  512.57  5013.8  512.65  5033.9  513.25  5037.1  513.29  5046.9  513.17
  5056.6  513.63  5071.9  518.75  5073.2   519.1  5074.5  519.25  5093.9  523.44
  5105.7  527.59  5118.9  528.85
#Mann= 3 , 1 , 0
 4862.20    0.14       0  4997.3    0.05       0  5002.8    0.14       0
Bank Sta=4997.30,5002.80
Exp/Cntr=0.3,0.1

Type RM Length L Ch R = 1 ,10735.0,443.1,443.1,443.1
XS GIS Cut Line= 3
      1887289.96       766960.03      1887370.37       766889.31
      1887479.64       766800.98
BEGIN DESCRIPTION:
Pine Hill Branch 21.0
END DESCRIPTION:
#Sta/Elev= 27
  4892.9  525.33  4899.8  524.62  4911.6  523.21  4919.7  522.37  4937.6  520.21
  4948.2  518.57  4957.5  516.98  4964.8  514.57  4983.8   509.7  4988.3  509.32
  4989.8  509.12  4997.3  508.36  4998.8  505.36  5001.3  505.36  5002.8  508.36
  5021.9   510.8  5025.7  510.82  5051.1  510.76  5058.4   510.6  5069.2  510.44
  5087.6  510.63  5093.5   513.2    5109  518.47  5121.9  519.67  5124.8  520.02
  5127.2  520.66  5140.5  524.22
#Mann= 3 , 1 , 0
 4892.90    0.15       0  4997.3    0.05       0  5002.8    0.15       0
Bank Sta=4997.30,5002.80
Exp/Cntr=0.3,0.1

Type RM Length L Ch R = 1 ,10291.9,535.8,535.8,535.8
XS GIS Cut Line= 3
      1887547.37       767265.83      1887700.75       767152.00
      1887777.92       767088.71
BEGIN DESCRIPTION:
Pine Hill Branch 20.0
END DESCRIPTION:
#Sta/Elev= 30
    4809  520.05  4824.1   519.7  4833.5  519.79  4841.4  519.41  4847.9  518.53
  4859.9  517.31  4874.2  515.35  4892.9   513.2    4906  512.44  4917.8  512.53
  4919.7  512.42  4934.8  508.99  4942.3  508.28  4960.1  507.34  4969.5  506.55
  4979.9  506.03  4994.7  505.54  4997.2  505.22  4998.7  502.22  5001.3  502.22
  5002.8  505.22  5010.4  505.59  5041.5  506.35  5042.8  506.67  5061.4  508.88
  5063.4  509.39  5064.2  509.38  5089.2  517.04  5095.4  519.32  5099.8  520.66
#Mann= 3 , 1 , 0
 4809.00    0.13       0  4997.2    0.05       0  5002.8    0.13       0
Bank Sta=4997.20,5002.80
Exp/Cntr=0.3,0.1

Type RM Length L Ch R = 1 ,9756.1,526.1,526.1,526.1
XS GIS Cut Line= 3
      1887928.18       767712.24      1888043.13       767530.19
      1888079.82       767434.48
BEGIN DESCRIPTION:
Pine Hill Branch 19.0
END DESCRIPTION:
#Sta/Elev= 30
  4784.7  518.45  4794.2  517.78  4814.1  515.79    4822  514.57  4832.2  512.54
  4841.4  510.37  4845.6   509.9  4853.2  508.58  4861.1  507.45  4878.8  506.01
  4894.2  505.71  4899.8  506.04  4921.2  505.05  4927.7  504.89  4938.2  504.79
  4956.2   504.9  4972.4  505.18  4984.2  504.72  4997.2  501.26  4998.7  498.26
  5001.2  498.26  5002.7  501.26  5005.5  501.72  5006.8  501.74  5010.1  502.26
    5023  503.54  5034.5  504.93  5062.9  507.17  5081.1  511.31  5102.5  518.22
#Mann= 3 , 1 , 0
 4784.70    0.13       0  4997.2    0.05       0  5002.7    0.14       0
Bank Sta=4997.20,5002.70
Exp/Cntr=0.3,0.1

Type RM Length L Ch R = 1 ,9230.0,605.2,605.2,605.2
XS GIS Cut Line= 3
      1888332.60       768029.58      1888477.00       767804.87
      1888511.89       767756.19
BEGIN DESCRIPTION:
Pine Hill Branch 18.0
END DESCRIPTION:
#Sta/Elev= 29
  4732.9  514.11  4746.8  513.04  4757.4  511.86  4775.3   510.4  4781.1  509.28
  4787.2  507.83  4799.8  505.32  4803.4  504.41  4815.3  503.32  4822.9  502.78
  4841.1  502.17  4852.2  502.01  4880.4  501.87  4907.8  501.57  4924.7  501.52
  4966.7  501.22  4973.7  501.09  4991.7  500.72 4996.63  499.24  4998.5  496.24
 5001.63  496.24  5003.5  499.24  5004.9   501.2  5012.5  501.65  5022.8  502.07
  5035.6  504.15  5042.6  506.52  5055.9  513.05  5059.9  513.79
#Mann= 3 , 1 , 0
 4732.90    0.15       0 4996.63    0.05       0  5003.5    0.13       0
Bank Sta=4996.63,5003.50
Exp/Cntr=0.3,0.1

Type RM Length L Ch R = 1 ,8624.8,695.8,695.8,695.8
XS GIS Cut Line= 3
      1888533.70       768497.01      1888692.00       768334.31
      1888816.79       768241.53
BEGIN DESCRIPTION:
Pine Hill Branch 17.0
END DESCRIPTION:
#Sta/Elev= 28
    4773  511.26  4781.9  509.61  4811.2  507.47  4826.5  502.83  4840.2     504
  4852.4  501.25  4871.5  502.47    4882  501.97  4889.9  498.32  4923.9  498.66
    4953  498.61  4995.1  498.22  4996.5  494.31 4998.38  491.31 5001.63  491.31
  5003.5  494.31  5011.6  495.29  5017.5  495.39  5029.2  498.78  5053.8  498.98
  5062.8  499.39  5068.7  499.81  5085.2  500.79  5094.1  501.89  5100.8  503.03
  5117.2  505.47  5133.2  509.95  5155.5   512.1
#Mann= 4 , 1 , 0
 4773.00      10       0  4871.5    0.15       0  4996.5    0.05       0
  5003.5    0.13       0
Bank Sta=4996.50,5003.50
Exp/Cntr=0.3,0.1