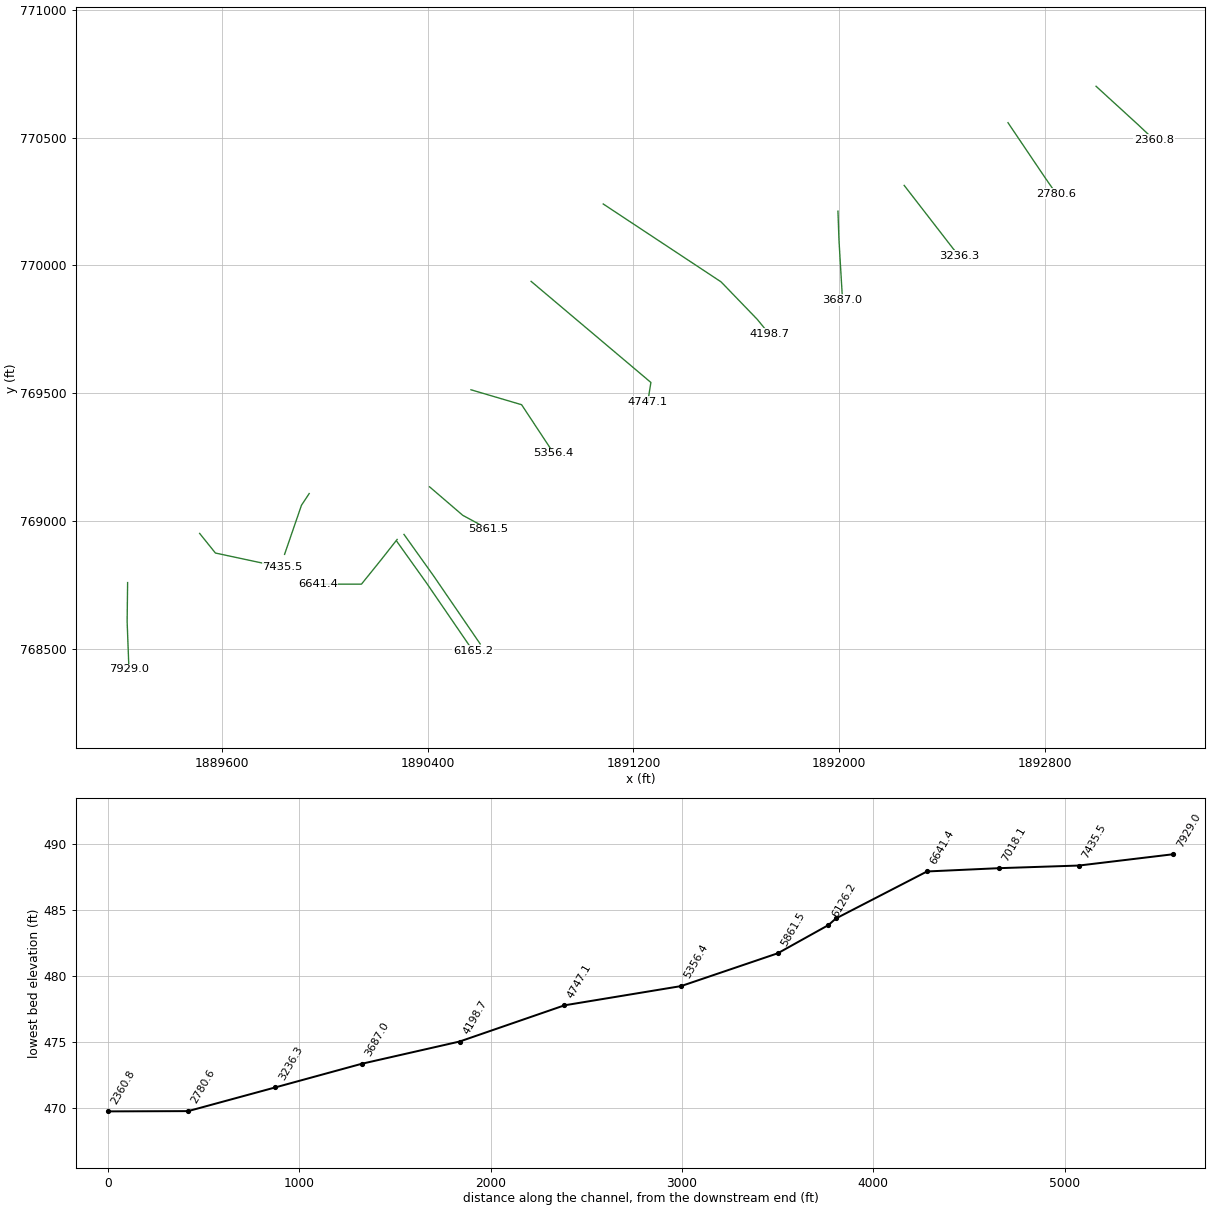
HEC-RAS study PINE HILL BRANCH.PRJ: Pine Hill Branch

--- PINE HILL BRANCH.g01 (geometry) --- (continued)

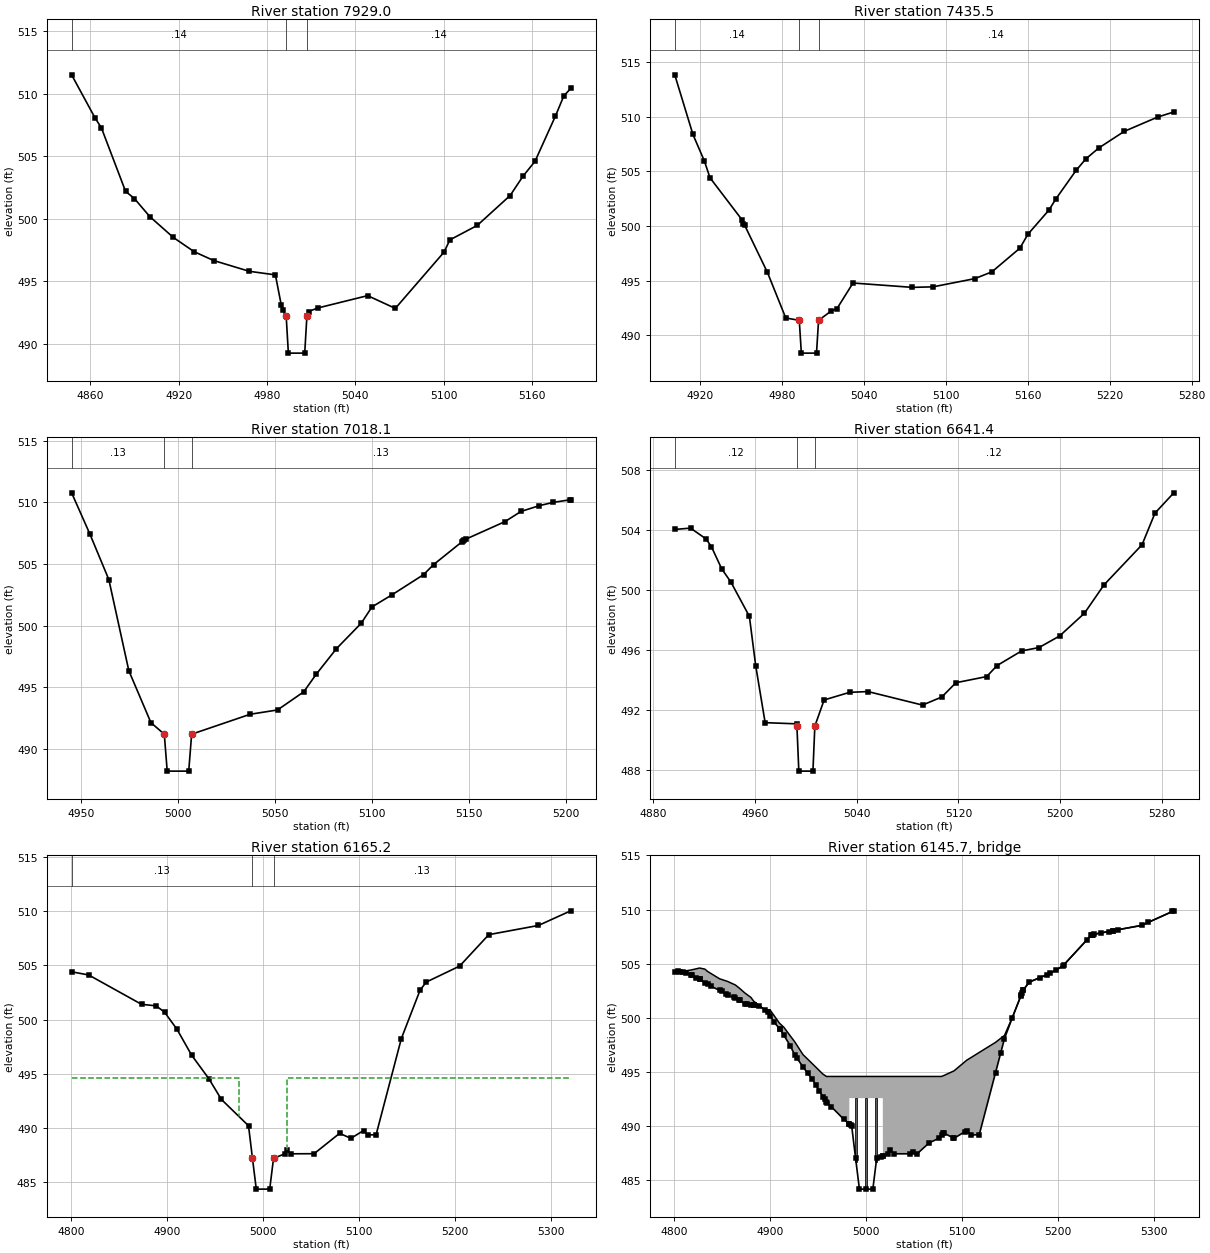
Type RM Length L Ch R = 1 ,7929.0,493.5,493.5,493.5
XS GIS Cut Line= 3
      1889232.73       768761.03      1889230.88       768608.44
      1889237.89       768422.47
BEGIN DESCRIPTION:
Pine Hill Branch 16.0
END DESCRIPTION:
#Sta/Elev= 30
  4847.4   511.5  4863.3  508.05  4867.6  507.26    4884  502.18    4890   501.6
  4900.5  500.15  4916.4  498.49  4930.5  497.35  4943.8  496.64  4967.9  495.78
  4985.7  495.49  4989.7  493.07  4990.8  492.65    4993  492.23  4994.5  489.23
  5005.6  489.23  5007.1  492.23  5008.2  492.56  5014.4  492.84  5048.3  493.83
  5067.1  492.81  5100.2  497.32  5104.1  498.29  5122.7  499.45    5145  501.84
  5153.7  503.38  5161.9  504.58  5175.8  508.21  5181.4   509.8  5186.1  510.41
#Mann= 3 , 1 , 0
 4847.40    0.14       0    4993    0.05       0  5007.1    0.14       0
Bank Sta=4993.00,5007.10
Exp/Cntr=0.3,0.1

Type RM Length L Ch R = 1 ,7435.5,417.4,417.4,417.4
XS GIS Cut Line= 3
      1889512.91       768953.13      1889574.26       768876.44
      1889835.22       768820.41
BEGIN DESCRIPTION:
Pine Hill Branch 15.0
END DESCRIPTION:
#Sta/Elev= 30
  4901.8  513.85  4915.1  508.39  4923.4  505.98  4927.6  504.42  4951.1  500.56
  4951.6  500.19  4952.9  500.09  4969.6  495.76    4983  491.59  4992.9  491.37
  4994.4  488.37  5005.5  488.37    5007  491.37  5016.3  492.23  5020.4  492.43
  5032.2  494.79  5075.7  494.39  5090.8  494.44  5121.3  495.19  5133.8  495.81
  5154.3  497.98  5160.2  499.26  5175.5  501.46  5180.8  502.52  5195.4   505.1
  5202.6  506.16  5212.1  507.16  5230.6  508.67    5255  509.98  5266.9  510.45
#Mann= 3 , 1 , 0
 4901.80    0.14       0  4992.9    0.05       0    5007    0.14       0
Bank Sta=4992.90,5007.00
Exp/Cntr=0.3,0.1

Type RM Length L Ch R = 1 ,7018.1,376.7,376.7,376.7
XS GIS Cut Line= 3
      1889938.96       769108.80      1889908.87       769063.00
      1889843.21       768871.34
BEGIN DESCRIPTION:
Pine Hill Branch 14.0
END DESCRIPTION:
#Sta/Elev= 29
  4945.2  510.78  4954.6  507.44  4964.4  503.73  4974.7  496.33  4986.1  492.11
    4993  491.17  4994.5  488.17  5005.6  488.17  5007.1  491.17  5037.3  492.79
  5051.4  493.14  5064.9  494.61  5071.4  496.05  5081.8  498.12  5094.6  500.19
  5100.1  501.51  5110.4  502.49  5126.7  504.13  5131.9  504.95  5146.3  506.77
  5147.1  506.89  5147.6  506.93  5148.6  507.02  5168.7  508.44    5177  509.27
  5186.5  509.74  5193.5     510  5202.1  510.21  5202.6   510.2
#Mann= 3 , 1 , 0
 4945.20    0.13       0    4993    0.05       0  5007.1    0.13       0
Bank Sta=4993.00,5007.10
Exp/Cntr=0.3,0.1

Type RM Length L Ch R = 1 ,6641.4,476.2,476.2,476.2
XS GIS Cut Line= 4
      1890280.98       768929.54      1890217.39       768848.30
      1890142.36       768754.99      1889972.69       768754.99
BEGIN DESCRIPTION:
Pine Hill Branch 13.0
END DESCRIPTION:
#Sta/Elev= 30
  4896.8  504.02  4909.2  504.11  4921.4  503.39  4925.7  502.86  4933.7   501.4
    4941  500.51  4955.5  498.23  4960.5  494.93  4967.9  491.15  4992.6  491.07
  4992.9  490.92  4994.4  487.92  5005.5  487.92    5007  490.92  5014.3  492.66
  5034.4  493.17  5048.8  493.22  5091.7  492.32  5106.9  492.86    5118  493.81
  5142.2  494.22  5150.3  494.95  5169.7  495.93  5183.3  496.15  5199.5  496.92
  5219.1  498.44  5234.5  500.33  5264.4     503  5274.6  505.11  5289.4  506.46
#Mann= 3 , 1 , 0
 4896.80    0.12       0  4992.9    0.05       0    5007    0.12       0
Bank Sta=4992.90,5007.00
Exp/Cntr=0.5,0.3

Type RM Length L Ch R = 1 ,6165.2,39,39,39
XS GIS Cut Line= 3
      1890279.95       768921.81      1890395.53       768759.08
      1890576.26       768493.95
BEGIN DESCRIPTION:
Upstream Section of Bridge/Culvert/Weir
END DESCRIPTION:
#Sta/Elev= 30
  4800.4  504.41  4818.2  504.12  4873.3  501.41  4888.5  501.27  4897.3  500.69
  4910.4  499.09  4925.6  496.71  4943.5  494.55  4956.6  492.63  4984.9   490.2
    4989   487.2    4993  484.35    5007  484.35    5011   487.2  5022.9  487.61
    5025     488  5028.8  487.61  5053.3  487.62  5079.9   489.5  5091.7  489.04
  5104.9  489.76  5109.5  489.34    5118  489.38  5144.3  498.25  5163.8  502.71
  5170.2  503.46  5205.1  504.94  5235.5  507.84  5287.3  508.69  5320.9  510.04
#Mann= 3 , 1 , 0
 4800.40    0.13       0    4989    0.05       0    5011    0.13       0
#XS Ineff= 2 , 0
       0    4975   494.6    5025       0   494.6
Bank Sta=4989.00,5011.00
Exp/Cntr=0.5,0.3

Type RM Length L Ch R = 3 ,6145.7,,,
BEGIN DESCRIPTION:
Pine Hill Branch - Bethel South Fork Rd
Structure ID: NCF-0067
Approximate Survey Structure
END DESCRIPTION:
Bridge Culvert--1,0,-1,-1, 0
Deck Dist Width WeirC Skew NumUp NumDn MinLoCord MaxHiCord MaxSubmerge Is_Ogee
10,19,2.6,, 57, 57,,,0.95,0,1,1,,
  4800.4  4803.7    4806    4817  4826.3  4831.8  4834.7  4847.1  4855.6  4863.7
  4868.5  4873.3  4879.9  4882.7  4888.5    4894  4897.3  4899.7  4904.2  4909.7
  4914.2    4921  4925.6  4934.1  4943.5  4954.9  4958.6  4976.6 4982.41  4982.5
 5017.39  5017.5  5022.9    5025  5028.8  5046.1  5048.9  5053.3  5065.6  5076.2
  5078.7  5079.9  5081.4  5091.7  5104.9  5109.5    5118    5135  5144.3  5152.3
  5163.8  5170.2  5191.9  5205.1  5235.5  5287.3  5320.9
  504.26   504.3  504.27  504.42  504.61  504.51  504.29  503.62  503.37  503.04
   502.7  502.32  501.89  501.55  501.13  500.77  500.71  500.75  500.19  499.51
  499.14  498.33  497.79  496.62  495.81  494.82   494.6   494.6   494.6   494.6
   494.6   494.6   494.6   494.6   494.6   494.6   494.6   494.6   494.6   494.6
   494.6  494.65   494.7  495.12   496.1  496.35  496.82  497.75  498.39     500
  502.57  503.32  504.12   504.8   507.7  508.55  509.89
  504.26   504.3  504.26  504.01  503.57  503.27  503.11  502.55  502.09  501.82
  501.66  501.26  501.22   501.2  501.12  500.76  500.54  500.21  499.59  499.01
   498.4  497.42  496.56   495.5   494.4  492.73  492.27  490.65  490.23   492.6
   492.6  487.27  487.46  487.85  487.46  487.46   487.6  487.47  488.46  488.91
  489.21  489.35  489.36  488.89  489.61  489.19  489.23  494.96   498.1  499.99
  502.56  503.31  504.11  504.79  507.69  508.54  509.89
  4800.4  4803.7    4806    4817  4826.3  4831.8  4834.7  4847.1  4855.6  4863.7
  4868.5  4873.3  4879.9  4882.7  4888.5    4894  4897.3  4899.7  4904.2  4909.7
  4914.2    4921  4925.6  4934.1  4943.5  4954.9  4958.6  4976.6 4982.41  4982.5
 5017.39  5017.5  5022.9    5025  5028.8  5046.1  5048.9  5053.3  5065.6  5076.2
  5078.7  5079.9  5081.4  5091.7  5104.9  5109.5    5118    5135  5144.3  5152.3
  5163.8  5170.2  5191.9  5205.1  5235.5  5287.3  5320.9
  504.26   504.3  504.27  504.42  504.61  504.51  504.29  503.62  503.37  503.04
   502.7  502.32  501.89  501.55  501.13  500.77  500.71  500.75  500.19  499.51
  499.14  498.33  497.79  496.62  495.81  494.82   494.6   494.6   494.6   494.6
   494.6   494.6   494.6   494.6   494.6   494.6   494.6   494.6   494.6   494.6
   494.6  494.65   494.7  495.12   496.1  496.35  496.82  497.75  498.39     500
  502.57  503.32  504.12   504.8   507.7  508.55  509.89
  504.01  504.05  504.01  503.76  503.32  503.02  502.86   502.3  501.84  501.57
  501.41  501.01  500.97  500.95  500.87  500.51  500.29  499.96  499.34  498.76
  498.15  497.17  496.31  495.25  494.15  492.48  492.02   490.4  489.98  492.35
  492.35  487.02  487.21   487.6  487.21  487.21  487.35  487.22  488.21  488.66
  488.96   489.1  489.11  488.64  489.36  488.94  488.98  494.71  497.85  499.74
  502.31  503.06  503.86  504.54  507.44  508.29  509.64
Pier Skew, UpSta & Num, DnSta & Num=,4989.5, 2 ,4989.5, 2 , 0 , 0 , 0 ,,
     2.5     2.5
   484.8   493.6
     2.5     2.5
  484.55  493.35
Pier Skew, UpSta & Num, DnSta & Num=,5000.0, 2 ,5000.0, 2 , 0 , 0 , 0 ,,
     2.5     2.5
   483.2   493.6
     2.5     2.5
  482.95  493.35
Pier Skew, UpSta & Num, DnSta & Num=,5010.5, 2 ,5010.5, 2 , 0 , 0 , 0 ,,
     2.5     2.5
   484.8   493.6
     2.5     2.5
  484.55  493.35
Abutment Skew #Up #Dn=, 2 , 2
 4982.30 4984.20
  492.60  490.10
 4982.30 4984.20
  492.35  489.85
Abutment Skew #Up #Dn=, 2 , 2
 5015.70 5017.59
  487.21  492.60
 5015.70 5017.59
  486.96  492.35
BR Coef= 1 , 1 , 0 ,1.25, 0 ,,,0.8,0,2,0,
Wspro=,,,, 1 ,,,, 0 ,,,, 0 ,,,,-1 ,-1 ,-1 , 0 , 0 , 0 , 0 , 0
BC Design=,, 0 ,, 0 ,,,,,,
BR U #Sta/Elev= 108
  4800.4  504.26  4803.7   504.3    4806  504.26  4809.4   504.2  4811.9  504.16
    4817  504.01  4818.2  503.97  4822.1  503.73  4826.3  503.57  4826.5  503.56
  4831.8  503.27  4834.7  503.11  4838.1  502.93  4847.1  502.55  4849.5  502.45
    4854  502.18  4855.6  502.09  4861.7  501.89  4863.7  501.82  4867.9  501.68
  4868.5  501.66  4873.3  501.26  4875.3  501.25  4879.9  501.22  4882.6   501.2
  4882.7   501.2  4888.5  501.12    4894  500.76  4897.3  500.54  4899.7  500.21
  4904.2  499.59  4909.7  499.01  4910.4  498.94  4914.2   498.4    4921  497.42
  4925.6  496.56    4928  496.26  4934.1   495.5  4938.9   494.9  4943.5   494.4
  4947.5  493.81    4951   493.3  4954.9  492.73  4956.6  492.48  4958.6  492.27
  4959.6  492.16  4963.8   491.8  4976.6  490.65 4982.41  490.23  4982.5  490.22
  4984.2   490.1  4984.9  490.05    4989  487.05    4993   484.2    5000   484.2
    5007   484.2    5011  487.05  5015.7  487.21 5017.39  487.27  5017.5  487.27
  5022.9  487.46    5025  487.85  5028.8  487.46  5046.1  487.46  5048.9   487.6
  5053.3  487.47  5065.6  488.46  5076.2  488.91  5078.7  489.21  5079.9  489.35
  5081.4  489.36    5091  488.92  5091.7  488.89  5103.1  489.51  5104.9  489.61
  5109.5  489.19    5118  489.23    5135  494.96  5140.4  496.78  5144.3   498.1
  5152.3  499.99  5161.2  502.01  5161.7  502.12  5162.6  502.31  5163.8  502.56
    5164   502.6  5170.2  503.31    5181  503.71  5188.9     504  5191.9  504.11
  5198.2  504.43  5205.1  504.79    5206  504.88    5230  507.19  5234.9  507.66
  5235.3  507.67  5235.5  507.69  5236.1   507.7  5238.1  507.73  5244.7  507.84
  5252.9  507.98    5257  508.05  5257.3  508.06    5263  508.15  5287.3  508.54
  5294.2  508.82  5319.5  509.83  5320.9  509.89
BR U #Mann= 3
 4800.40    0.13    4989    0.05    5011    0.13
BR U Banks=4989.00,5011.00
BR D #Sta/Elev= 108
  4800.4  504.01  4803.7  504.05    4806  504.01  4809.4  503.95  4811.9  503.91
    4817  503.76  4818.2  503.72  4822.1  503.48  4826.3  503.32  4826.5  503.31
  4831.8  503.02  4834.7  502.86  4838.1  502.68  4847.1   502.3  4849.5   502.2
    4854  501.93  4855.6  501.84  4861.7  501.64  4863.7  501.57  4867.9  501.43
  4868.5  501.41  4873.3  501.01  4875.3     501  4879.9  500.97  4882.6  500.95
  4882.7  500.95  4888.5  500.87    4894  500.51  4897.3  500.29  4899.7  499.96
  4904.2  499.34  4909.7  498.76  4910.4  498.69  4914.2  498.15    4921  497.17
  4925.6  496.31    4928  496.01  4934.1  495.25  4938.9  494.65  4943.5  494.15
  4947.5  493.56    4951  493.05  4954.9  492.48  4956.6  492.23  4958.6  492.02
  4959.6  491.91  4963.8  491.55  4976.6   490.4 4982.41  489.98  4982.5  489.97
  4984.2  489.85  4984.9   489.8    4989   486.8    4993  483.95    5000  483.95
    5007  483.95    5011   486.8  5015.7  486.96 5017.39  487.02  5017.5  487.02
  5022.9  487.21    5025   487.6  5028.8  487.21  5046.1  487.21  5048.9  487.35
  5053.3  487.22  5065.6  488.21  5076.2  488.66  5078.7  488.96  5079.9   489.1
  5081.4  489.11    5091  488.67  5091.7  488.64  5103.1  489.26  5104.9  489.36
  5109.5  488.94    5118  488.98    5135  494.71  5140.4  496.53  5144.3  497.85
  5152.3  499.74  5161.2  501.76  5161.7  501.87  5162.6  502.06  5163.8  502.31
    5164  502.35  5170.2  503.06    5181  503.46  5188.9  503.75  5191.9  503.86
  5198.2  504.18  5205.1  504.54    5206  504.63    5230  506.94  5234.9  507.41
  5235.3  507.42  5235.5  507.44  5236.1  507.45  5238.1  507.48  5244.7  507.59
  5252.9  507.73    5257   507.8  5257.3  507.81    5263   507.9  5287.3  508.29
  5294.2  508.57  5319.5  509.58  5320.9  509.64
BR D #Mann= 3
 4800.40    0.13    4989    0.05    5011    0.13
BR D Banks=4989.00,5011.00

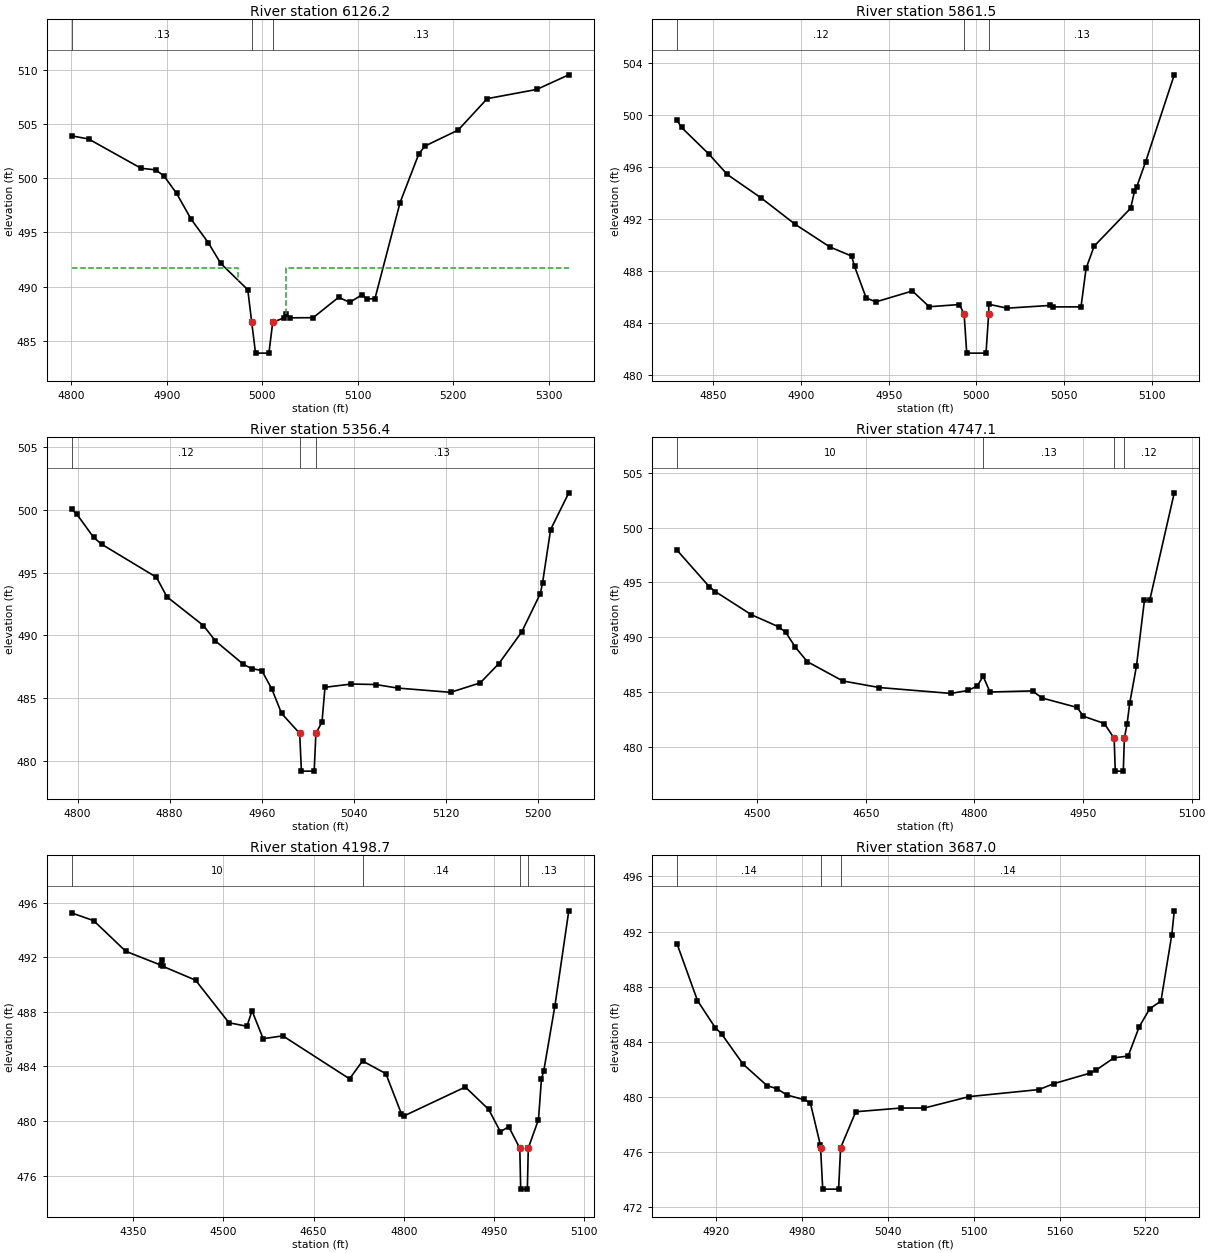
Type RM Length L Ch R = 1 ,6126.2,264.7,264.7,264.7
XS GIS Cut Line= 3
      1890307.70       768949.21      1890423.29       768786.48
      1890604.02       768521.35
BEGIN DESCRIPTION:
Downstream Section of Bridge/Culvert/Weir
END DESCRIPTION:
#Sta/Elev= 30
  4800.4  503.91  4818.2  503.62  4873.3  500.91  4888.5  500.77  4897.3  500.19
  4910.4  498.59  4925.6  496.21  4943.5  494.05  4956.6  492.13  4984.9   489.7
    4989   486.7    4993  483.85    5007  483.85    5011   486.7  5022.9  487.11
    5025   487.5  5028.8  487.11  5053.3  487.12  5079.9     489  5091.7  488.54
  5104.9  489.26  5109.5  488.84    5118  488.88  5144.3  497.75  5163.8  502.21
  5170.2  502.96  5205.1  504.44  5235.5  507.34  5287.3  508.19  5320.9  509.54
#Mann= 3 , 1 , 0
 4800.40    0.13       0    4989    0.05       0    5011    0.13       0
#XS Ineff= 2 , 0
       0    4975  491.75    5025       0  491.75
Bank Sta=4989.00,5011.00
Exp/Cntr=0.5,0.3

Type RM Length L Ch R = 1 ,5861.5,505.1,505.1,505.1
XS GIS Cut Line= 3
      1890407.11       769135.23      1890536.47       769023.74
      1890635.67       768969.77
BEGIN DESCRIPTION:
Pine Hill Branch 12.0
END DESCRIPTION:
#Sta/Elev= 30
  4829.2  499.58  4831.8  499.03  4847.3     497  4857.9  495.42  4877.2  493.62
  4896.7  491.59  4916.4  489.86  4928.8  489.16  4930.5  488.37  4937.1  485.95
  4942.6  485.64  4963.5  486.48  4973.1  485.27  4990.3  485.44    4993  484.71
  4994.5  481.71  5005.5  481.71    5007  484.71  5007.1  485.46  5017.5  485.16
    5042  485.37    5044  485.26  5059.7  485.26  5062.6  488.22  5067.2  489.92
    5088  492.83  5090.2  494.13  5091.5  494.48  5096.5  496.37  5112.9  503.07
#Mann= 3 , 1 , 0
 4829.20    0.12       0    4993    0.05       0    5007    0.13       0
Bank Sta=4993.00,5007.00
Exp/Cntr=0.3,0.1

Type RM Length L Ch R = 1 ,5356.4,609.3,609.3,609.3
XS GIS Cut Line= 3
      1890568.28       769514.36      1890765.13       769456.06
      1890889.70       769266.41
BEGIN DESCRIPTION:
Pine Hill Branch 11.0
END DESCRIPTION:
#Sta/Elev= 30
  4794.7  500.03  4799.4  499.62  4813.9  497.79  4820.8  497.25  4868.5  494.62
  4877.6  493.07  4909.4  490.78  4919.8  489.56    4944  487.71  4951.2  487.37
  4960.1  487.21  4968.9  485.72  4977.3   483.8    4993  482.22  4994.5  479.22
  5005.6  479.22  5007.1  482.22  5012.4  483.12    5015  485.88  5037.9  486.14
  5059.1   486.1  5078.1  485.82  5124.1  485.48  5149.9  486.23  5166.1  487.76
    5186  490.28  5202.2  493.33  5204.1  494.18  5211.1  498.41  5226.9  501.33
#Mann= 3 , 1 , 0
 4794.70    0.12       0    4993    0.05       0  5007.1    0.13       0
Bank Sta=4993.00,5007.10
Exp/Cntr=0.3,0.1

Type RM Length L Ch R = 1 ,4747.1,548.4,548.4,548.4
XS GIS Cut Line= 3
      1890802.13       769938.02      1891268.00       769543.00
      1891256.01       769467.95
BEGIN DESCRIPTION:
Pine Hill Branch 10.0
END DESCRIPTION:
#Sta/Elev= 30
  4389.2  497.95  4433.8  494.61  4442.3  494.16  4491.7  492.06  4529.5  490.95
  4539.4  490.44  4552.7  489.08  4569.2  487.76  4618.2     486  4668.4   485.4
  4767.5  484.86  4790.9  485.13  4803.8  485.53    4812  486.43  4821.5  484.99
  4880.2  485.09  4893.4  484.44  4941.8  483.58  4950.4  482.78  4979.4  482.11
    4993  480.76  4994.5  477.76  5005.6  477.76  5007.1  480.76  5010.9  482.11
  5014.5  483.98  5023.8  487.36  5034.8  493.37  5042.2   493.4    5076  503.19
#Mann= 4 , 1 , 0
 4389.20      10       0    4812    0.13       0    4993    0.05       0
  5007.1    0.12       0
Bank Sta=4993.00,5007.10
Exp/Cntr=0.3,0.1

Type RM Length L Ch R = 1 ,4198.7,511.7,511.7,511.7
XS GIS Cut Line= 4
      1891082.64       770240.36      1891541.08       769935.97
      1891681.38       769789.94      1891728.46       769732.33
BEGIN DESCRIPTION:
Pine Hill Branch 9.0
END DESCRIPTION:
#Sta/Elev= 30
  4247.2  495.25    4284  494.68  4337.3  492.44  4395.8  491.42    4398  491.83
  4399.3  491.33  4453.5  490.32  4509.1   487.2  4538.9  486.94  4547.5  488.07
    4566  486.03  4598.7  486.24  4709.7  483.09  4731.3   484.4  4770.1  483.47
  4795.8  480.55  4801.1  480.39  4902.3  482.49  4941.1  480.85  4960.7  479.21
  4974.4  479.59  4992.9  478.01  4994.4  475.01  5005.5  475.01    5007  478.01
    5024  480.11  5028.9  483.07  5032.8  483.68  5051.4  488.46  5074.4   495.4
#Mann= 4 , 1 , 0
 4247.20      10       0  4731.3    0.14       0  4992.9    0.05       0
    5007    0.13       0
Bank Sta=4992.90,5007.00
Exp/Cntr=0.3,0.1

Type RM Length L Ch R = 1 ,3687.0,450.7,450.7,450.7
XS GIS Cut Line= 3
      1891995.61       770212.34      1891999.42       770101.77
      1892013.37       769865.42
BEGIN DESCRIPTION:
Pine Hill Branch 8.0
END DESCRIPTION:
#Sta/Elev= 30
  4892.7  491.11    4907  486.99  4919.4  485.03  4923.8  484.58  4938.8  482.39
  4955.5  480.83  4962.5   480.6  4969.6  480.14  4981.1  479.82  4985.8   479.6
  4992.9  476.49    4993  476.32  4994.5  473.32  5005.6  473.32    5007  476.32
  5017.6  478.93  5049.1   479.2  5065.5   479.2  5096.9  480.03  5145.6  480.54
    5156  480.97  5180.9  481.72  5185.3  481.94    5198  482.84  5207.9  482.97
  5215.6  485.09  5222.9  486.39  5230.8  486.96  5238.4  491.78  5240.1   493.5
#Mann= 3 , 1 , 0
 4892.70    0.14       0    4993    0.05       0    5007    0.14       0
Bank Sta=4993.00,5007.00
Exp/Cntr=0.3,0.1

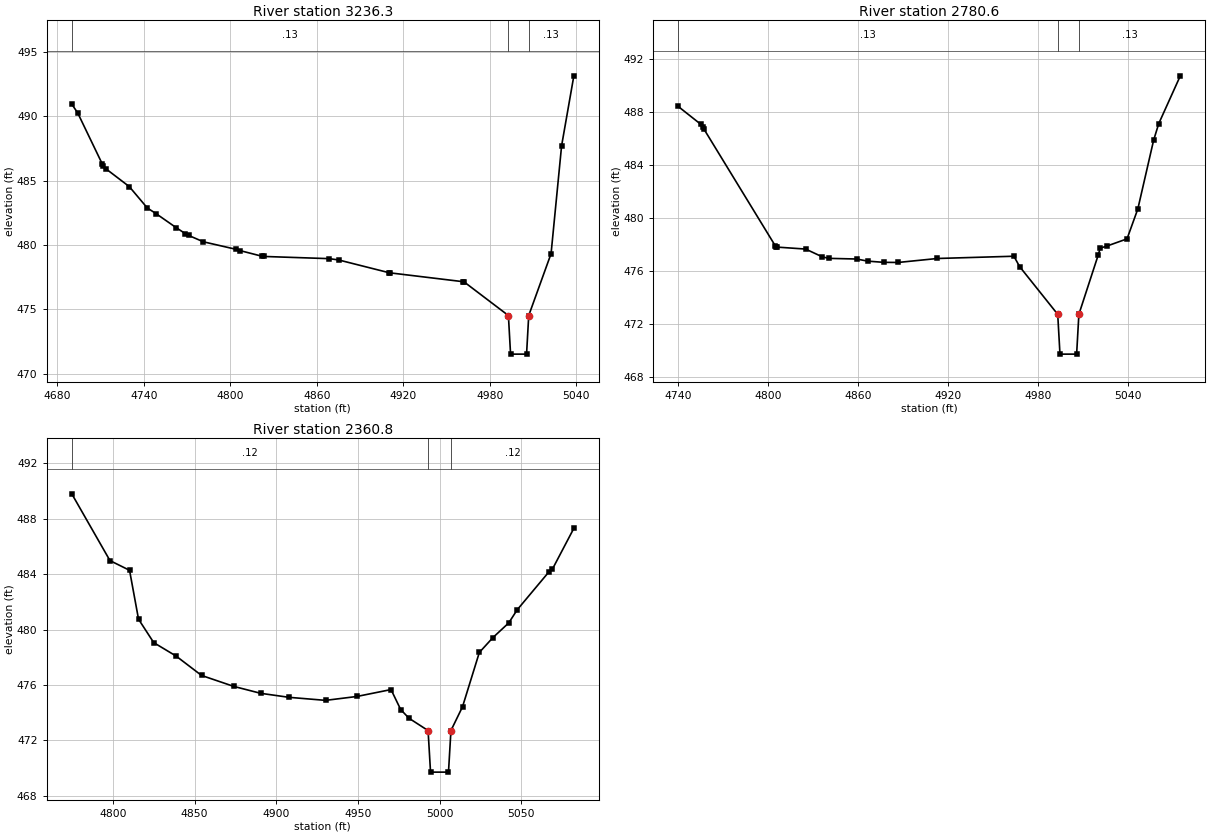
Type RM Length L Ch R = 1 ,3236.3,455.7,455.7,455.7
XS GIS Cut Line= 3
      1892253.18       770313.01      1892442.38       770067.44
      1892466.70       770037.85
BEGIN DESCRIPTION:
Pine Hill Branch 7.0
END DESCRIPTION:
#Sta/Elev= 29
    4690  490.96  4694.1  490.28  4711.2   486.3    4712  486.13  4713.5  485.95
  4729.9  484.55  4742.4  482.89  4748.6  482.44  4762.3  481.37  4768.7   480.9
    4771  480.76  4781.3  480.26  4803.8  479.68  4806.6  479.58  4821.9  479.14
  4823.7  479.12  4868.7  478.95  4875.1  478.85  4910.4  477.85  4910.5  477.85
  4961.5  477.16  4962.2  477.14  4992.9  474.53  4994.4  471.53  5005.5  471.53
    5007  474.53  5022.5  479.34  5029.8  487.72  5038.3  493.16
#Mann= 3 , 1 , 0
 4690.00    0.13       0  4992.9    0.05       0    5007    0.13       0
Bank Sta=4992.90,5007.00
Exp/Cntr=0.3,0.1

Type RM Length L Ch R = 1 ,2780.6,419.8,419.8,419.8
XS GIS Cut Line= 3
      1892656.92       770557.97      1892801.87       770342.13
      1892844.38       770280.82
BEGIN DESCRIPTION:
Pine Hill Branch 6.0
END DESCRIPTION:
#Sta/Elev= 29
    4740   488.4  4755.1  487.05  4756.3  486.83  4757.1   486.7  4804.7  477.89
  4805.3  477.82  4805.6   477.8  4824.9  477.65  4835.9  477.07  4840.2  476.95
  4858.9   476.9  4866.3  476.74  4876.9  476.65  4886.5  476.64  4912.7  476.94
  4963.7  477.11  4967.5  476.33  4992.9  472.73  4994.4  469.73  5005.5  469.73
    5007  472.73    5020  477.24  5021.2  477.72  5025.5  477.87  5039.1  478.42
  5046.3  480.68  5056.8  485.85  5060.2   487.1  5074.6  490.71
#Mann= 3 , 1 , 0
 4740.00    0.13       0  4992.9    0.05       0    5007    0.13       0
Bank Sta=4992.90,5007.00
Exp/Cntr=0.3,0.1

Type RM Length L Ch R = 1 ,2360.8,394.6,394.6,394.6
XS GIS Cut Line= 3
      1892999.51       770700.36      1893163.48       770549.69
      1893225.13       770491.29
BEGIN DESCRIPTION:
Pine Hill Branch 5.0
END DESCRIPTION:
#Sta/Elev= 27
  4774.7   489.8  4798.1  484.98  4810.1  484.28  4815.6  480.75  4824.9  479.06
  4838.6  478.09  4854.2  476.69  4873.9   475.9  4890.4   475.4  4907.8  475.11
  4930.2  474.89  4949.3  475.17  4970.3  475.67  4976.2  474.23  4981.3   473.6
    4993  472.71  4994.5  469.71  5005.5  469.71    5007  472.71  5014.1  474.43
  5024.4  478.35  5032.7  479.42  5042.4  480.48  5047.6  481.43  5067.2  484.19
  5069.2  484.37  5082.3  487.31
#Mann= 3 , 1 , 0
 4774.70    0.12       0    4993   0.045       0    5007    0.12       0
Bank Sta=4993.00,5007.00
Exp/Cntr=0.3,0.1