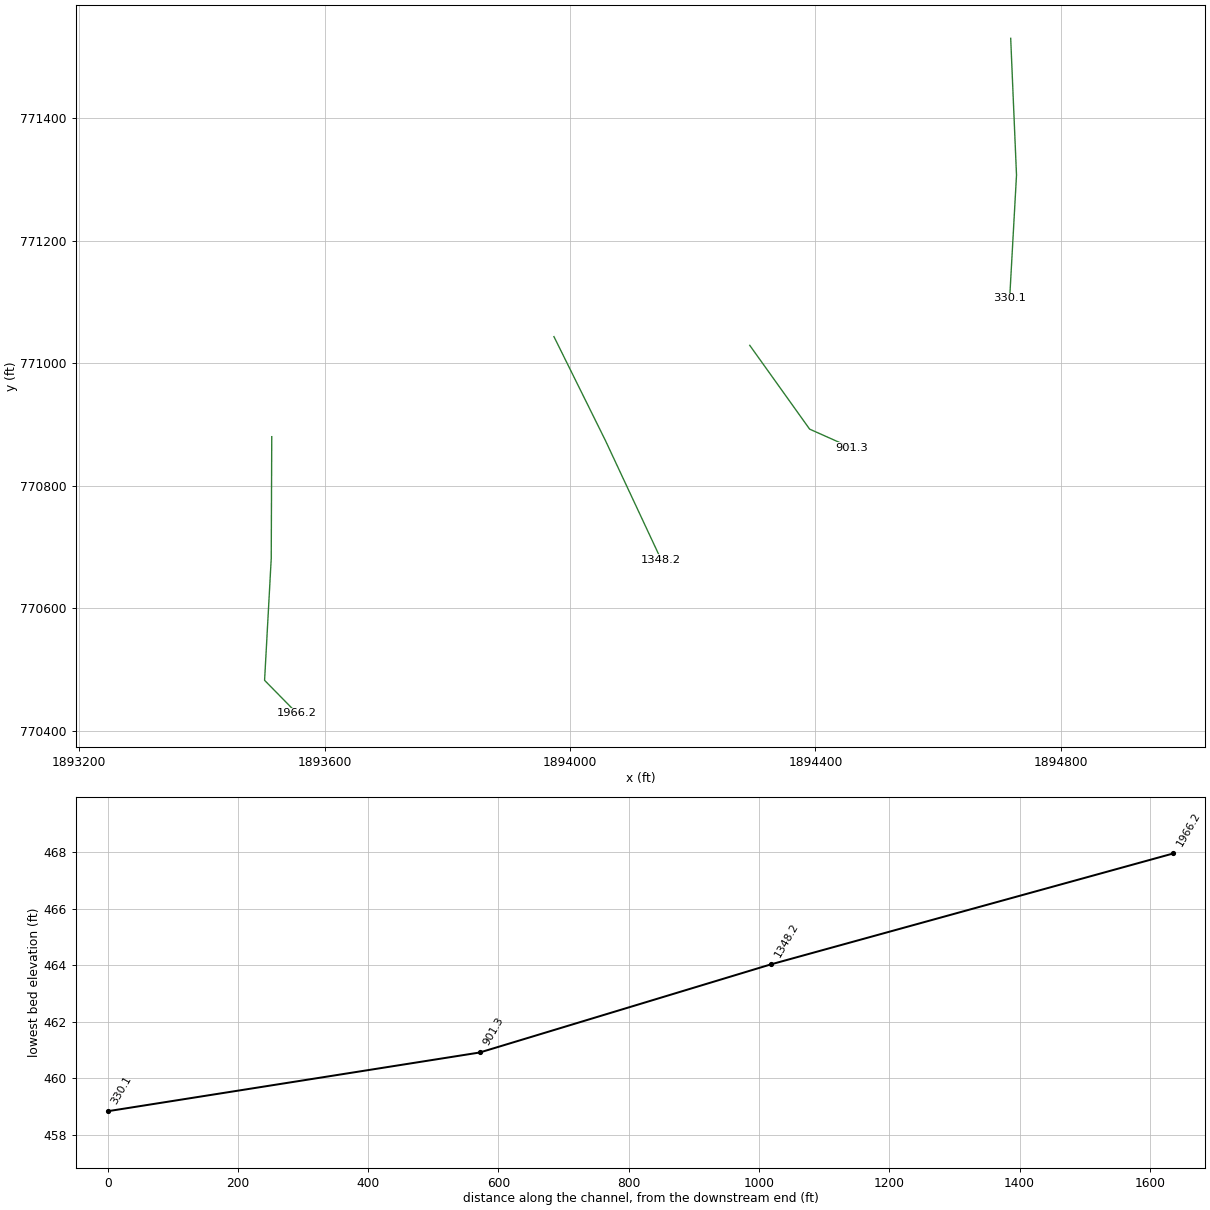
HEC-RAS study PINE HILL BRANCH.PRJ: Pine Hill Branch

--- PINE HILL BRANCH.g01 (geometry) --- (continued)

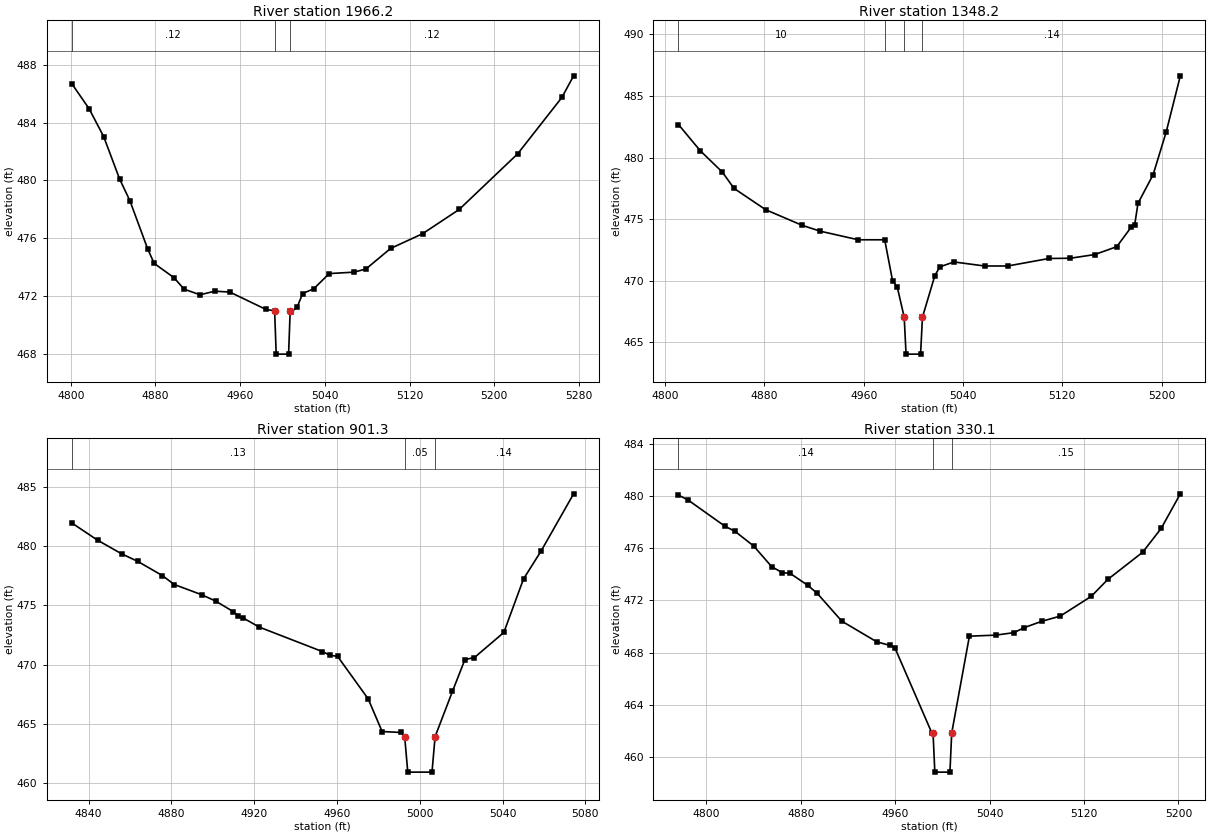
Type RM Length L Ch R = 1 ,1966.2,618,618,618
XS GIS Cut Line= 4
      1893513.71       770880.06      1893512.87       770681.06
      1893502.02       770481.98      1893554.96       770427.98
BEGIN DESCRIPTION:
Pine Hill Branch 4.0
END DESCRIPTION:
#Sta/Elev= 30
    4801   486.7  4817.4  484.96  4831.2  483.02  4846.2  480.09  4855.9  478.59
  4872.8  475.23  4878.9  474.24  4897.5  473.26  4907.1  472.46  4922.2  472.07
    4936  472.32  4950.3  472.26  4984.3  471.06  4992.6  470.96  4994.1  467.96
  5005.8  467.96  5007.3  470.96    5008  470.87  5013.9  471.22  5019.1  472.16
  5029.6  472.49  5044.2  473.54  5067.7  473.64  5078.9  473.86  5102.1  475.28
  5132.3   476.3  5166.9  477.98  5222.2  481.84  5263.9  485.74    5275  487.24
#Mann= 3 , 1 , 0
 4801.00    0.12       0  4992.6   0.045       0  5007.3    0.12       0
Bank Sta=4992.60,5007.30
Exp/Cntr=0.3,0.1

Type RM Length L Ch R = 1 ,1348.2,446.9,446.9,446.9
XS GIS Cut Line= 3
      1893973.78       771043.49      1894057.63       770873.88
      1894148.58       770679.07
BEGIN DESCRIPTION:
Pine Hill Branch 3.0
END DESCRIPTION:
#Sta/Elev= 30
  4810.8  482.68  4828.4  480.55  4846.1  478.82  4855.6  477.49  4881.1  475.76
  4910.3   474.5  4924.9  474.02  4955.6  473.32  4976.9  473.32  4983.2  470.01
  4987.1  469.45  4992.6  467.03  4994.1  464.03  5005.8  464.03  5007.3  467.03
  5017.3  470.41  5021.3  471.12  5032.7  471.52  5057.3  471.19    5076  471.19
  5109.2   471.8  5126.4  471.82  5146.1  472.12  5163.8  472.76  5175.4  474.34
  5178.2  474.51  5180.9  476.28  5193.1  478.61  5203.6  482.07    5215  486.64
#Mann= 4 , 1 , 0
 4810.80      10       0  4976.9    0.13       0  4992.6    0.05       0
  5007.3    0.14       0
Bank Sta=4992.60,5007.30
Exp/Cntr=0.3,0.1

Type RM Length L Ch R = 1 ,901.3,571.2,571.2,571.2
XS GIS Cut Line= 3
      1894293.02       771029.22      1894390.62       770892.37
      1894458.46       770862.06
BEGIN DESCRIPTION:
Pine Hill Branch 2.0
END DESCRIPTION:
#Sta/Elev= 29
  4831.9  481.96  4844.4   480.5    4856  479.35  4863.7  478.72  4875.6  477.52
  4881.4  476.76  4894.6   475.9  4901.4  475.36    4910  474.46  4912.1  474.14
  4914.4  473.96  4922.5  473.16    4953  471.09  4956.7  470.78  4960.3  470.69
  4975.1  467.09  4981.8  464.34  4990.8  464.26  4992.7  463.91  4994.2  460.91
  5005.9  460.91  5007.4  463.91  5015.8  467.74  5021.8  470.42  5026.4  470.59
  5040.6  472.71  5050.1  477.23  5058.5  479.56  5074.3  484.42
#Mann= 3 , 1 , 0
 4831.90    0.13       0  4992.7    0.05       0  5007.4    0.14       0
Bank Sta=4992.70,5007.40
Exp/Cntr=0.3,0.1

Type RM Length L Ch R = 1 ,330.1,0,0,0
XS GIS Cut Line= 3
      1894718.41       771530.84      1894727.88       771307.44
      1894716.73       771106.15
BEGIN DESCRIPTION:
Pine Hill Branch 1.0
END DESCRIPTION:
#Sta/Elev= 30
  4776.4  480.08  4784.3  479.72    4816  477.68  4824.2  477.31  4840.2  476.17
  4855.5  474.58  4864.5  474.13    4871  474.08  4886.1  473.15    4894  472.54
  4914.8  470.41  4944.5  468.82  4955.8  468.55  4959.7  468.38    4991  461.85
  4992.1  461.83  4993.6  458.83  5006.4  458.83  5007.9  461.83  5022.9  469.26
  5045.2  469.34  5060.6  469.53  5069.2  469.91  5084.2   470.4  5099.9   470.8
  5126.2  472.32  5140.1  473.61  5169.7   475.7  5185.4  477.53  5201.6  480.18
#Mann= 3 , 1 , 0
 4776.40    0.14       0  4992.1    0.05       0  5007.9    0.15       0
Bank Sta=4992.10,5007.90
Exp/Cntr=0.3,0.1

Chan Stop Cuts=-1