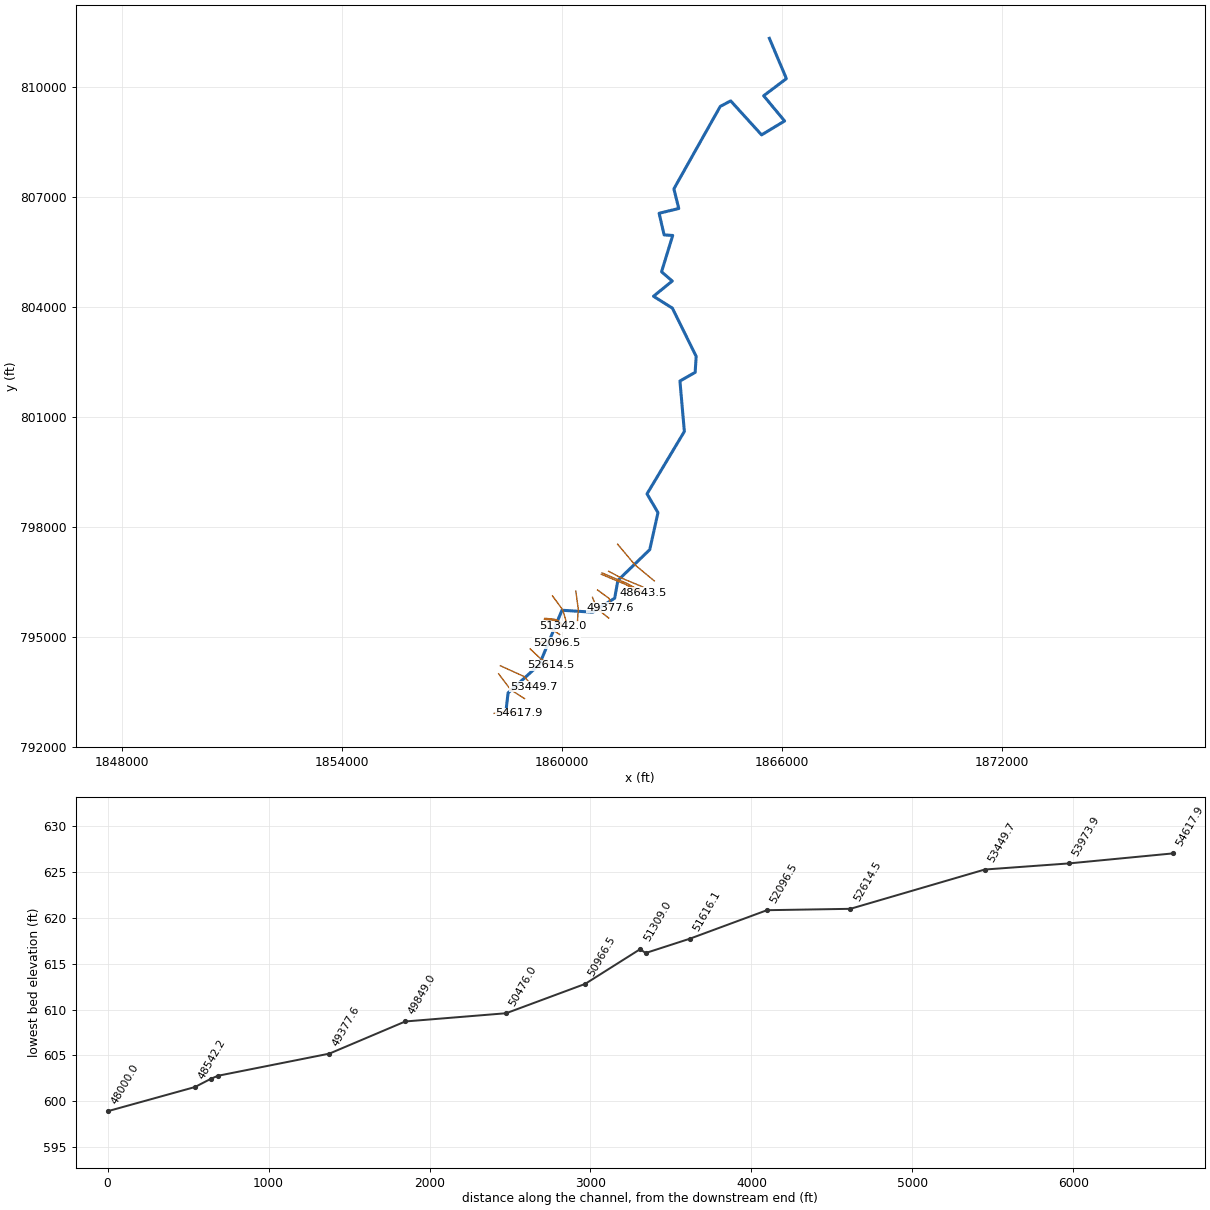
--- ROCK CREEK 1.PRJ (project) ---

Proj Title=Rock Creek 1
Current Plan=p01
Default Exp/Contr=0.3,0.1
English Units
Geom File=g01
Flow File=f01
Plan File=p01
Y Axis Title=Elevation
X Axis Title(PF)=Main Channel Distance
X Axis Title(XS)=Station
BEGIN DESCRIPTION:
####(Watershed Name)####
ROCK CREEK 1
HCFCD Unit X###-##-##
(Flood Hazard, Floodway) Model
10, 2, 1, 0.2% Event
Filename:  N:\NC_flood\60273\Approximates\Eng\Haw-Big_Alamance\Eng\Rock Creek 1\Rock Creek 1.prj
Prepared by:  ________     Date: ________
Reviewed by:  ________     Date: ________
STATUS (Draft RAS, SVSQ, FINAL)
END DESCRIPTION:
DSS Export Rating Curves= 0
DSS Export Rating Curve Sorted= 0
DSS Export Volume Flow Curves= 0
DXF OffsetX= 0
DXF OffsetY= 0
DXF ScaleX= 1
DXF ScaleY= 10

--- ROCK CREEK 1.p01 (plan) ---

Plan Title=Approximate Floodway
Program Version=3.10
Short Identifier=Plan01
Geom File=g01
Flow File=f01
Subcritical Flow
K Sum by GR= 0
Std Step Tol= 0.01
Critical Tol= 0.01
Num of Std Step Trials= 20
Max Error Tol= 0.3
Flow Tol Ratio= 0.001
Split Flow NTrial= 30
Split Flow Tol= 0.02
Split Flow Ratio= 0.02
Log Output Level= 0
Friction Slope Method= 1
Unsteady Friction Slope Method= 2
Parabolic Critical Depth
Global Vel Dist= 0 , 0 , 0
Global Log Level= 0
CheckData=True
Encroach Param=-1 ,10,10, 2
Encroach River=Rock Creek 1
Encroach Reach=Reach - 1
Encroach Node=54617.9
       1  4987.3 5068.71
Encroach Node=53973.9
       1 4918.74 5101.18
Encroach Node=53449.7
       1 4918.21  5061.5
Encroach Node=52614.5
       1  4893.4 5086.35
Encroach Node=52096.5
       1 4945.18 5044.84
Encroach Node=51616.1
       1 4923.85 5025.01
Encroach Node=51342.0
       1    4980    5020
Encroach Node=51325.5
       1    4980    5020
Encroach Node=51309.0
       1    4980    5020
Encroach Node=50966.5
       1  4964.3 5127.12
Encroach Node=50476.0
       1 4860.41  5012.7
Encroach Node=49849.0
       1 4927.41 5061.92
Encroach Node=49377.6
       1 4965.59    5040
Encroach Node=48685.0
       1  4981.5    5110
Encroach Node=48664.2
       1  4981.5    5110
Encroach Node=48643.5
       1  4981.5    5110
Encroach Node=48542.2
       1 4941.31 5144.26
Encroach Node=48000.0
       1 4920.59 5133.06
Encroach Node=47801.2
       1 4872.63 5128.72
Encroach Node=47259.5
       1 4884.29    5080
Encroach Node=47073.7
       1    4900    5070
Encroach Node=47053.7
       4    4900    5070
Encroach Node=47033.7
       1    4900    5070
Encroach Node=46894.2
       1 4853.68 5049.11
Encroach Node=46652.3
       1 4969.55    5070
Encroach Node=46627.3
       4 4969.55    5070
Encroach Node=46602.3
       1 4969.55    5070
Encroach Node=46530.4
       1 4956.15 5055.87
Encroach Node=45976.9
       1 4903.07 5016.72
Encroach Node=45500.0
       1 4859.97  5019.9
Encroach Node=45023.0
       1 4847.81 5233.73
Encroach Node=44443.8
       1 4784.69 5126.24
Encroach Node=43919.3
       1 4785.81 5027.29
Encroach Node=43704.6
       1    4865    5075
Encroach Node=43688.1
       1    4865    5075
Encroach Node=43671.6
       1    4865    5075
Encroach Node=43579.6
       1 4955.82  5146.8
Encroach Node=43138.3
       1 4895.49 5113.86
Encroach Node=42970.3
       1 4927.53 5069.49
Encroach Node=42951.3
       4 4927.53 5069.49
Encroach Node=42932.3
       1 4927.53 5069.49
Encroach Node=42653.3
       1  4835.3 5045.14
Encroach Node=41836.3
       1 4830.54 5095.83
Encroach Node=41097.7
       1 4923.79 5148.28
Encroach Node=40594.6
       1  4916.8 5066.91
Encroach Node=40143.3
       1 4888.64  5048.3
Encroach Node=39916.3
       1 4950.35  5023.3
Encroach Node=39895.8
       1 4950.35  5023.3
Encroach Node=39875.3
       1 4950.35  5023.3
Encroach Node=39564.9
       1 4915.85  5079.1
Encroach Node=39051.7
       1  4931.1  5017.4
Encroach Node=38657.1
       1 4903.85  5017.4
Encroach Node=37770.4
       1 4897.78 5029.87
Encroach Node=37299.6
       1 4942.46 5126.53
Encroach Node=36719.5
       1  4982.4 5100.18
Encroach Node=36176.7
       1 4795.48  5017.6
Encroach Node=35319.0
       1 4970.25  5112.6
Encroach Node=34861.5
       1 4981.12 5069.54
Encroach Node=34564.8
       1    4965    5035
Encroach Node=34545.5
       1    4965    5035
Encroach Node=34526.3
       1    4965    5035
Encroach Node=34351.9
       1    4980 5102.57
Encroach Node=33667.5
       1 4958.51  5017.6
Encroach Node=32991.7
       1 4971.72 5042.91
Encroach Node=32500.0
       1    4975  5017.6
Encroach Node=32139.4
       1    4972  5019.8
Encroach Node=31535.7
       1    4985  5019.8
Encroach Node=30963.3
       1 4971.98  5019.7
Encroach Node=30405.7
       1  4980.2    5045
Encroach Node=29764.7
       1  4980.2    5022
Encroach Node=29295.6
       1 4937.55 5098.64
Encroach Node=28805.9
       1    4800  5020.4
Encroach Node=28351.6
       1  4752.3 5037.77
Encroach Node=27735.1
       1 4757.95 5024.88
Encroach Node=27286.5
       1 4891.11    5180
Encroach Node=26923.3
       1 4972.59 5113.85
Encroach Node=26538.5
       1    4925    5068
Encroach Node=25873.3
       1    4891 5038.84
Encroach Node=25392.1
       1 4977.22    5130
Encroach Node=25024.0
       1 4928.97  5053.6
Encroach Node=24997.0
       1 4928.97  5053.6
Encroach Node=24970.0
       1 4928.97  5053.6
Encroach Node=24785.5
       1 4948.49 5094.65
Computation Interval=1HOUR
Output Interval=1HOUR
Run HTab= 0
Run UNet= 0
Run PostProcess= 0
UNET Theta= 1
UNET Theta Warmup= 1
UNET ZTol= 0.02
UNET ZSATol= 0.05
UNET MxIter= 20
UNET MaxInSteps= 1
UNET DtIC= 0
UNET DtMin= 0
UNET MaxCRTS= 20
UNET WFStab= 2
UNET SFStab= 1
UNET WFX= 1
UNET SFX= 1
UNET DSS MLevel= 4
UNET Convert EG Bridges=-1
UNET Use Existing IB Tables=-1
UNET Froude Reduction=False
UNET Froude Limit= 1
UNET Froude Power= 10
Instantaneous Interval=1HOUR
Write IC File= 0
Echo Input=False
Echo Output=False
Write Detailed= 0

--- ROCK CREEK 1.f01 (steady flow) ---

Flow Title= Approximate Floodway
Number of Profiles= 2
Profile Names=100-Year,AFW
River Rch & RM=Rock Creek 1,Reach - 1,54617.9
    1290    1290
River Rch & RM=Rock Creek 1,Reach - 1,49849
    2130    2130
River Rch & RM=Rock Creek 1,Reach - 1,45500
    2260    2260
River Rch & RM=Rock Creek 1,Reach - 1,41097.7
    2550    2550
River Rch & RM=Rock Creek 1,Reach - 1,37770.4
    2630    2630
River Rch & RM=Rock Creek 1,Reach - 1,32139.4
    3500    3500
River Rch & RM=Rock Creek 1,Reach - 1,28805.9
    3720    3720
Boundary for River Rch & Prof#=Rock Creek 1,Reach - 1, 1
Up Type= 0
Dn Type= 1
Dn Known WS=537.00
Boundary for River Rch & Prof#=Rock Creek 1,Reach - 1, 2
Up Type= 0
Dn Type= 1
Dn Known WS=537.70

--- ROCK CREEK 1.g01 (geometry) ---

Geom Title=Geom 01 by CodeH2 for Windows
Program Version=3.10

River Reach=Rock Creek 1    ,Reach - 1
Reach XY= 30
      1858475.88       792964.47      1858534.62       793472.19
      1859388.87       794247.31      1860004.88       795725.94
      1860846.37       795672.94      1861443.37       796055.81
      1861530.63       796539.44      1862400.13       797378.81
      1862624.12       798387.75       1862325.5       798898.25
      1863344.13       800598.31       1863223.5        801974.5
      1863638.13       802210.12      1863666.38       802646.63
        1863017.       803961.75        1862502.         804285.
      1863013.38       804700.56        1862722.       804952.63
      1863026.13       805942.62       1862791.5       805958.12
      1862655.38       806547.19       1863191.5       806677.81
      1863058.12       807212.06       1864322.5       809459.19
      1864607.25        809611.5       1865450.5       808684.37
      1866078.88        809063.5      1865507.13       809750.88
       1866127.5       810217.44      1865663.38       811316.13

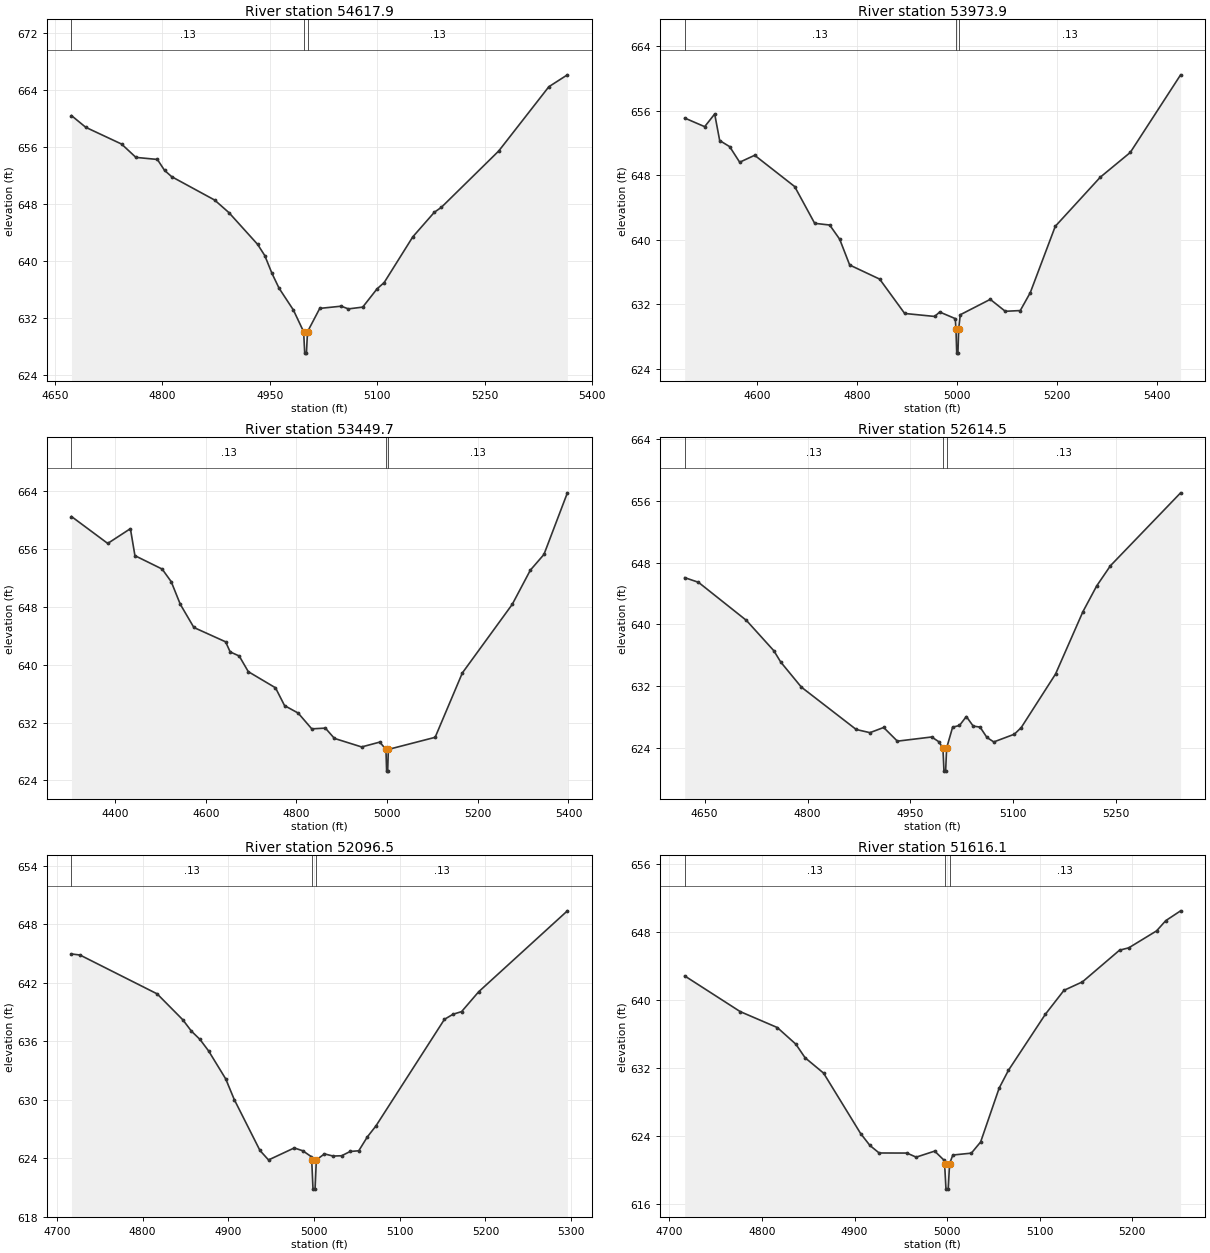
Type RM Length L Ch R = 1 ,54617.9 ,644,644,644
BEGIN DESCRIPTION:
Rock Creek 1 85.0
END DESCRIPTION:
XS GIS Cut Line= 3
      1858152.66       792915.09      1858475.67       792964.53
      1858838.22       792915.09
#Sta/Elev= 30
    4673   660.4    4693  658.75    4743   656.4    4763  654.53    4793  654.24
    4803  652.71    4813  651.82    4873  648.54    4893  646.77    4933  642.32
    4943  640.75    4953  638.26    4963  636.16    4983   633.1  4997.3  630.05
  4998.8  627.05  5001.2  627.05  5002.7  630.05  5019.8  633.33  5049.8  633.64
  5059.8  633.26  5079.8  633.51  5099.8  636.07  5109.8  636.96  5149.8  643.38
  5179.8  646.82  5189.8  647.53  5269.8  655.43  5339.8  664.45  5365.7  666.12
#Mann= 3 , 1 , 0
    4673     .13       0  4997.3    .045       0  5002.7     .13       0
Bank Sta=4997.3,5002.7
XS Rating Curve= 0
Exp/Cntr=0.3,0.1

Type RM Length L Ch R = 1 ,53973.9 ,524.2,524.2,524.2
BEGIN DESCRIPTION:
Rock Creek 1 84.0
END DESCRIPTION:
XS GIS Cut Line= 3
      1858277.91       793992.87      1858604.21        793561.1
      1858983.25        793317.2
#Sta/Elev= 30
  4454.7  655.12  4494.7  654.05  4514.7  655.62  4524.7  652.33  4544.7  651.57
  4564.7  649.64  4594.7   650.5  4674.7  646.62  4714.7  642.06  4744.7  641.85
  4764.7  640.09  4784.7  636.89  4844.7  635.14  4894.7  630.88  4954.7  630.51
  4964.7  631.06  4995.9  630.24  4997.3  628.96  4998.8  625.96  5001.2  625.96
  5002.7  628.96  5005.9  630.72  5065.9  632.63  5095.9  631.15  5125.9  631.24
  5145.9  633.46  5195.9  641.69  5285.9  647.78  5345.9  650.85  5446.6  660.48
#Mann= 3 , 1 , 0
  4454.7     .13       0  4997.3    .045       0  5002.7     .13       0
Bank Sta=4997.3,5002.7
XS Rating Curve= 0
Exp/Cntr=0.3,0.1

Type RM Length L Ch R = 1 ,53449.7 ,835.2,835.2,835.2
BEGIN DESCRIPTION:
Rock Creek 1 83.0
END DESCRIPTION:
XS GIS Cut Line= 3
      1858324.05        794213.7      1858963.47       793923.66
      1859233.74        793640.2
#Sta/Elev= 30
  4303.8  660.46  4383.8  656.74  4433.8  658.78  4443.8  655.05  4503.8   653.2
  4523.8  651.46  4543.8  648.34  4573.8  645.13  4643.8  643.15  4653.8  641.76
  4673.8  641.19  4693.8  639.03  4753.8   636.8  4773.8  634.34  4803.8  633.31
  4833.8  631.13  4863.8  631.23  4883.8  629.81  4943.8  628.63  4983.8   629.3
  4997.4  628.29  4998.9  625.29  5001.2  625.29  5002.7  628.29  5105.9  629.96
  5165.9  638.85  5275.9  648.32  5315.9  653.05  5345.9  655.22  5397.6  663.73
#Mann= 3 , 1 , 0
  4303.8     .13       0  4997.4    .045       0  5002.7     .13       0
Bank Sta=4997.4,5002.7
XS Rating Curve= 0
Exp/Cntr=0.3,0.1

Type RM Length L Ch R = 1 ,52614.5 ,518,518,518
BEGIN DESCRIPTION:
Rock Creek 1 81.0
END DESCRIPTION:
XS GIS Cut Line= 3
      1859137.83       794672.83      1859414.69       794411.79
      1859699.46       794221.94
#Sta/Elev= 30
  4620.9  646.05  4640.9  645.45  4710.9  640.51  4750.9  636.58  4760.9  635.12
  4790.9  631.88  4870.9  626.39  4890.9  625.98  4910.9  626.65  4930.9  624.88
  4980.9  625.42  4990.9  624.83  4997.3     624  4998.8     621  5001.2     621
  5002.7     624  5011.4  626.69  5021.4  626.91  5031.4  628.07  5041.4  626.83
  5051.4   626.7  5061.4  625.36  5071.4  624.78  5101.4  625.78  5111.4  626.64
  5161.4  633.57  5201.4  641.66  5221.4  644.98  5241.4  647.59  5343.7  657.03
#Mann= 3 , 1 , 0
  4620.9     .13       0  4997.3    .045       0  5002.7     .13       0
Bank Sta=4997.3,5002.7
XS Rating Curve= 0
Exp/Cntr=0.3,0.1

Type RM Length L Ch R = 1 ,52096.5 ,480.4,480.4,480.4
BEGIN DESCRIPTION:
Rock Creek 1 80.0
END DESCRIPTION:
XS GIS Cut Line= 3
      1859288.12       794836.31      1859570.26        794878.5
       1859860.3       794833.68
#Sta/Elev= 30
  4716.9  644.95  4726.9  644.84  4816.9  640.86  4846.9   638.2  4856.9  637.04
  4866.9  636.19  4876.9  635.02  4896.9  632.15  4906.9  630.03  4936.9  624.81
  4946.9  623.84  4976.9  625.07  4986.9  624.78  4996.9  624.17  4997.3  623.85
  4998.8  620.85  5001.2  620.85  5002.7  623.85  5012.2  624.46  5022.2  624.24
  5032.2  624.27  5042.2  624.71  5052.2  624.78  5062.2   626.2  5072.2  627.32
  5152.2  638.25  5162.2  638.77  5172.2  639.04  5192.2  641.08  5295.7  649.37
#Mann= 3 , 1 , 0
  4716.9     .13       0  4997.3    .045       0  5002.7     .13       0
Bank Sta=4997.3,5002.7
XS Rating Curve= 0
Exp/Cntr=0.3,0.1

Type RM Length L Ch R = 1 ,51616.1 ,274.1,274.1,274.1
BEGIN DESCRIPTION:
Rock Creek 1 79.0
END DESCRIPTION:
XS GIS Cut Line= 3
      1859475.33       795326.75      1859726.17       795203.32
      1859942.04       795065.71
#Sta/Elev= 30
  4716.6   642.8  4776.6   638.6  4816.6  636.73  4836.6  634.78  4846.6  633.18
  4866.6  631.37  4906.6  624.27  4916.6  622.87  4926.6  621.98  4956.6  621.97
  4966.6  621.49  4986.6   622.2  4996.2  621.18  4997.3  620.73  4998.8  617.73
  5001.2  617.73  5002.7  620.73  5006.2  621.74  5026.2  621.96  5036.2  623.27
  5056.2   629.6  5066.2  631.69  5106.2   638.3  5126.2   641.1  5146.2   642.1
  5186.2  645.82  5196.2   646.1  5226.2  648.09  5236.2   649.3  5252.2  650.45
#Mann= 3 , 1 , 0
  4716.6     .13       0  4997.3    .045       0  5002.7     .13       0
Bank Sta=4997.3,5002.7
XS Rating Curve= 0
Exp/Cntr=0.5,0.3

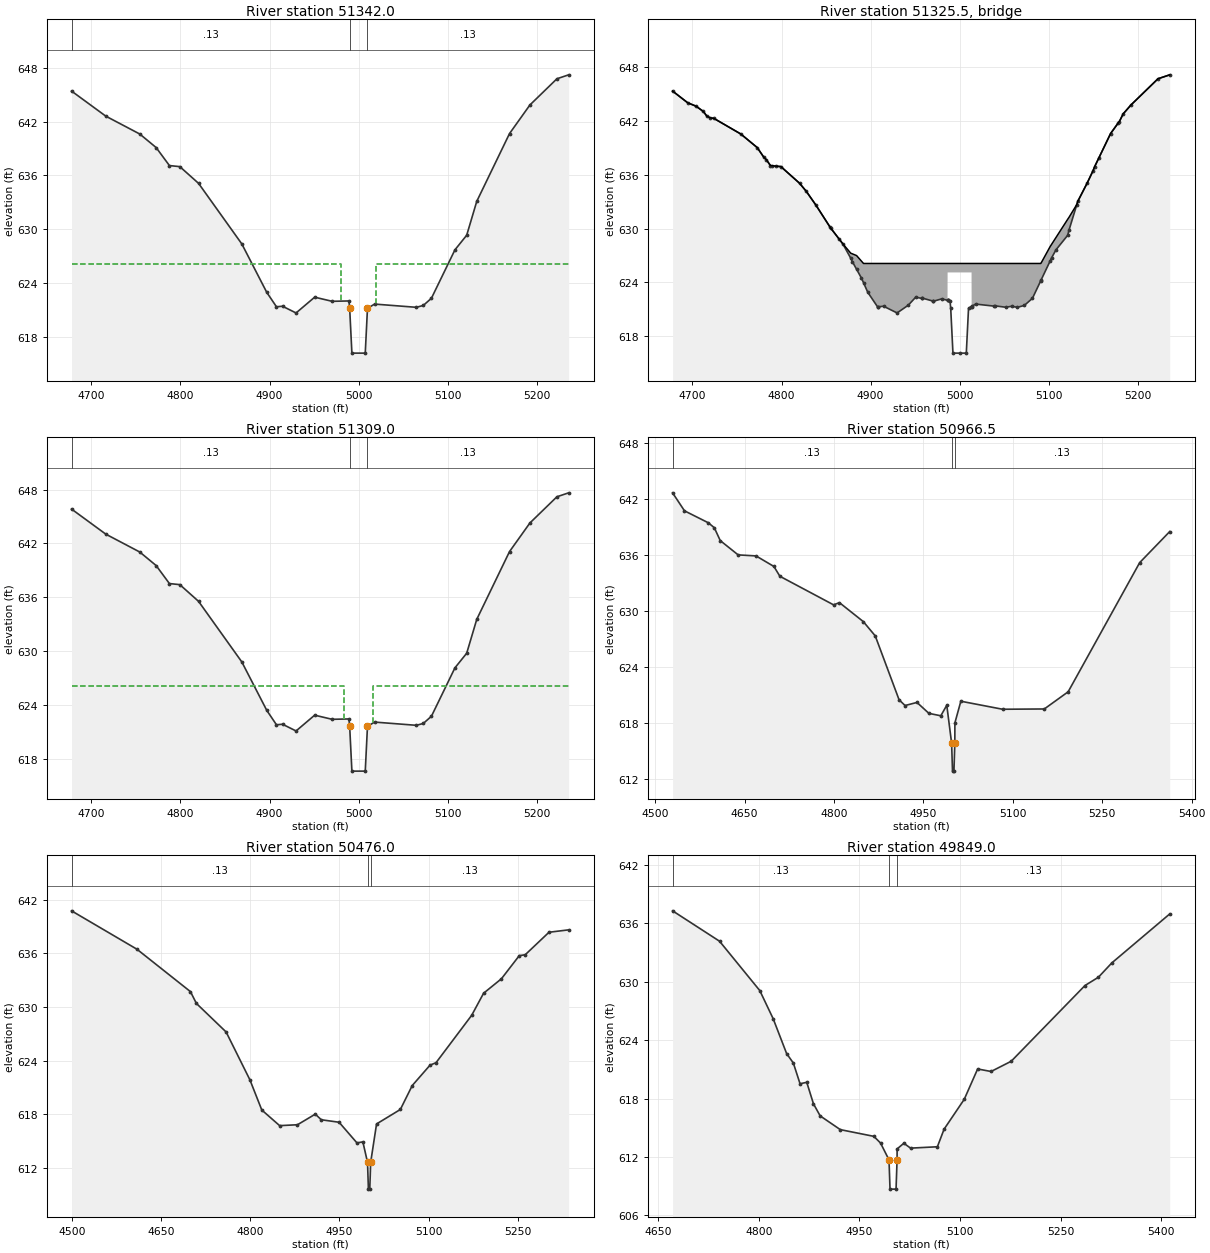
Type RM Length L Ch R = 1 ,51342.0 ,33,33,33
BEGIN DESCRIPTION:
Upstream Section of Bridge/Culvert/Weir
END DESCRIPTION:
XS GIS Cut Line= 5
      1859526.88         795479.      1859747.71       795458.61
      1859836.33       795439.28      1859879.84       795411.88
      1860030.23       795288.85
#Sta/Elev= 30
  4677.7   645.4  4716.2   642.6  4754.3  640.61  4772.7   639.1  4787.6  637.09
  4799.3  636.97  4820.3  635.11  4868.9  628.35  4896.9  622.95  4907.8  621.34
  4914.6   621.4  4929.8  620.65  4950.7  622.41  4970.3  621.95  4989.2  621.99
    4990  621.17  4992.5  616.17  5007.5  616.17    5010  621.17    5018  621.64
  5064.9  621.28  5072.7  621.49  5081.8  622.29  5108.2  627.69  5121.4  629.32
  5132.7   633.1  5169.5  640.66  5192.4  643.85  5222.7  646.77  5235.9  647.21
#Mann= 3 , 1 , 0
  4677.7     .13       0    4990    .045       0    5010     .13       0
#XS Ineff= 2 , 0
       0    4980   626.1    5020       0   626.1
Permanent Ineff=
       F       F
Bank Sta=4990,5010
XS Rating Curve= 0
Exp/Cntr=0.5,0.3

Type RM Length L Ch R = 3 ,51325.5 ,,,
BEGIN DESCRIPTION:
Siler Rd - TOR
Structure ID: Siler Rd
Approximate Survey Structure
END DESCRIPTION:
Bridge Culvert--1,0,-1,-1, 0
Deck Dist Width WeirC Skew NumUp NumDn MinLoCord MaxHiCord MaxSubmerge Is_Ogee
10,13,2.6,0, 58, 58, , , 0.95, 0, 1,1,,
  4677.7  4694.7  4704.1  4712.3  4716.2  4719.7  4724.1  4754.3  4772.7  4779.8
    4783  4787.6  4799.3  4820.3  4827.9  4838.6  4855.1  4868.9  4877.7  4884.3
  4889.7  4892.1  4896.9  4907.8  4914.6  4929.8  4942.4  4950.7  4958.3  4970.3
  4979.9 4986.41  4986.5 5013.39  5013.5    5018  5051.6  5058.3  5064.9  5072.7
  5081.8    5091  5091.6  5101.6  5108.2  5121.4    5123  5131.6  5132.7  5143.3
  5149.9  5151.6  5169.5  5179.3  5183.6  5192.4  5222.7  5235.9
  645.33  644.02  643.64  643.05  642.53  642.35  642.28  640.54  639.03     638
  637.67  637.02  636.91  635.05  634.14  632.62  630.07  628.29  627.25  626.98
  626.37   626.1   626.1   626.1   626.1   626.1   626.1   626.1   626.1   626.1
   626.1   626.1   626.1   626.1   626.1   626.1   626.1   626.1   626.1   626.1
   626.1   626.1  626.17  627.98     629  631.04  631.28  632.68  633.04  635.09
  636.47   636.9  640.59  641.92  642.78  643.78   646.7  647.14
  645.33  644.02  643.64  643.05  642.53  642.35  642.28  640.54  639.03     638
  637.67  637.02   636.9  635.04  634.13  632.61  630.06  628.28  626.69  625.45
  624.48  623.95  622.88  621.27  621.33  620.58  621.45  622.34  622.23  621.88
  622.15  621.99   625.1   625.1  621.31  621.57  621.22  621.32  621.21  621.42
  622.22  624.15  624.28  626.37  627.62  629.25  629.88  632.67  633.03  635.08
  636.46  636.89  640.59  641.92  642.78  643.78   646.7  647.14
  4677.7  4694.7  4704.1  4712.3  4716.2  4719.7  4724.1  4754.3  4772.7  4779.8
    4783  4787.6  4799.3  4820.3  4827.9  4838.6  4855.1  4868.9  4877.7  4884.3
  4889.7  4892.1  4896.9  4907.8  4914.6  4929.8  4942.4  4950.7  4958.3  4970.3
  4979.9 4986.41  4986.5 5013.39  5013.5    5018  5051.6  5058.3  5064.9  5072.7
  5081.8    5091  5091.6  5101.6  5108.2  5121.4    5123  5131.6  5132.7  5143.3
  5149.9  5151.6  5169.5  5179.3  5183.6  5192.4  5222.7  5235.9
  645.33  644.02  643.64  643.05  642.53  642.35  642.28  640.54  639.03     638
  637.67  637.02  636.91  635.05  634.14  632.62  630.07  628.29  627.25  626.98
  626.37   626.1   626.1   626.1   626.1   626.1   626.1   626.1   626.1   626.1
   626.1   626.1   626.1   626.1   626.1   626.1   626.1   626.1   626.1   626.1
   626.1   626.1  626.17  627.98     629  631.04  631.28  632.68  633.04  635.09
  636.47   636.9  640.59  641.92  642.78  643.78   646.7  647.14
  645.08  643.77  643.39   642.8  642.28   642.1  642.03  640.29  638.78  637.75
  637.42  636.77  636.65  634.79  633.88  632.36  629.81  628.03  626.44   625.2
  624.23   623.7  622.63  621.02  621.08  620.33   621.2  622.09  621.98  621.63
   621.9  621.74  624.85  624.85  621.06  621.32  620.97  621.07  620.96  621.17
  621.97   623.9  624.03  626.12  627.37     629  629.63  632.42  632.78  634.83
  636.21  636.64  640.34  641.67  642.53  643.53  646.45  646.89
BR Coef= 1 , 1 , 0 ,1.25, 0 ,,,0.8,0,2,0,
WSPro=,,,, 1 ,,,, 0 ,,,, 0 ,,,,-1 ,-1 ,-1 , 0 , 0 , 0 , 0 , 0
BR U #Sta/Elev= 79
  4677.7  645.33  4694.7  644.02  4704.1  643.64  4712.3  643.05  4716.2  642.53
  4719.7  642.35  4724.1  642.28  4754.3  640.54  4772.7  639.03  4779.8     638
    4783  637.67  4787.6  637.02  4788.9  636.97  4794.3  636.93  4799.3   636.9
  4820.3  635.04  4827.9  634.13  4838.6  632.61  4854.3  630.18  4855.1  630.06
  4864.3  628.87  4868.9  628.28  4877.7  626.69  4879.5  626.31  4884.3  625.45
  4889.7  624.48  4892.1  623.95  4896.9  622.88  4907.8  621.27  4908.1  621.26
  4914.6  621.33  4929.8  620.58  4942.4  621.45  4950.7  622.34  4957.2  622.21
  4958.3  622.23  4969.9  621.91  4970.3  621.88  4979.9  622.15 4986.41  621.99
  4986.5  621.99  4986.6  621.98  4989.2  621.92    4990   621.1  4992.5   616.1
    5000   616.1  5007.5   616.1    5010   621.1  5013.3  621.29 5013.39   621.3
  5013.5  621.31    5018  621.57  5038.8  621.34  5039.9  621.37  5051.6  621.22
  5058.3  621.32  5064.9  621.21  5072.7  621.42  5081.8  622.22    5091  624.15
  5091.6  624.28  5101.6  626.37  5103.4  626.75  5108.2  627.62  5121.4  629.25
    5123  629.88  5131.6  632.67  5132.7  633.03  5143.3  635.08  5149.9  636.46
  5151.6  636.89  5156.1  637.82  5169.5  640.59  5177.6  641.73  5179.3  641.92
  5183.6  642.78  5192.4  643.78  5222.7   646.7  5235.9  647.14
BR U #Mann= 3
  4677.7     .13    4990    .045    5010     .13
BR U Banks=4990,5010
BR D #Sta/Elev= 79
  4677.7  645.08  4694.7  643.77  4704.1  643.39  4712.3   642.8  4716.2  642.28
  4719.7   642.1  4724.1  642.03  4754.3  640.29  4772.7  638.78  4779.8  637.75
    4783  637.42  4787.6  636.77  4788.9  636.72  4794.3  636.68  4799.3  636.65
  4820.3  634.79  4827.9  633.88  4838.6  632.36  4854.3  629.93  4855.1  629.81
  4864.3  628.62  4868.9  628.03  4877.7  626.44  4879.5  626.06  4884.3   625.2
  4889.7  624.23  4892.1   623.7  4896.9  622.63  4907.8  621.02  4908.1  621.01
  4914.6  621.08  4929.8  620.33  4942.4   621.2  4950.7  622.09  4957.2  621.96
  4958.3  621.98  4969.9  621.66  4970.3  621.63  4979.9   621.9 4986.41  621.74
  4986.5  621.74  4986.6  621.73  4989.2  621.67    4990  620.85  4992.5  615.85
    5000  615.85  5007.5  615.85    5010  620.85  5013.3  621.04 5013.39  621.05
  5013.5  621.06    5018  621.32  5038.8  621.09  5039.9  621.12  5051.6  620.97
  5058.3  621.07  5064.9  620.96  5072.7  621.17  5081.8  621.97    5091   623.9
  5091.6  624.03  5101.6  626.12  5103.4   626.5  5108.2  627.37  5121.4     629
    5123  629.63  5131.6  632.42  5132.7  632.78  5143.3  634.83  5149.9  636.21
  5151.6  636.64  5156.1  637.57  5169.5  640.34  5177.6  641.48  5179.3  641.67
  5183.6  642.53  5192.4  643.53  5222.7  646.45  5235.9  646.89
BR D #Mann= 3
  4677.7     .13    4990    .045    5010     .13
BR D Banks=4990,5010
BC Design=,, 0 ,, 0 ,,,,,,
BC HTab HWMax=647.21

Type RM Length L Ch R = 1 ,51309.0 ,342.5,342.5,342.5
BEGIN DESCRIPTION:
Downstream Section of Bridge/Culvert/Weir
END DESCRIPTION:
XS GIS Cut Line= 5
      1859545.01       795506.58      1859765.85       795486.19
      1859854.47       795466.86      1859897.98       795439.46
      1860048.36       795316.43
#Sta/Elev= 30
  4677.7  645.83  4716.2  643.03  4754.3  641.04  4772.7  639.53  4787.6  637.52
  4799.3   637.4  4820.3  635.54  4868.9  628.78  4896.9  623.38  4907.8  621.77
  4914.6  621.83  4929.8  621.08  4950.7  622.84  4970.3  622.38  4989.2  622.42
    4990   621.6  4992.5   616.6  5007.5   616.6    5010   621.6    5018  622.07
  5064.9  621.71  5072.7  621.92  5081.8  622.72  5108.2  628.12  5121.4  629.75
  5132.7  633.53  5169.5  641.09  5192.4  644.28  5222.7   647.2  5235.9  647.64
#Mann= 3 , 1 , 0
  4677.7     .13       0    4990    .045       0    5010     .13       0
#XS Ineff= 2 , 0
       0 4983.33   626.1 5016.67       0   626.1
Permanent Ineff=
       F       F
Bank Sta=4990,5010
XS Rating Curve= 0
Exp/Cntr=0.5,0.3

Type RM Length L Ch R = 1 ,50966.5 ,490.5,490.5,490.5
BEGIN DESCRIPTION:
Rock Creek 1 78.0
END DESCRIPTION:
XS GIS Cut Line= 3
      1859746.92       796117.79      1860026.42       795735.45
      1860129.26       795390.04
#Sta/Elev= 30
  4529.2  642.62  4549.2  640.69  4589.2  639.41  4599.2  638.88  4609.2   637.5
  4639.2  635.97  4669.2  635.86  4699.2  634.73  4709.2  633.68  4799.2  630.62
  4809.2  630.85  4849.2  628.82  4869.2  627.29  4909.2  620.44  4919.2  619.83
  4939.2  620.16  4959.2  618.99  4979.2  618.73  4989.2  619.86  4997.3   615.8
  4998.8   612.8  5001.2   612.8  5002.7   615.8  5002.8  617.97  5012.8  620.29
  5082.8  619.43  5152.8  619.46  5192.8   621.3  5312.8  635.14  5363.2  638.47
#Mann= 3 , 1 , 0
  4529.2     .13       0  4997.3    .045       0  5002.7     .13       0
Bank Sta=4997.3,5002.7
XS Rating Curve= 0
Exp/Cntr=0.3,0.1

Type RM Length L Ch R = 1 ,50476.0 ,627,627,627
BEGIN DESCRIPTION:
Rock Creek 1 77.0
END DESCRIPTION:
XS GIS Cut Line= 3
      1860382.39       796249.63      1860450.94       795751.27
      1860427.21       795419.04
#Sta/Elev= 30
  4499.6  640.77  4609.6  636.47  4699.6  631.72  4709.6   630.4  4759.6   627.2
  4799.6  621.84  4819.6  618.46  4849.6  616.71  4879.6  616.81  4909.6     618
  4919.6  617.37  4949.6  617.09  4979.6  614.78  4989.6  614.89  4997.4   612.6
  4998.9   609.6  5001.2   609.6  5002.7   612.6  5012.6   616.9  5052.6  618.52
  5072.6   621.2  5102.6  623.49  5112.6  623.76  5172.6  629.07  5192.6  631.54
  5222.6  633.16  5252.6  635.75  5262.6  635.85  5302.6  638.37  5335.7  638.64
#Mann= 3 , 1 , 0
  4499.6     .13       0  4997.4    .045       0  5002.7     .13       0
Bank Sta=4997.4,5002.7
XS Rating Curve= 0
Exp/Cntr=0.3,0.1

Type RM Length L Ch R = 1 ,49849.0 ,471.4,471.4,471.4
BEGIN DESCRIPTION:
Rock Creek 1 76.0
END DESCRIPTION:
XS GIS Cut Line= 3
      1860838.55       796078.23      1860954.57       795775.01
      1861278.89       795513.96
#Sta/Elev= 30
  4671.4  637.28  4741.4  634.16  4801.4  629.09  4821.4  626.19  4841.4  622.62
  4851.4  621.65  4861.4  619.52  4871.4  619.67  4881.4  617.46  4891.4  616.22
  4921.4  614.81  4971.4  614.12  4981.4  613.43    4994   611.7  4995.5   608.7
  5004.5   608.7    5006   611.7  5006.1  612.83  5016.1  613.41  5026.1  612.91
  5066.1  613.05  5076.1  614.86  5106.1  617.92  5126.1  621.04  5146.1  620.78
  5176.1  621.83  5286.1  629.61  5306.1  630.46  5326.1  631.93  5412.4  636.96
#Mann= 3 , 1 , 0
  4671.4     .13       0    4994    .045       0    5006     .13       0
Bank Sta=4994,5006
XS Rating Curve= 0
Exp/Cntr=0.3,0.1

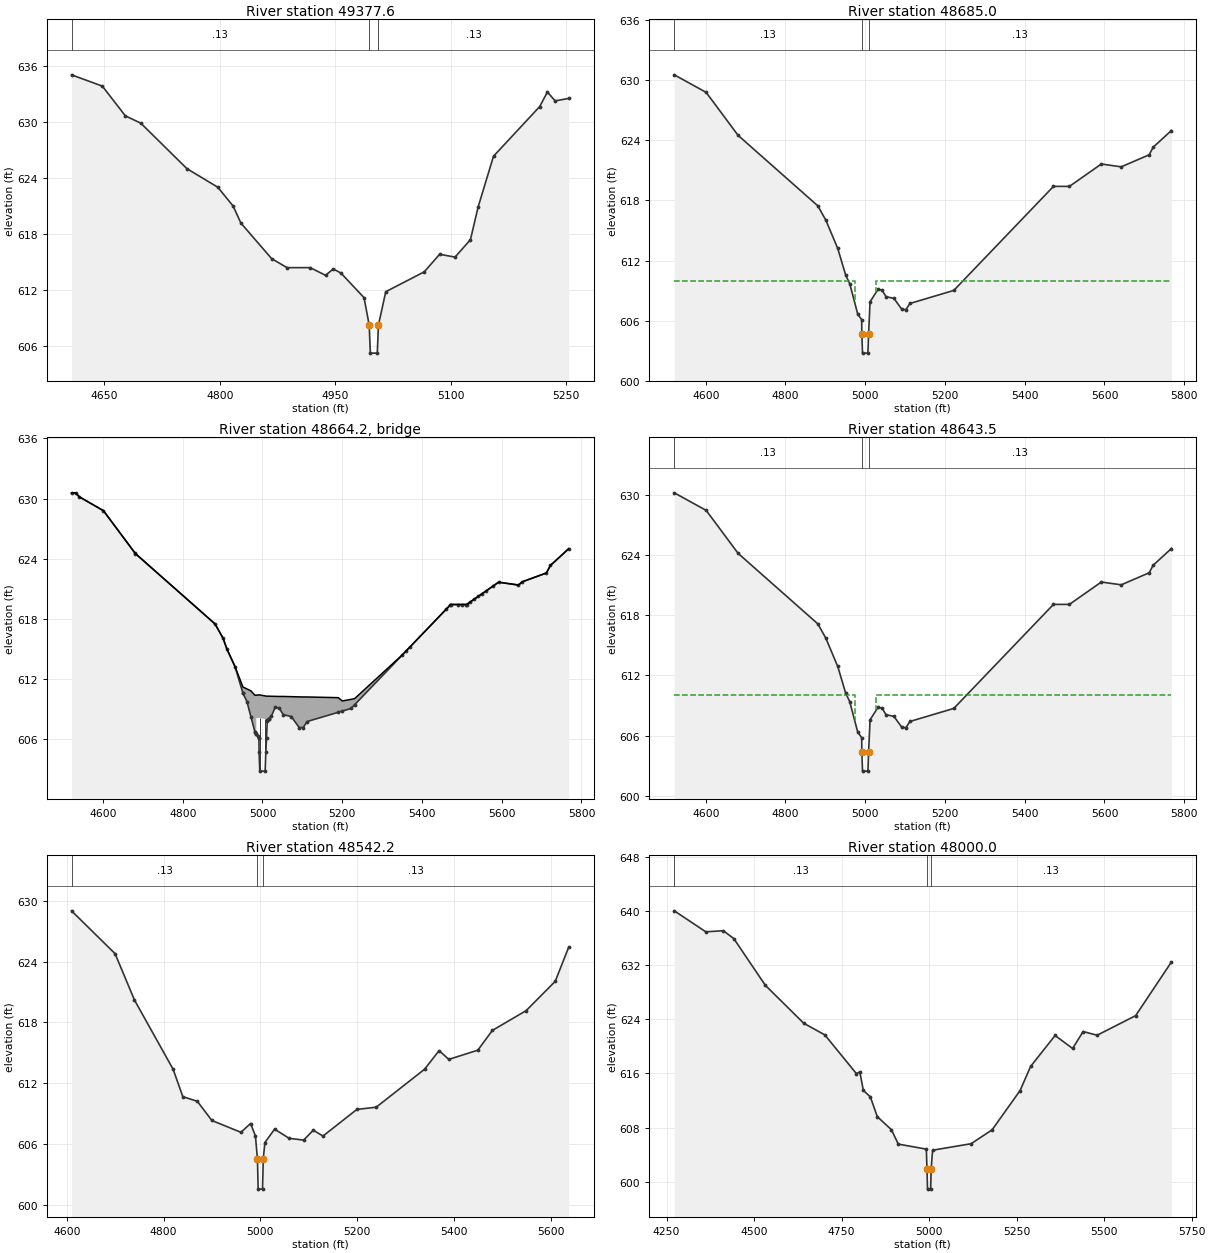
Type RM Length L Ch R = 1 ,49377.6 ,692.65,692.65,692.65
BEGIN DESCRIPTION:
Rock Creek 1 75.0
END DESCRIPTION:
XS GIS Cut Line= 3
      1860975.66       796278.63      1861297.35       796043.96
      1861331.63       795798.74
#Sta/Elev= 30
  4607.3  635.01  4647.3   633.8  4677.3  630.61  4697.3  629.83  4757.3  624.95
  4797.3  622.97  4817.3  620.94  4827.3  619.13  4867.3  615.31  4887.3  614.35
  4917.3  614.35  4937.3  613.53  4947.3  614.21  4957.3  613.77  4987.3  611.13
    4994  608.19  4995.5  605.19  5004.5  605.19    5006  608.19  5015.5  611.77
  5065.5   613.9  5085.5  615.78  5105.5  615.48  5125.5  617.34  5135.5  620.85
  5155.5  626.29  5215.5  631.61  5225.5  633.17  5235.5  632.22  5253.1  632.48
#Mann= 3 , 1 , 0
  4607.3     .13       0    4994    .045       0    5006     .13       0
Bank Sta=4994,5006
XS Rating Curve= 0
Exp/Cntr=0.5,0.3

Type RM Length L Ch R = 1 ,48685.0 ,41.5,41.5,41.5
BEGIN DESCRIPTION:
Upstream Section of Bridge/Culvert/Weir
END DESCRIPTION:
XS GIS Cut Line= 4
      1861078.23       796708.09      1861518.98       796520.64
       1861733.3       796434.57      1862202.63       796173.85
#Sta/Elev= 30
  4521.1  630.51  4601.1  628.76  4681.1  624.48  4881.1  617.45  4901.1  616.03
  4931.1   613.2    4951  610.54  4961.1   609.7  4981.1  606.67  4991.1   606.1
  4991.5  604.72  4993.2  602.77  5006.7  602.77  5008.5  604.72  5012.1  607.88
  5032.1  609.14  5042.1  609.05  5052.1   608.4  5072.1  608.22  5092.1  607.12
  5102.1  607.11  5112.1  607.72  5222.1  609.02  5472.1  619.39  5512.1  619.39
  5592.1  621.62  5642.1  621.34  5712.1  622.54  5722.1  623.29  5767.9  624.96
#Mann= 3 , 1 , 0
  4521.1     .13       0  4991.5    .045       0  5008.5     .13       0
#XS Ineff= 2 , 0
       0    4974     610    5026       0     610
Permanent Ineff=
       F       F
Bank Sta=4991.5,5008.5
XS Rating Curve= 0
Exp/Cntr=0.5,0.3

Type RM Length L Ch R = 3 ,48664.2 ,,,
BEGIN DESCRIPTION:
Beale Rd-TOR
Structure ID: NCF-0088
Approximate Survey Structure
END DESCRIPTION:
Bridge Culvert--1,0,-1,-1, 0
Deck Dist Width WeirC Skew NumUp NumDn MinLoCord MaxHiCord MaxSubmerge Is_Ogee
10,21.5,2.6,0, 39, 39, , , 0.95, 0, 1,1,,
  4521.1  4531.1  4541.1  4601.1  4681.1  4881.1  4901.1  4911.1  4931.1    4951
  4961.1    4971  4981.1 4984.41  4984.5  4991.5  5010.1  5015.5  5022.1  5032.1
  5042.1  5052.1  5072.1  5092.1  5102.1  5112.1  5190.1  5200.1  5222.1    5231
    5351  5472.1  5512.1  5592.1  5642.1  5652.1  5712.1  5722.1  5767.9
  630.54  630.57  630.16  628.79  624.52  617.49  616.07  614.96  613.24  611.19
     611  610.81  610.37  610.38  610.38  610.41  610.28  610.28  610.27  610.26
  610.25  610.25  610.23  610.21   610.2   610.2  610.13   609.8  609.96  610.03
  614.41  619.43  619.43  621.65  621.37   621.7  622.57  623.32  624.99
  630.54  630.57  630.16  628.79  624.51  617.48  616.06  614.95  613.23  610.57
  609.73  608.23   606.7  606.51  608.08  608.11  607.98  608.03  608.27  609.17
  609.08  608.43  608.25  607.15  607.14  607.75  608.67  608.79  609.05  609.42
   614.4  619.42  619.42  621.65  621.37   621.7  622.57  623.32  624.99
  4521.1  4531.1  4541.1  4601.1  4681.1  4881.1  4901.1  4911.1  4931.1    4951
  4961.1    4971  4981.1 4984.41  4984.5  4991.5  5010.1  5015.5  5022.1  5032.1
  5042.1  5052.1  5072.1  5092.1  5102.1  5112.1  5190.1  5200.1  5222.1    5231
    5351  5472.1  5512.1  5592.1  5642.1  5652.1  5712.1  5722.1  5767.9
  630.54  630.57  630.16  628.79  624.52  617.49  616.07  614.96  613.24  611.19
     611  610.81  610.37  610.38  610.38  610.41  610.28  610.28  610.27  610.26
  610.25  610.25  610.23  610.21   610.2   610.2  610.13   609.8  609.96  610.03
  614.41  619.43  619.43  621.65  621.37   621.7  622.57  623.32  624.99
  630.29  630.32  629.91  628.54  624.26  617.23  615.81   614.7  612.98  610.32
  609.48  607.98  606.45  606.26  607.83  607.86  607.73  607.78  608.02  608.92
  608.83  608.18     608   606.9  606.89   607.5  608.42  608.54   608.8  609.17
  614.15  619.17  619.17   621.4  621.12  621.45  622.32  623.07  624.74
Pier Skew, UpSta & Num, DnSta & Num=  ,4994, 2 ,4994, 2 , 0 , 0 , 0 ,,
       1       1
   601.8   609.1
       1       1
  601.55  608.85
Pier Skew, UpSta & Num, DnSta & Num=  ,5006, 2 ,5006, 2 , 0 , 0 , 0 ,,
       1       1
   601.8  609.01
       1       1
  601.55  608.76
Abutment Skew #Up #Dn= , 2 , 2
  4984.3    4988
  608.08  606.31
  4984.3    4988
  607.83  606.06
Abutment Skew #Up #Dn= , 2 , 2
    5012 5015.59
  607.82  608.03
    5012 5015.59
  607.57  607.78
BR Coef= 1 , 1 , 0 ,1.25, 0 ,,,0.8,0,2,0,
WSPro=,,,, 1 ,,,, 0 ,,,, 0 ,,,,-1 ,-1 ,-1 , 0 , 0 , 0 , 0 , 0
BR U #Sta/Elev= 64
  4521.1  630.54  4531.1  630.57  4541.1  630.16  4601.1  628.79    4681  624.52
  4681.1  624.51  4881.1  617.48  4901.1  616.06  4911.1  614.95  4931.1  613.23
    4951  610.57  4951.1  610.56  4961.1  609.73    4971  608.23    4981  606.72
  4981.1   606.7 4984.41  606.51  4984.5  606.51    4988  606.31    4991  606.14
  4991.1  606.13  4991.5  604.75  4993.2   602.8  5006.7   602.8  5008.5  604.75
  5010.1  606.15    5012  607.82  5012.1  607.91 5015.39  608.03  5015.5  608.03
  5022.1  608.27  5032.1  609.17  5042.1  609.08  5052.1  608.43  5072.1  608.25
  5092.1  607.15  5102.1  607.14  5112.1  607.75  5190.1  608.67  5200.1  608.79
  5222.1  609.05    5231  609.42    5351   614.4    5361  614.81    5371  615.23
    5461  618.96    5471  619.37  5472.1  619.42    5491  619.42    5501  619.42
    5511  619.42  5512.1  619.42    5521  619.67    5531  619.95    5541  620.23
    5551   620.5    5561  620.78  5578.5  621.27  5592.1  621.65  5642.1  621.37
  5652.1   621.7  5712.1  622.57  5722.1  623.32  5767.9  624.99
BR U #Mann= 3
  4521.1     .13  4991.5    .045  5008.5     .13
BR U Banks=4991.5,5008.5
BR D #Sta/Elev= 64
  4521.1  630.29  4531.1  630.32  4541.1  629.91  4601.1  628.54    4681  624.27
  4681.1  624.26  4881.1  617.23  4901.1  615.81  4911.1   614.7  4931.1  612.98
    4951  610.32  4951.1  610.31  4961.1  609.48    4971  607.98    4981  606.47
  4981.1  606.45 4984.41  606.26  4984.5  606.26    4988  606.06    4991  605.89
  4991.1  605.88  4991.5   604.5  4993.2  602.55  5006.7  602.55  5008.5   604.5
  5010.1   605.9    5012  607.57  5012.1  607.66 5015.39  607.78  5015.5  607.78
  5022.1  608.02  5032.1  608.92  5042.1  608.83  5052.1  608.18  5072.1     608
  5092.1   606.9  5102.1  606.89  5112.1   607.5  5190.1  608.42  5200.1  608.54
  5222.1   608.8    5231  609.17    5351  614.15    5361  614.56    5371  614.98
    5461  618.71    5471  619.12  5472.1  619.17    5491  619.17    5501  619.17
    5511  619.17  5512.1  619.17    5521  619.42    5531   619.7    5541  619.98
    5551  620.25    5561  620.53  5578.5  621.02  5592.1   621.4  5642.1  621.12
  5652.1  621.45  5712.1  622.32  5722.1  623.07  5767.9  624.74
BR D #Mann= 3
  4521.1     .13  4991.5    .045  5008.5     .13
BR D Banks=4991.5,5008.5
BC Design=,, 0 ,, 0 ,,,,,,
BC HTab HWMax=630.54

Type RM Length L Ch R = 1 ,48643.5 ,101.25,101.25,101.25
BEGIN DESCRIPTION:
Downstream Section of Bridge/Culvert/Weir
END DESCRIPTION:
XS GIS Cut Line= 4
      1861100.18       796743.31      1861540.94       796555.86
      1861755.26       796469.79      1862224.58       796209.06
#Sta/Elev= 30
  4521.1   630.2  4601.1  628.45  4681.1  624.17  4881.1  617.14  4901.1  615.72
  4931.1  612.89    4951  610.23  4961.1  609.39  4981.1  606.36  4991.1  605.79
  4991.5  604.41  4993.2  602.46  5006.7  602.46  5008.5  604.41  5012.1  607.57
  5032.1  608.83  5042.1  608.74  5052.1  608.09  5072.1  607.91  5092.1  606.81
  5102.1   606.8  5112.1  607.41  5222.1  608.71  5472.1  619.08  5512.1  619.08
  5592.1  621.31  5642.1  621.03  5712.1  622.23  5722.1  622.98  5767.9  624.65
#Mann= 3 , 1 , 0
  4521.1     .13       0  4991.5    .045       0  5008.5     .13       0
#XS Ineff= 2 , 0
       0    4974     610    5026       0     610
Permanent Ineff=
       F       F
Bank Sta=4991.5,5008.5
XS Rating Curve= 0
Exp/Cntr=0.5,0.3

Type RM Length L Ch R = 1 ,48542.2 ,542.2,542.2,542.2
BEGIN DESCRIPTION:
Rock Creek 1 70.0
END DESCRIPTION:
XS GIS Cut Line= 3
       1861278.2       796788.48      1861622.59        796606.3
      1862211.54       796361.73
#Sta/Elev= 30
  4609.8  629.02  4699.8  624.79  4739.8  620.22  4819.8  613.37  4839.8  610.67
  4869.8  610.21  4899.8  608.32  4959.8  607.15  4979.8  608.02  4989.8   606.8
    4994  604.54  4995.5  601.54  5004.5  601.54    5006  604.54  5009.4  606.14
  5029.4  607.46  5059.4  606.56  5089.4  606.38  5109.4  607.36  5129.4  606.78
  5199.4  609.41  5239.4  609.63  5339.4  613.38  5369.4  615.22  5389.4  614.35
  5449.4  615.26  5479.4  617.21  5549.4  619.17  5609.4  622.06  5637.1  625.42
#Mann= 3 , 1 , 0
  4609.8     .13       0    4994    .045       0    5006     .13       0
Bank Sta=4994,5006
XS Rating Curve= 0
Exp/Cntr=0.3,0.1

Type RM Length L Ch R = 1 ,48000.0 ,198.8,198.8,198.8
BEGIN DESCRIPTION:
Rock Creek 1 68.0
END DESCRIPTION:
XS GIS Cut Line= 3
        1861525.         797525.      1861992.34       796967.06
        1862525.         796525.
#Sta/Elev= 30
  4272.2  640.02  4362.2  636.92  4412.2  637.08  4442.2  635.92  4532.2  629.02
  4642.2   623.4  4702.2  621.69  4792.2  615.98  4802.2  616.21  4812.2  613.49
  4832.2  612.53  4852.2   609.6  4892.2  607.69  4912.2  605.55  4992.2  604.81
    4994   601.9  4995.5   598.9  5004.5   598.9    5006   601.9    5010  604.65
    5120  605.61    5180  607.66    5260  613.47    5290  617.03    5360   621.6
    5410  619.68    5440  622.18    5480  621.64    5590  624.53  5692.2  632.46
#Mann= 3 , 1 , 0
  4272.2     .13       0    4994    .045       0    5006     .13       0
Bank Sta=4994,5006
XS Rating Curve= 0
Exp/Cntr=0.3,0.1