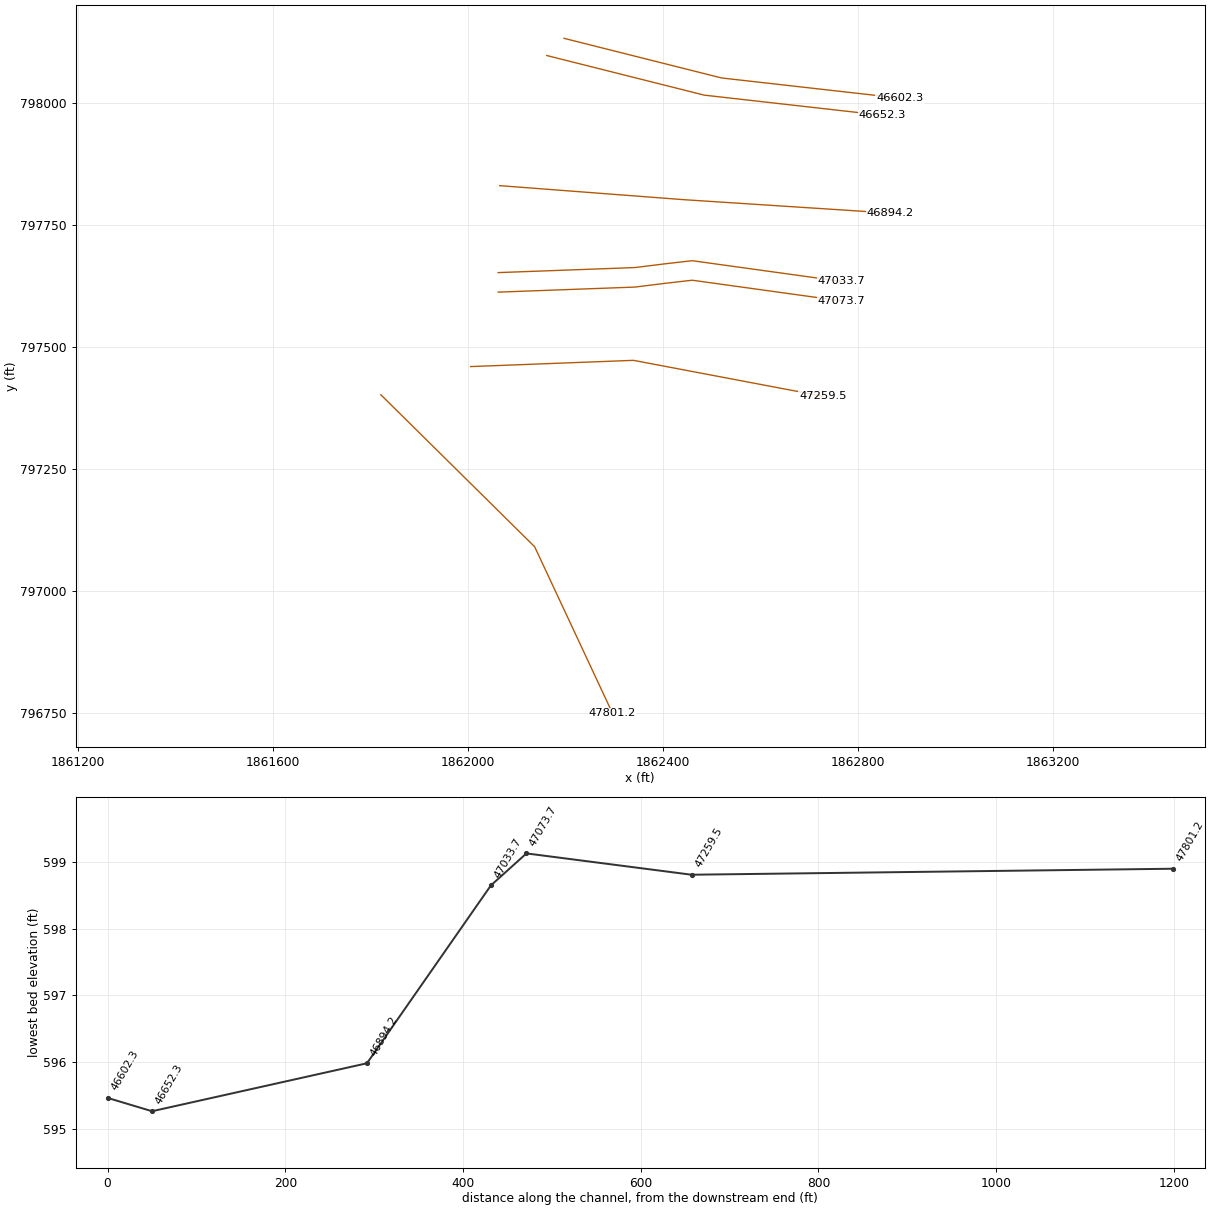
HEC-RAS study ROCK CREEK 1.PRJ: Rock Creek 1

--- ROCK CREEK 1.g01 (geometry) --- (continued)

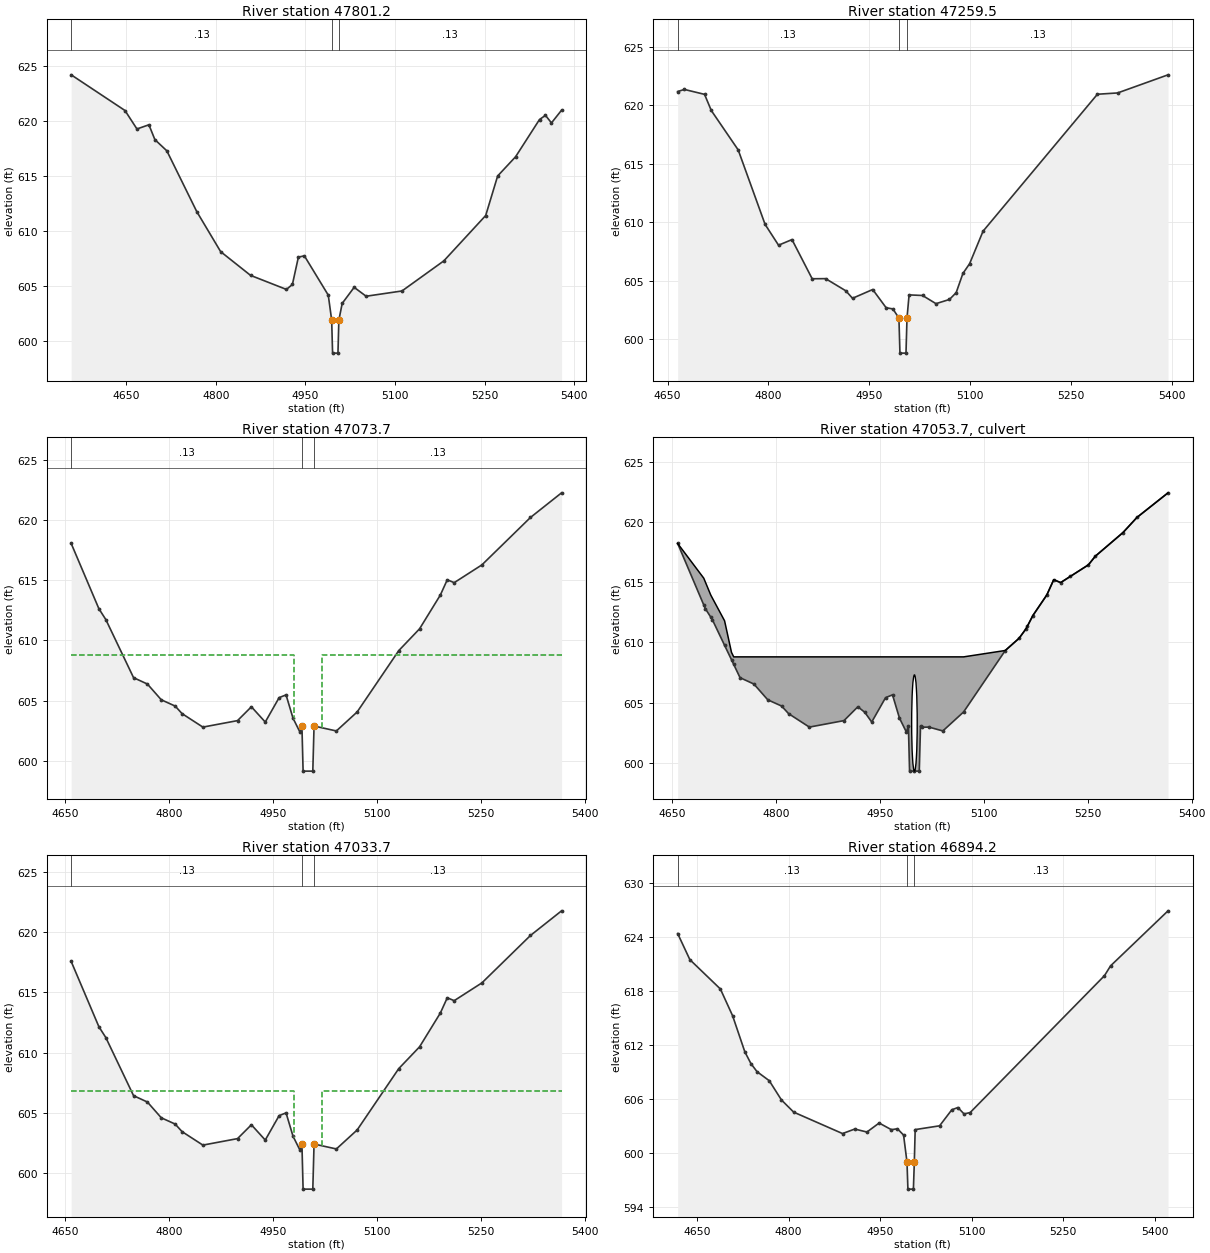
Type RM Length L Ch R = 1 ,47801.2 ,541.7,541.7,541.7
BEGIN DESCRIPTION:
Rock Creek 1 67.0
END DESCRIPTION:
XS GIS Cut Line= 3
      1861820.99       797402.64      1862136.43       797091.19
      1862296.14        796749.8
#Sta/Elev= 30
  4558.3  624.24  4648.3  620.99  4668.3  619.31  4688.3  619.69  4698.3  618.34
  4718.3  617.32  4768.3  611.79  4808.3  608.14  4858.3  605.98  4918.3   604.7
  4928.3  605.15  4938.3  607.64  4948.3  607.76  4988.3  604.18    4994   601.9
  4995.5   598.9  5004.5   598.9    5006   601.9  5011.6  603.43  5031.6  604.89
  5051.6  604.08  5111.6  604.56  5181.6   607.3  5251.6  611.43  5271.6  615.03
  5301.6  616.78  5341.6  620.17  5351.6  620.55  5361.6  619.86  5378.5  621.02
#Mann= 3 , 1 , 0
  4558.3     .13       0    4994    .045       0    5006     .13       0
Bank Sta=4994,5006
XS Rating Curve= 0
Exp/Cntr=0.3,0.1

Type RM Length L Ch R = 1 ,47259.5 ,185.8,185.8,185.8
BEGIN DESCRIPTION:
Rock Creek 1 66.0
END DESCRIPTION:
XS GIS Cut Line= 3
      1862005.26       797460.33      1862339.07       797473.11
      1862727.18       797399.64
#Sta/Elev= 30
    4665  621.18    4675  621.36    4705  620.94    4715  619.56    4755  616.19
    4795  609.82    4815  608.04    4835  608.52    4865  605.17    4885  605.18
    4915  604.14    4925   603.5    4955  604.25    4975  602.69    4985  602.59
    4994  601.81  4995.5  598.81  5004.5  598.81    5006  601.81  5009.1  603.79
  5029.1  603.74  5049.1  603.04  5069.1   603.4  5079.1  603.98  5089.1  605.62
  5099.1  606.46  5119.1  609.24  5289.1  620.95  5319.1  621.06  5394.1  622.61
#Mann= 3 , 1 , 0
    4665     .13       0    4994    .045       0    5006     .13       0
Bank Sta=4994,5006
XS Rating Curve= 0
Exp/Cntr=0.5,0.3

Type RM Length L Ch R = 1 ,47073.7 ,40,40,40
BEGIN DESCRIPTION:
Upstream Section of Bridge/Culvert/Weir
END DESCRIPTION:
XS GIS Cut Line= 5
      1862061.69       797612.87       1862342.1       797623.21
      1862403.23       797630.81      1862459.65       797637.26
      1862765.24       797594.95
#Sta/Elev= 30
  4658.4  618.06  4698.4  612.63  4708.4  611.73  4748.4   606.9  4768.4  606.37
  4788.4  605.06  4808.4  604.54  4818.4  603.91  4848.4  602.79  4898.4  603.33
  4918.4  604.48  4938.4  603.21  4958.4  605.24  4968.4  605.47  4978.4  603.54
  4988.4  602.38  4991.3  602.88    4993  599.13    5007  599.13  5008.8  602.88
    5041  602.47    5071  604.05    5131  609.15    5161  610.96    5191  613.77
    5201  615.04    5211   614.8    5251  616.28    5321  620.22  5365.9  622.27
#Mann= 3 , 1 , 0
  4658.4     .13       0  4991.3    .045       0  5008.8     .13       0
#XS Ineff= 2 , 0
       0    4980   608.8    5020       0   608.8
Permanent Ineff=
       F       F
Bank Sta=4991.3,5008.8
XS Rating Curve= 0
Exp/Cntr=0.5,0.3

Type RM Length L Ch R = 2 ,47053.7 ,,,
BEGIN DESCRIPTION:
Private Rd3-TOR
Structure ID: NCF-0089
Approximate Survey Structure
END DESCRIPTION:
Bridge Culvert--1,0,-1,-1, 0
Deck Dist Width WeirC Skew NumUp NumDn MinLoCord MaxHiCord MaxSubmerge Is_Ogee
10,20,3,0, 45, 45, , , 0.95, 0, 1,1,,
  4658.4  4696.1  4698.4  4706.1  4708.4  4726.1  4736.1  4739.3  4748.4  4768.4
  4788.4  4808.4  4818.4  4848.4  4898.4  4918.4  4928.4  4938.4  4958.4  4968.4
  4978.4  4988.4  4991.3    4993    5000    5007  5008.8    5011    5021    5041
    5071    5131    5151    5161  5163.1    5171    5191    5201    5211  5225.1
    5251    5261    5301    5321  5365.9
  618.23  615.34  615.02  613.95   613.7   611.8  609.17   608.8   608.8   608.8
   608.8   608.8   608.8   608.8   608.8   608.8   608.8   608.8   608.8   608.8
   608.8   608.8   608.8   608.8   608.8   608.8   608.8   608.8   608.8   608.8
   608.8  609.33  610.35  611.14  611.37  612.25  613.95  615.22  614.98   615.5
  616.45  617.17  619.14  620.39  622.44
  618.23  613.11   612.8  612.11   611.9  609.76  608.56  608.17  607.07  606.54
  605.23  604.71  604.08  602.96   603.5  604.65  604.19  603.38  605.41  605.64
  603.71  602.55  603.05   599.3   599.3   599.3  603.05  602.95  602.96  602.64
  604.22  609.32  610.34  611.13  611.36  612.24  613.94  615.21  614.97  615.49
  616.45  617.17  619.14  620.39  622.44
  4658.4  4696.1  4698.4  4706.1  4708.4  4726.1  4736.1  4739.3  4748.4  4768.4
  4788.4  4808.4  4818.4  4848.4  4898.4  4918.4  4928.4  4938.4  4958.4  4968.4
  4978.4  4988.4  4991.3    4993    5000    5007  5008.8    5011    5021    5041
    5071    5131    5151    5161  5163.1    5171    5191    5201    5211  5225.1
    5251    5261    5301    5321  5365.9
  618.23  615.34  615.02  613.95   613.7   611.8  609.17   608.8   608.8   608.8
   608.8   608.8   608.8   608.8   608.8   608.8   608.8   608.8   608.8   608.8
   608.8   608.8   608.8   608.8   608.8   608.8   608.8   608.8   608.8   608.8
   608.8  609.33  610.35  611.14  611.37  612.25  613.95  615.22  614.98   615.5
  616.45  617.17  619.14  620.39  622.44
  618.13  613.01   612.7  612.01   611.8  609.66  608.46  608.07  606.97  606.44
  605.13  604.61  603.98  602.86   603.4  604.55  604.09  603.28  605.31  605.54
  603.61  602.45  602.95   599.2   599.2   599.2  602.95  602.85  602.86  602.54
  604.12  609.22  610.24  611.03  611.26  612.14  613.84  615.11  614.87  615.39
  616.35  617.07  619.04  620.29  622.34
BR Coef= 1 , 0 , 0 ,1.25, 0 ,,,0.8,-1,2,0,
WSPro=,,,, 1 ,,,, 0 ,,,, 0 ,,,,-1 ,-1 ,-1 , 0 , 0 , 0 , 0 , 0
Culvert=1,8,,20,0.024,0.9,1,2,3,599.3,5000.02,599.2,5000.02,Culvert #1  , 0 ,10
Culvert Bottom n=0.024
BR U #Sta/Elev= 45
  4658.4  618.23  4696.1  613.11  4698.4   612.8  4706.1  612.11  4708.4   611.9
  4726.1  609.76  4736.1  608.56  4739.3  608.17  4748.4  607.07  4768.4  606.54
  4788.4  605.23  4808.4  604.71  4818.4  604.08  4848.4  602.96  4898.4   603.5
  4918.4  604.65  4928.4  604.19  4938.4  603.38  4958.4  605.41  4968.4  605.64
  4978.4  603.71  4988.4  602.55  4991.3  603.05    4993   599.3    5000   599.3
    5007   599.3  5008.8  603.05    5011  602.95    5021  602.96    5041  602.64
    5071  604.22    5131  609.32    5151  610.34    5161  611.13  5163.1  611.36
    5171  612.24    5191  613.94    5201  615.21    5211  614.97  5225.1  615.49
    5251  616.45    5261  617.17    5301  619.14    5321  620.39  5365.9  622.44
BR U #Mann= 3
  4658.4     .13  4991.3    .045  5008.8     .13
BR U Banks=4991.3,5008.8
BR D #Sta/Elev= 45
  4658.4  618.13  4696.1  613.01  4698.4   612.7  4706.1  612.01  4708.4   611.8
  4726.1  609.66  4736.1  608.46  4739.3  608.07  4748.4  606.97  4768.4  606.44
  4788.4  605.13  4808.4  604.61  4818.4  603.98  4848.4  602.86  4898.4   603.4
  4918.4  604.55  4928.4  604.09  4938.4  603.28  4958.4  605.31  4968.4  605.54
  4978.4  603.61  4988.4  602.45  4991.3  602.95    4993   599.2    5000   599.2
    5007   599.2  5008.8  602.95    5011  602.85    5021  602.86    5041  602.54
    5071  604.12    5131  609.22    5151  610.24    5161  611.03  5163.1  611.26
    5171  612.14    5191  613.84    5201  615.11    5211  614.87  5225.1  615.39
    5251  616.35    5261  617.07    5301  619.04    5321  620.29  5365.9  622.34
BR D #Mann= 3
  4658.4     .13  4991.3    .045  5008.8     .13
BR D Banks=4991.3,5008.8
BC Design=,, 0 ,, 0 ,,,,,,
BC HTab HWMax=622.27

Type RM Length L Ch R = 1 ,47033.7 ,139.5,139.5,139.5
BEGIN DESCRIPTION:
Downstream Section of Bridge/Culvert/Weir
END DESCRIPTION:
XS GIS Cut Line= 5
      1862061.69       797652.87       1862342.1       797663.21
      1862403.23       797670.81      1862459.65       797677.26
      1862765.24       797634.95
#Sta/Elev= 30
  4658.4  617.58  4698.4  612.15  4708.4  611.25  4748.4  606.42  4768.4  605.89
  4788.4  604.58  4808.4  604.06  4818.4  603.43  4848.4  602.31  4898.4  602.85
  4918.4     604  4938.4  602.73  4958.4  604.76  4968.4  604.99  4978.4  603.06
  4988.4   601.9  4991.3   602.4    4993  598.65    5007  598.65  5008.8   602.4
    5041  601.99    5071  603.57    5131  608.67    5161  610.48    5191  613.29
    5201  614.56    5211  614.32    5251   615.8    5321  619.74  5365.9  621.79
#Mann= 3 ,-1 , 0
  4658.4     .13       0  4991.3    .045       0  5008.8     .13       0
#XS Ineff= 2 , 0
       0    4980   606.8    5020       0   606.8
Permanent Ineff=
       F       F
Bank Sta=4991.3,5008.8
XS Rating Curve= 0
Exp/Cntr=0.5,0.3

Type RM Length L Ch R = 1 ,46894.2 ,241.9,241.9,241.9
BEGIN DESCRIPTION:
Rock Creek 1 63.0
END DESCRIPTION:
XS GIS Cut Line= 3
      1862064.83       797831.04      1862442.74       797802.26
      1862865.97       797774.81
#Sta/Elev= 30
  4618.4  624.36  4638.4  621.46  4688.4   618.2  4708.4  615.23  4728.4  611.23
  4738.4  609.92  4748.4  609.02  4768.4  608.02  4788.4  605.88  4808.4  604.53
  4888.4  602.15  4908.4  602.65  4928.4  602.32  4948.4  603.32  4968.4  602.58
  4978.4  602.68  4988.4  601.98    4994  598.98  4995.5  595.98  5004.5  595.98
    5006  598.98  5007.4  602.59  5047.4  603.01  5067.4  604.79  5077.4  605.04
  5087.4  604.33  5097.4  604.48  5317.4  619.68  5327.4  620.77  5421.5  626.88
#Mann= 3 , 1 , 0
  4618.4     .13       0    4994    .045       0    5006     .13       0
Bank Sta=4994,5006
XS Rating Curve= 0
Exp/Cntr=0.5,0.3

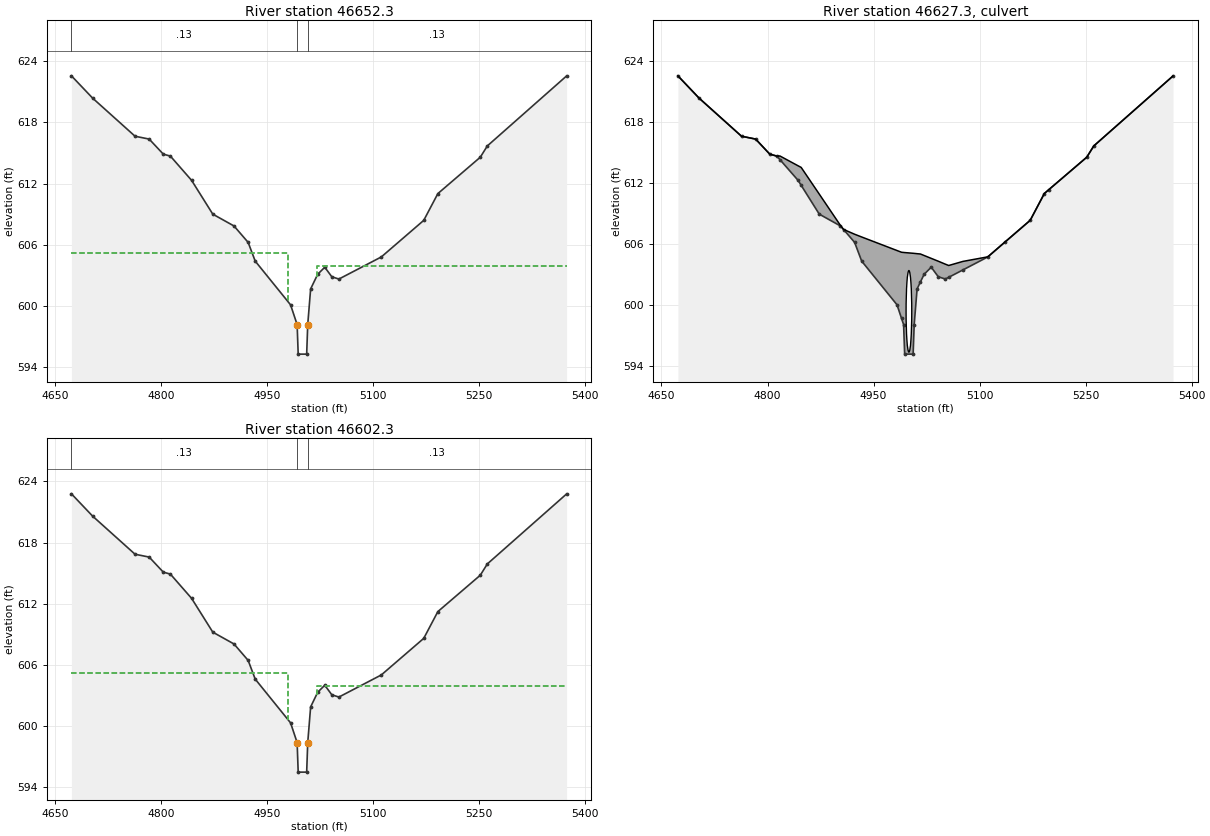
Type RM Length L Ch R = 1 ,46652.3 ,50,50,50
BEGIN DESCRIPTION:
Upstream Section of Bridge/Culvert/Weir
END DESCRIPTION:
XS GIS Cut Line= 3
       1862161.2       798097.65       1862484.2       798016.47
      1862849.34       797975.23
#Sta/Elev= 27
  4673.2  622.58  4703.2  620.39  4763.2  616.65  4783.2  616.37  4803.2  614.89
  4813.2   614.7  4843.2  612.32  4873.2     609  4903.2  607.84  4923.2  606.23
  4933.2  604.39  4983.2   600.1  4992.5  598.16    4994  595.26    5006  595.26
  5007.5  598.16  5011.6  601.66  5021.6   603.1  5031.6  603.79  5041.6  602.85
  5051.6  602.63  5111.6   604.8  5171.6  608.39  5191.6  611.02  5251.6  614.59
  5261.6   615.7  5373.7  622.57
#Mann= 3 , 1 , 0
  4673.2     .13       0  4992.5    .045       0  5007.5     .13       0
#XS Ineff= 2 , 0
       0    4980  605.18    5020       0   603.9
Permanent Ineff=
       F       F
Bank Sta=4992.5,5007.5
XS Rating Curve= 0
Exp/Cntr=0.5,0.3

Type RM Length L Ch R = 2 ,46627.3 ,,,
BEGIN DESCRIPTION:
Private Rd2-TOR
Structure ID: NCF-1559
Approximate Survey Structure
END DESCRIPTION:
Bridge Culvert--1,0,-1,-1, 0
Deck Dist Width WeirC Skew NumUp NumDn MinLoCord MaxHiCord MaxSubmerge Is_Ogee
10,30,3,0, 36, 36, , , 0.95, 0, 1,1,,
  4673.2  4703.2  4763.2  4783.2  4803.2  4813.2  4817.6  4843.2  4847.6  4873.2
  4903.2  4907.6  4923.2  4933.2  4983.2  4989.6  4992.5    4994    5006  5007.5
  5011.6  5016.3  5021.6  5031.6  5041.6  5051.6  5056.3  5076.3  5111.6  5136.3
  5171.6  5191.6  5197.6  5251.6  5261.6  5373.7
  622.52  620.33  616.59  616.31  614.83  614.64  614.65  613.69  613.53  610.91
  607.83  607.44  606.97   606.7  605.37   605.2  605.18  605.17   605.1  605.09
  605.06  605.03  604.88   604.6  604.32  604.03   603.9   604.3  604.75  606.23
  608.34  610.97  611.33  614.53  615.64  622.51
  622.52  620.33  616.59  616.31  614.83  614.64  614.29  612.26  611.77  608.94
  607.78  607.43  606.17  604.33  600.04   598.7   598.1   595.2   595.2   598.1
   601.6  602.28  603.04  603.73  602.79  602.57  602.74  603.46  604.74  606.22
  608.33  610.96  611.32  614.53  615.64  622.51
  4673.2  4703.2  4763.2  4783.2  4803.2  4813.2  4817.6  4843.2  4847.6  4873.2
  4903.2  4907.6  4923.2  4933.2  4983.2  4989.6  4992.5    4994    5006  5007.5
  5011.6  5016.3  5021.6  5031.6  5041.6  5051.6  5056.3  5076.3  5111.6  5136.3
  5171.6  5191.6  5197.6  5251.6  5261.6  5373.7
  622.52  620.33  616.59  616.31  614.83  614.64  614.65  613.69  613.53  610.91
  607.83  607.44  606.97   606.7  605.37   605.2  605.18  605.17   605.1  605.09
  605.06  605.03  604.88   604.6  604.32  604.03   603.9   604.3  604.75  606.23
  608.34  610.97  611.33  614.53  615.64  622.51
  622.37  620.18  616.44  616.16  614.68  614.49  614.14  612.11  611.62  608.79
  607.63  607.28  606.02  604.18  599.89  598.55  597.95  595.05  595.05  597.95
  601.45  602.13  602.89  603.58  602.64  602.42  602.59  603.31  604.59  606.07
  608.18  610.81  611.17  614.38  615.49  622.36
BR Coef= 1 , 0 , 0 ,1.25, 0 ,,,0.8,-1,2,0,
WSPro=,,,, 1 ,,,, 0 ,,,, 0 ,,,,-1 ,-1 ,-1 , 0 , 0 , 0 , 0 , 0
Culvert=1,8,,30,0.024,0.9,1,2,3,595.4,5000.02,595.25,5000.02,Culvert #1  , 0 ,10
Culvert Bottom n=0.024
BR U #Sta/Elev= 36
  4673.2  622.52  4703.2  620.33  4763.2  616.59  4783.2  616.31  4803.2  614.83
  4813.2  614.64  4817.6  614.29  4843.2  612.26  4847.6  611.77  4873.2  608.94
  4903.2  607.78  4907.6  607.43  4923.2  606.17  4933.2  604.33  4983.2  600.04
  4989.6   598.7  4992.5   598.1    4994   595.2    5006   595.2  5007.5   598.1
  5011.6   601.6  5016.3  602.28  5021.6  603.04  5031.6  603.73  5041.6  602.79
  5051.6  602.57  5056.3  602.74  5076.3  603.46  5111.6  604.74  5136.3  606.22
  5171.6  608.33  5191.6  610.96  5197.6  611.32  5251.6  614.53  5261.6  615.64
  5373.7  622.51
BR U #Mann= 3
  4673.2     .13  4992.5    .045  5007.5     .13
BR U Banks=4992.5,5007.5
BR D #Sta/Elev= 36
  4673.2  622.37  4703.2  620.18  4763.2  616.44  4783.2  616.16  4803.2  614.68
  4813.2  614.49  4817.6  614.14  4843.2  612.11  4847.6  611.62  4873.2  608.79
  4903.2  607.63  4907.6  607.28  4923.2  606.02  4933.2  604.18  4983.2  599.89
  4989.6  598.55  4992.5  597.95    4994  595.05    5006  595.05  5007.5  597.95
  5011.6  601.45  5016.3  602.13  5021.6  602.89  5031.6  603.58  5041.6  602.64
  5051.6  602.42  5056.3  602.59  5076.3  603.31  5111.6  604.59  5136.3  606.07
  5171.6  608.18  5191.6  610.81  5197.6  611.17  5251.6  614.38  5261.6  615.49
  5373.7  622.36
BR D #Mann= 3
  4673.2     .13  4992.5    .045  5007.5     .13
BR D Banks=4992.5,5007.5
BC Design=,, 0 ,, 0 ,,,,,,
BC HTab HWMax=622.58

Type RM Length L Ch R = 1 ,46602.3 ,71.9,71.9,71.9
BEGIN DESCRIPTION:
Downstream Section of Bridge/Culvert/Weir
END DESCRIPTION:
XS GIS Cut Line= 3
       1862196.7       798132.86       1862519.7       798051.67
      1862884.84       798010.44
#Sta/Elev= 27
  4673.2  622.78  4703.2  620.59  4763.2  616.85  4783.2  616.57  4803.2  615.09
  4813.2   614.9  4843.2  612.52  4873.2   609.2  4903.2  608.04  4923.2  606.43
  4933.2  604.59  4983.2   600.3  4992.5  598.36    4994  595.46    5006  595.46
  5007.5  598.36  5011.6  601.86  5021.6   603.3  5031.6  603.99  5041.6  603.05
  5051.6  602.83  5111.6     605  5171.6  608.59  5191.6  611.22  5251.6  614.79
  5261.6   615.9  5373.7  622.77
#Mann= 3 , 1 , 0
  4673.2     .13       0  4992.5    .045       0  5007.5     .13       0
#XS Ineff= 2 , 0
       0    4980  605.18    5020       0   603.9
Permanent Ineff=
       F       F
Bank Sta=4992.5,5007.5
XS Rating Curve= 0
Exp/Cntr=0.5,0.3