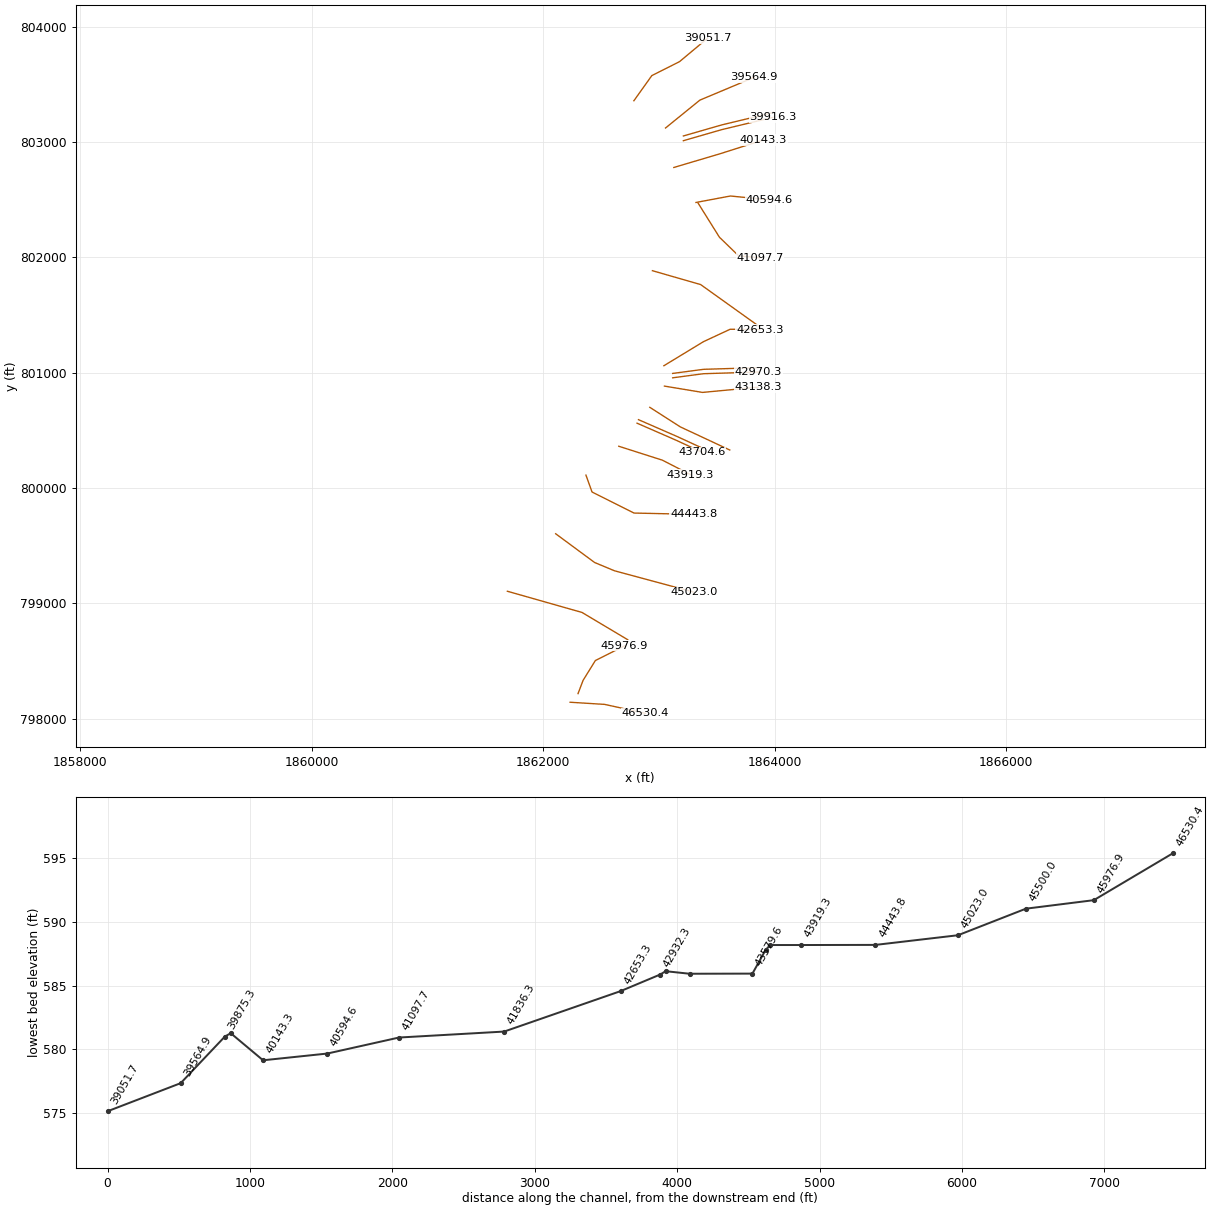
HEC-RAS study ROCK CREEK 1.PRJ: Rock Creek 1

--- ROCK CREEK 1.g01 (geometry) --- (continued)

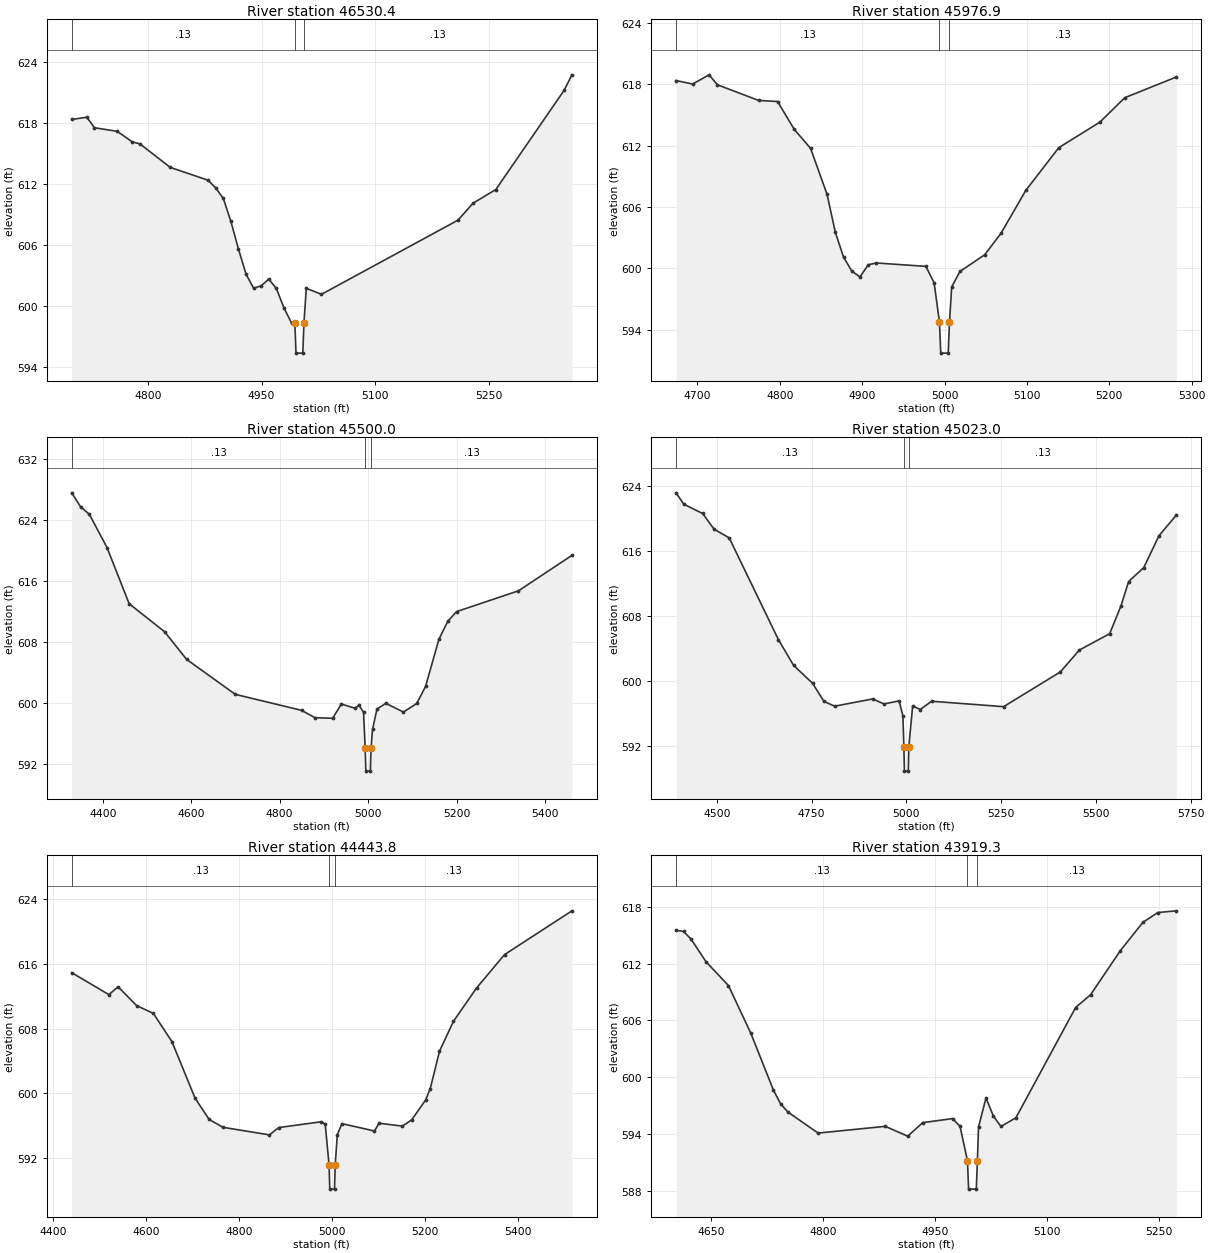
Type RM Length L Ch R = 1 ,46530.4 ,553.5,553.5,553.5
BEGIN DESCRIPTION:
Rock Creek 1 60.0
END DESCRIPTION:
XS GIS Cut Line= 3
      1862233.86       798142.03      1862532.81       798123.34
       1862884.7       798045.49
#Sta/Elev= 30
  4699.6  618.32  4719.6  618.54  4729.6  617.51  4759.6  617.16  4779.6  616.12
  4789.6  615.93  4829.6  613.62  4879.6  612.36  4889.6   611.6  4899.6  610.58
  4909.6  608.32  4919.6  605.61  4929.6  603.15  4939.6  601.76  4949.6  602.01
  4959.6  602.66  4969.6  601.74  4979.6  599.84  4989.6  598.36    4994   598.4
  4995.5   595.4  5004.5   595.4    5006   598.4  5009.1  601.76  5029.1  601.17
  5209.1  608.44  5229.1  610.11  5259.1  611.45  5349.1  621.17  5359.5   622.7
#Mann= 3 , 1 , 0
  4699.6     .13       0    4994    .045       0    5006     .13       0
Bank Sta=4994,5006
XS Rating Curve= 0
Exp/Cntr=0.3,0.1

Type RM Length L Ch R = 1 ,45976.9 ,476.9,476.9,476.9
BEGIN DESCRIPTION:
Rock Creek 1 59.0
END DESCRIPTION:
XS GIS Cut Line= 4
      1862302.37       798216.77      1862345.97       798331.99
      1862451.84       798503.26      1862704.08       798630.94
#Sta/Elev= 30
  4674.2  618.36  4694.2  618.02  4714.2  618.92  4724.2  617.95  4774.2  616.42
  4797.4  616.31  4817.4  613.61  4837.4  611.73  4857.4  607.24  4867.4  603.54
  4877.4  601.11  4887.4  599.74  4897.4  599.17  4907.4  600.36  4917.4  600.53
  4977.4   600.2  4987.4  598.58  4993.9  594.72  4995.4  591.72  5004.5  591.72
    5006  594.72  5008.7  598.19  5018.7   599.7  5048.7  601.33  5068.7  603.45
  5098.7  607.63  5138.7   611.8  5188.7   614.3  5218.7  616.68  5281.5  618.71
#Mann= 3 , 1 , 0
  4674.2     .13       0  4993.9    .045       0    5006     .13       0
Bank Sta=4993.9,5006
XS Rating Curve= 0
Exp/Cntr=0.3,0.1

Type RM Length L Ch R = 1 ,45500.0 ,477,477,477
BEGIN DESCRIPTION:
Rock Creek 1 58.0
END DESCRIPTION:
XS GIS Cut Line= 3
      1861692.01       799104.27      1862336.61       798920.49
      1862732.11       798683.87
#Sta/Elev= 30
  4329.7  627.55  4349.7  625.73  4369.7  624.73  4409.7  620.36  4459.7     613
  4539.7  609.34  4589.7   605.7  4699.7  601.12  4849.7  599.02  4879.7  598.06
  4919.7  597.98  4939.7  599.85  4969.7  599.31  4979.7  599.66  4989.7  598.76
  4993.4  594.05  4994.9  591.05  5005.1  591.05  5006.6  594.05    5010  596.53
    5020  599.18    5040  599.94    5080   598.8    5110  599.92    5130  602.17
    5160  608.33    5180  610.69    5200  611.97    5340   614.7  5460.9  619.35
#Mann= 3 , 1 , 0
  4329.7     .13       0  4993.4    .045       0  5006.6     .13       0
Bank Sta=4993.4,5006.6
XS Rating Curve= 0
Exp/Cntr=0.3,0.1

Type RM Length L Ch R = 1 ,45023.0 ,579.2,579.2,579.2
BEGIN DESCRIPTION:
Rock Creek 1 57.0
END DESCRIPTION:
XS GIS Cut Line= 4
       1862109.3       799602.52      1862445.62        799353.4
      1862616.89       799281.77      1863308.21       799094.93
#Sta/Elev= 30
  4392.4   623.2  4412.4   621.8  4462.4  620.66  4492.4  618.73  4532.4  617.66
  4662.4  605.13  4702.4  601.97  4752.4  599.77  4782.4  597.54  4810.9  596.95
  4910.9  597.84  4940.9  597.23  4980.9   597.6  4990.9  595.75  4993.4  591.96
  4994.9  588.96  5005.1  588.96  5006.5  591.96  5016.6  596.99  5036.6  596.54
  5066.6  597.56  5256.6  596.89  5406.6  601.17  5456.6  603.86  5536.6  605.87
  5566.6  609.31  5586.6  612.29  5626.6     614  5666.6  617.92  5712.7  620.47
#Mann= 3 , 1 , 0
  4392.4     .13       0  4993.4    .045       0  5006.5     .13       0
Bank Sta=4993.4,5006.5
XS Rating Curve= 0
Exp/Cntr=0.3,0.1

Type RM Length L Ch R = 1 ,44443.8 ,524.5,524.5,524.5
BEGIN DESCRIPTION:
Rock Creek 1 56.0
END DESCRIPTION:
XS GIS Cut Line= 4
      1862370.63       800111.08      1862423.26       799964.45
      1862786.08        799782.1      1863301.16       799770.82
#Sta/Elev= 30
  4439.2  614.89  4519.2  612.18  4539.2  613.14  4579.2  610.82    4615  609.87
    4655  606.39    4705   599.4    4735   596.8    4765  595.82    4865  594.89
    4885  595.79    4975  596.49    4985  596.25  4993.4   591.2  4994.9   588.2
  5005.1   588.2  5006.6   591.2  5011.1  594.91  5021.1  596.27  5091.1  595.37
  5101.1  596.32  5151.1  595.97  5171.1  596.73  5201.1  599.17  5211.1  600.56
  5231.1  605.19  5261.1  608.88  5311.1  613.01  5371.1  617.11  5516.3  622.51
#Mann= 3 , 1 , 0
  4439.2     .13       0  4993.4    .045       0  5006.6     .13       0
Bank Sta=4993.4,5006.6
XS Rating Curve= 0
Exp/Cntr=0.3,0.1

Type RM Length L Ch R = 1 ,43919.3 ,214.7,214.7,214.7
BEGIN DESCRIPTION:
Rock Creek 1 55.0
END DESCRIPTION:
XS GIS Cut Line= 3
      1862654.49        800361.1      1863030.46       800240.79
      1863274.85       800114.84
#Sta/Elev= 30
  4603.3  615.53  4613.3   615.4  4623.3  614.59  4643.3   612.2  4673.3  609.69
  4703.3  604.65  4733.3  598.69  4743.3  597.17  4753.3  596.31  4793.3  594.11
  4883.3  594.82  4913.3  593.78  4933.3  595.21  4973.3  595.64  4983.3  594.83
  4993.3  591.19  4994.8  588.19  5005.1  588.19  5006.6  591.19  5008.1  594.76
  5018.1  597.81  5028.1  595.89  5038.1  594.81  5058.1  595.72  5138.1  607.37
  5158.1  608.72  5198.1  613.39  5228.1  616.36  5248.1   617.4    5273  617.58
#Mann= 3 , 1 , 0
  4603.3     .13       0  4993.3    .045       0  5006.6     .13       0
Bank Sta=4993.3,5006.6
XS Rating Curve= 0
Exp/Cntr=0.5,0.3

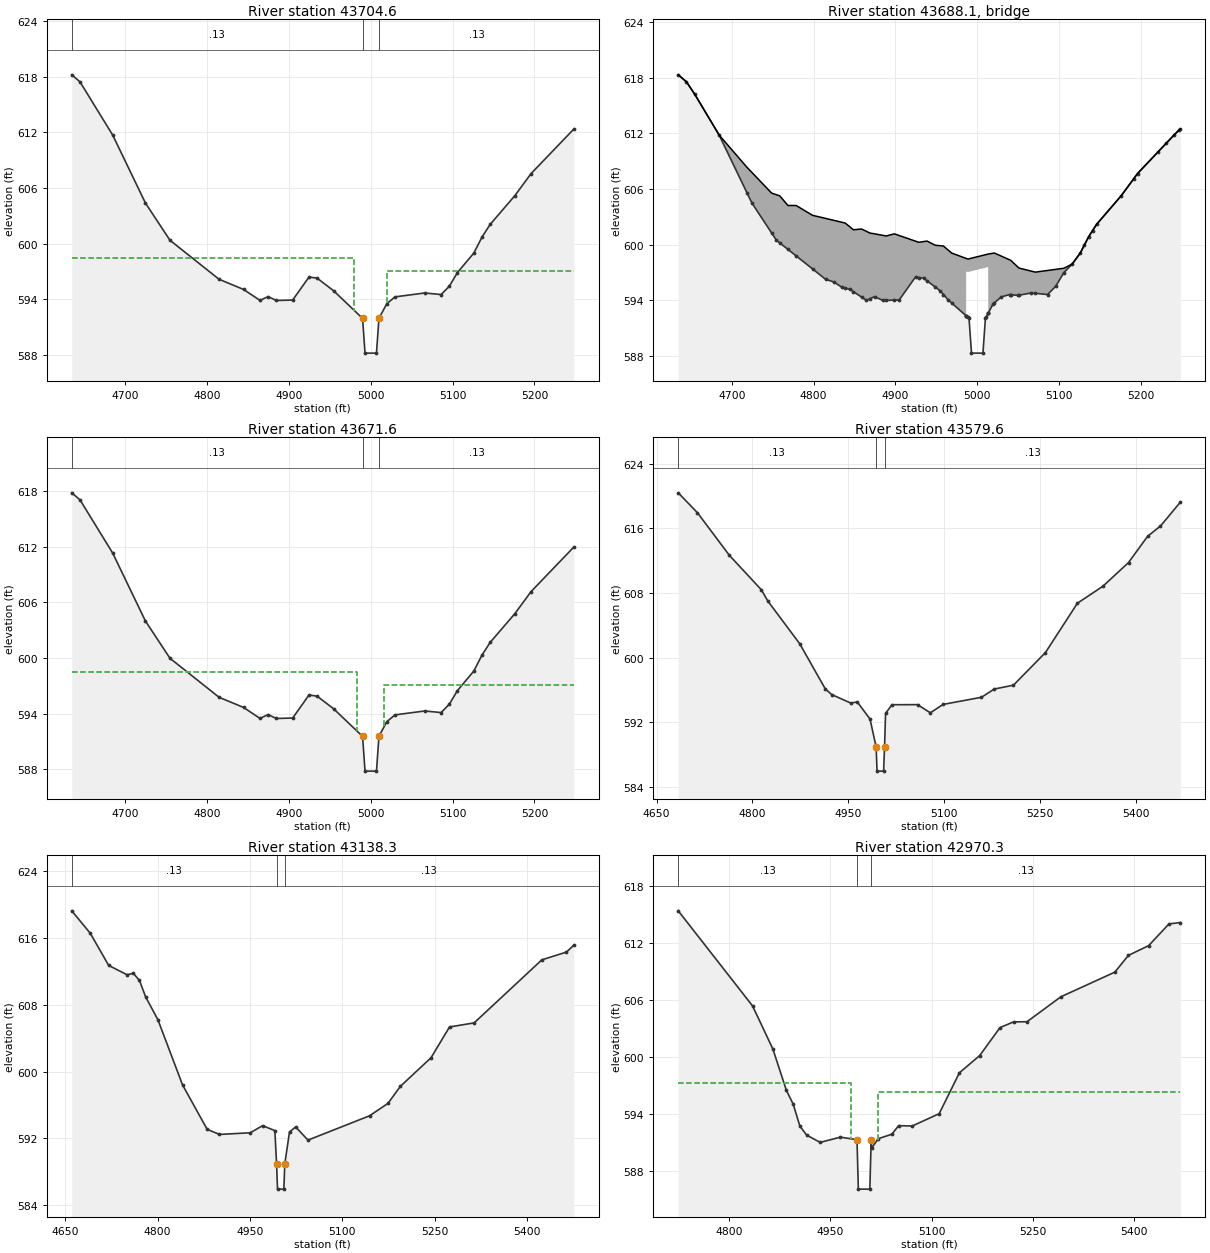
Type RM Length L Ch R = 1 ,43704.6 ,33,33,33
BEGIN DESCRIPTION:
Upstream Section of Bridge/Culvert/Weir
END DESCRIPTION:
XS GIS Cut Line= 3
      1862812.21       800561.12      1863147.84       800414.22
      1863372.16       800310.28
#Sta/Elev= 30
  4634.6  618.22  4644.6  617.47  4684.6  611.72  4724.6  604.39  4754.6  600.37
  4814.6  596.16  4844.6  595.06  4864.6  593.88  4874.6  594.29  4884.6  593.87
  4904.6  593.92  4924.6  596.41  4934.6  596.27  4954.6  594.92    4990  591.94
    4993  588.19    5007  588.19    5010  591.94  5019.6  593.52  5029.6  594.26
    5066  594.68    5086  594.51    5096  595.41    5106  596.89    5126  598.99
    5136  600.72    5146  602.09    5176  605.17    5196  607.57  5248.2  612.37
#Mann= 3 , 1 , 0
  4634.6     .13       0    4990    .045       0    5010     .13       0
#XS Ineff= 2 , 0
       0    4980  598.45    5020       0  597.04
Permanent Ineff=
       F       F
Bank Sta=4990,5010
XS Rating Curve= 0
Exp/Cntr=0.5,0.3

Type RM Length L Ch R = 3 ,43688.1 ,,,
BEGIN DESCRIPTION:
Thaxton Rd-TOR
Structure ID: NCF-0091
Approximate Survey Structure
END DESCRIPTION:
Bridge Culvert--1,0,-1,-1, 0
Deck Dist Width WeirC Skew NumUp NumDn MinLoCord MaxHiCord MaxSubmerge Is_Ogee
10,13,2.6,0, 58, 58, , , 0.95, 0, 1,1,,
  4634.6  4644.6  4654.6  4684.6  4718.7  4724.6  4748.7  4754.6  4758.7  4768.7
  4778.7  4798.7  4814.6  4824.6  4834.6  4838.7  4844.6  4848.7  4858.7  4864.6
  4868.7  4874.6  4884.6  4888.7  4898.7  4904.6  4924.6  4928.7  4934.6  4938.7
  4948.7  4954.6  4958.7  4964.6  4968.7 4986.41  4986.5  4988.7 5013.39  5013.5
  5019.6    5021  5029.6    5041    5051    5066    5071    5086    5096    5106
    5116    5126    5136    5146    5176    5196    5241  5248.2
  618.33  617.58  616.26  611.83  608.34   607.8  605.57  605.39  605.27  604.23
  604.23  603.17  602.84  602.63  602.42  602.33  601.91  601.61  601.69  601.44
  601.26  601.17  601.01  600.94  601.17  600.99  600.38  600.26  600.34  600.39
  599.94  599.89  599.86  599.41   599.1  598.52  598.52  598.45  598.99  598.99
  599.08   599.1  598.76  598.31  597.48  597.15  597.04  597.22  597.34  597.46
  597.91  599.11  600.84  602.21  605.29  607.69  611.88  612.48
  618.33  617.58  616.26  611.83  605.58   604.5  601.27  600.48  600.19  599.49
  598.79  597.39  596.27  595.98  595.41  595.31  595.17  594.93  594.34  593.99
  594.16   594.4  593.98  593.99  594.02  594.03  596.52  596.46  596.38   596.1
  595.43  595.03  594.62  594.03  593.71  592.33  597.12  597.05  597.59  592.63
  593.63  593.73  594.37  594.61  594.55  594.79  594.75  594.62  595.52     597
   597.9   599.1  600.83   602.2  605.28  607.68  611.87  612.48
  4634.6  4644.6  4654.6  4684.6  4718.7  4724.6  4748.7  4754.6  4758.7  4768.7
  4778.7  4798.7  4814.6  4824.6  4834.6  4838.7  4844.6  4848.7  4858.7  4864.6
  4868.7  4874.6  4884.6  4888.7  4898.7  4904.6  4924.6  4928.7  4934.6  4938.7
  4948.7  4954.6  4958.7  4964.6  4968.7 4986.41  4986.5  4988.7 5013.39  5013.5
  5019.6    5021  5029.6    5041    5051    5066    5071    5086    5096    5106
    5116    5126    5136    5146    5176    5196    5241  5248.2
  618.33  617.58  616.26  611.83  608.34   607.8  605.57  605.39  605.27  604.23
  604.23  603.17  602.84  602.63  602.42  602.33  601.91  601.61  601.69  601.44
  601.26  601.17  601.01  600.94  601.17  600.99  600.38  600.26  600.34  600.39
  599.94  599.89  599.86  599.41   599.1  598.52  598.52  598.45  598.99  598.99
  599.08   599.1  598.76  598.31  597.48  597.15  597.04  597.22  597.34  597.46
  597.91  599.11  600.84  602.21  605.29  607.69  611.88  612.48
  618.08  617.33  616.01  611.58  605.33  604.25  601.02  600.23  599.94  599.24
  598.54  597.14  596.02  595.73  595.16  595.06  594.92  594.68  594.09  593.74
  593.91  594.15  593.73  593.74  593.77  593.78  596.27  596.21  596.13  595.85
  595.18  594.78  594.37  593.78  593.46  592.08  596.87   596.8  597.34  592.38
  593.38  593.48  594.12  594.36   594.3  594.54   594.5  594.37  595.27  596.75
  597.65  598.85  600.58  601.95  605.03  607.43  611.62  612.23
BR Coef= 1 , 1 , 0 ,1.25, 0 ,,,0.8,0,2,0,
WSPro=,,,, 1 ,,,, 0 ,,,, 0 ,,,,-1 ,-1 ,-1 , 0 , 0 , 0 , 0 , 0
BR U #Sta/Elev= 73
  4634.6  618.33  4644.6  617.58  4654.6  616.26  4684.6  611.83  4718.7  605.58
  4724.6   604.5  4748.7  601.27  4754.6  600.48  4758.7  600.19  4768.7  599.49
  4778.7  598.79  4798.7  597.39  4814.6  596.27  4824.6  595.98  4834.6  595.41
  4838.7  595.31  4844.6  595.17  4848.7  594.93  4858.7  594.34  4864.6  593.99
  4868.7  594.16  4874.6   594.4  4884.6  593.98  4888.7  593.99  4898.7  594.02
  4904.6  594.03  4924.6  596.52  4928.7  596.46  4934.6  596.38  4938.7   596.1
  4948.7  595.43  4954.6  595.03  4958.7  594.62  4964.6  594.03  4968.7  593.71
 4986.41  592.33  4986.5  592.32  4986.6  592.32  4988.7  592.15    4990  592.05
    4993   588.3    5007   588.3    5010  592.05    5011  592.21  5013.3  592.59
 5013.39  592.61  5013.5  592.63  5019.6  593.63    5021  593.73  5029.6  594.37
  5039.6  594.62    5041  594.61  5049.6  594.53    5051  594.55    5066  594.79
    5071  594.75    5086  594.62    5096  595.52    5106     597    5116   597.9
    5126   599.1    5131  599.97    5136  600.83    5141  601.52    5146   602.2
    5176  605.28    5191  607.08    5196  607.68    5221  610.01    5231  610.94
    5241  611.87    5246  612.33  5248.2  612.48
BR U #Mann= 3
  4634.6     .13    4990    .045    5010     .13
BR U Banks=4990,5010
BR D #Sta/Elev= 73
  4634.6  618.08  4644.6  617.33  4654.6  616.01  4684.6  611.58  4718.7  605.33
  4724.6  604.25  4748.7  601.02  4754.6  600.23  4758.7  599.94  4768.7  599.24
  4778.7  598.54  4798.7  597.14  4814.6  596.02  4824.6  595.73  4834.6  595.16
  4838.7  595.06  4844.6  594.92  4848.7  594.68  4858.7  594.09  4864.6  593.74
  4868.7  593.91  4874.6  594.15  4884.6  593.73  4888.7  593.74  4898.7  593.77
  4904.6  593.78  4924.6  596.27  4928.7  596.21  4934.6  596.13  4938.7  595.85
  4948.7  595.18  4954.6  594.78  4958.7  594.37  4964.6  593.78  4968.7  593.46
 4986.41  592.08  4986.5  592.07  4986.6  592.07  4988.7   591.9    4990   591.8
    4993  588.05    5007  588.05    5010   591.8    5011  591.96  5013.3  592.34
 5013.39  592.36  5013.5  592.38  5019.6  593.38    5021  593.48  5029.6  594.12
  5039.6  594.37    5041  594.36  5049.6  594.28    5051   594.3    5066  594.54
    5071   594.5    5086  594.37    5096  595.27    5106  596.75    5116  597.65
    5126  598.85    5131  599.72    5136  600.58    5141  601.27    5146  601.95
    5176  605.03    5191  606.83    5196  607.43    5221  609.76    5231  610.69
    5241  611.62    5246  612.08  5248.2  612.23
BR D #Mann= 3
  4634.6     .13    4990    .045    5010     .13
BR D Banks=4990,5010
BC Design=,, 0 ,, 0 ,,,,,,
BC HTab HWMax=618.22

Type RM Length L Ch R = 1 ,43671.6 ,92,92,92
BEGIN DESCRIPTION:
Downstream Section of Bridge/Culvert/Weir
END DESCRIPTION:
XS GIS Cut Line= 3
      1862824.31       800591.82      1863159.94       800444.92
      1863384.25       800340.98
#Sta/Elev= 30
  4634.6  617.82  4644.6  617.07  4684.6  611.32  4724.6  603.99  4754.6  599.97
  4814.6  595.76  4844.6  594.66  4864.6  593.48  4874.6  593.89  4884.6  593.47
  4904.6  593.52  4924.6  596.01  4934.6  595.87  4954.6  594.52    4990  591.54
    4993  587.79    5007  587.79    5010  591.54  5019.6  593.12  5029.6  593.86
    5066  594.28    5086  594.11    5096  595.01    5106  596.49    5126  598.59
    5136  600.32    5146  601.69    5176  604.77    5196  607.17  5248.2  611.97
#Mann= 3 , 1 , 0
  4634.6     .13       0    4990    .045       0    5010     .13       0
#XS Ineff= 2 , 0
       0 4983.33  598.45 5016.67       0  597.04
Permanent Ineff=
       F       F
Bank Sta=4990,5010
XS Rating Curve= 0
Exp/Cntr=0.5,0.3

Type RM Length L Ch R = 1 ,43579.6 ,441.3,441.3,441.3
BEGIN DESCRIPTION:
Rock Creek 1 52.0
END DESCRIPTION:
XS GIS Cut Line= 3
      1862922.09       800698.87      1863186.43       800528.78
      1863612.81       800328.81
#Sta/Elev= 30
  4683.9  620.39  4713.9  617.93  4763.9  612.65  4813.9  608.39  4823.9  607.01
  4873.9  601.71  4913.9  596.12  4923.9  595.42  4953.9  594.36  4963.9  594.51
  4983.9  592.38  4993.4  588.94  4994.9  585.94  5005.1  585.94  5006.6  588.94
  5008.2  593.09  5018.2  594.16  5058.2  594.17  5078.2  593.16  5098.2   594.2
  5158.2  595.08  5178.2   596.1  5208.2  596.58  5258.2  600.61  5308.2  606.72
  5348.2  608.83  5388.2  611.76  5418.2  615.02  5438.2  616.28  5469.2  619.23
#Mann= 3 , 1 , 0
  4683.9     .13       0  4993.4    .045       0  5006.6     .13       0
Bank Sta=4993.4,5006.6
XS Rating Curve= 0
Exp/Cntr=0.3,0.1

Type RM Length L Ch R = 1 ,43138.3 ,168,168,168
BEGIN DESCRIPTION:
Rock Creek 1 51.0
END DESCRIPTION:
XS GIS Cut Line= 3
      1863048.51       800882.76      1863377.77       800827.95
       1863857.6       800873.56
#Sta/Elev= 30
  4660.5  619.26  4690.5  616.58  4720.5  612.72  4750.5   611.6  4760.5  611.78
  4770.5  610.92  4780.5  608.96  4800.5  606.21  4840.5  598.41  4880.5  593.09
  4900.5  592.48  4950.5  592.68  4970.5  593.53  4990.5  592.94  4993.3  588.93
  4994.8  585.93  5005.1  585.93  5006.6  588.93  5014.3  592.78  5024.3  593.38
  5044.3   591.8  5144.3  594.71  5174.3   596.2  5194.3  598.23  5244.3  601.67
  5274.3  605.35  5314.3  605.84  5424.3  613.39  5464.3  614.32  5476.3  615.15
#Mann= 3 , 1 , 0
  4660.5     .13       0  4993.3    .045       0  5006.6     .13       0
Bank Sta=4993.3,5006.6
XS Rating Curve= 0
Exp/Cntr=0.5,0.3

Type RM Length L Ch R = 1 ,42970.3 ,38,38,38
BEGIN DESCRIPTION:
Upstream Section of Bridge/Culvert/Weir
END DESCRIPTION:
XS GIS Cut Line= 3
      1863119.61        800954.6       1863386.4       800990.18
      1863859.93       801004.57
#Sta/Elev= 30
    4725  615.42    4835  605.41    4865  600.88    4885  596.53    4895  595.09
    4905  592.76    4915  591.82    4935  591.05    4965   591.6  4989.5  591.33
  4991.5  586.13  5008.5  586.13  5010.5  591.33  5011.1  590.45  5021.1  591.44
  5041.1  591.91  5051.1  592.81  5071.1  592.77  5111.1  594.07  5141.1  598.38
  5171.1  600.19  5201.1  603.13  5221.1  603.73  5241.1  603.75  5291.1  606.37
  5371.1  608.97  5391.1  610.73  5421.1  611.76  5451.1  614.04  5467.9  614.19
#Mann= 3 , 1 , 0
    4725     .13       0  4989.5    .045       0  5010.5     .13       0
#XS Ineff= 2 , 0
       0    4980   597.3    5020       0  596.35
Permanent Ineff=
       F       F
Bank Sta=4989.5,5010.5
XS Rating Curve= 0
Exp/Cntr=0.5,0.3

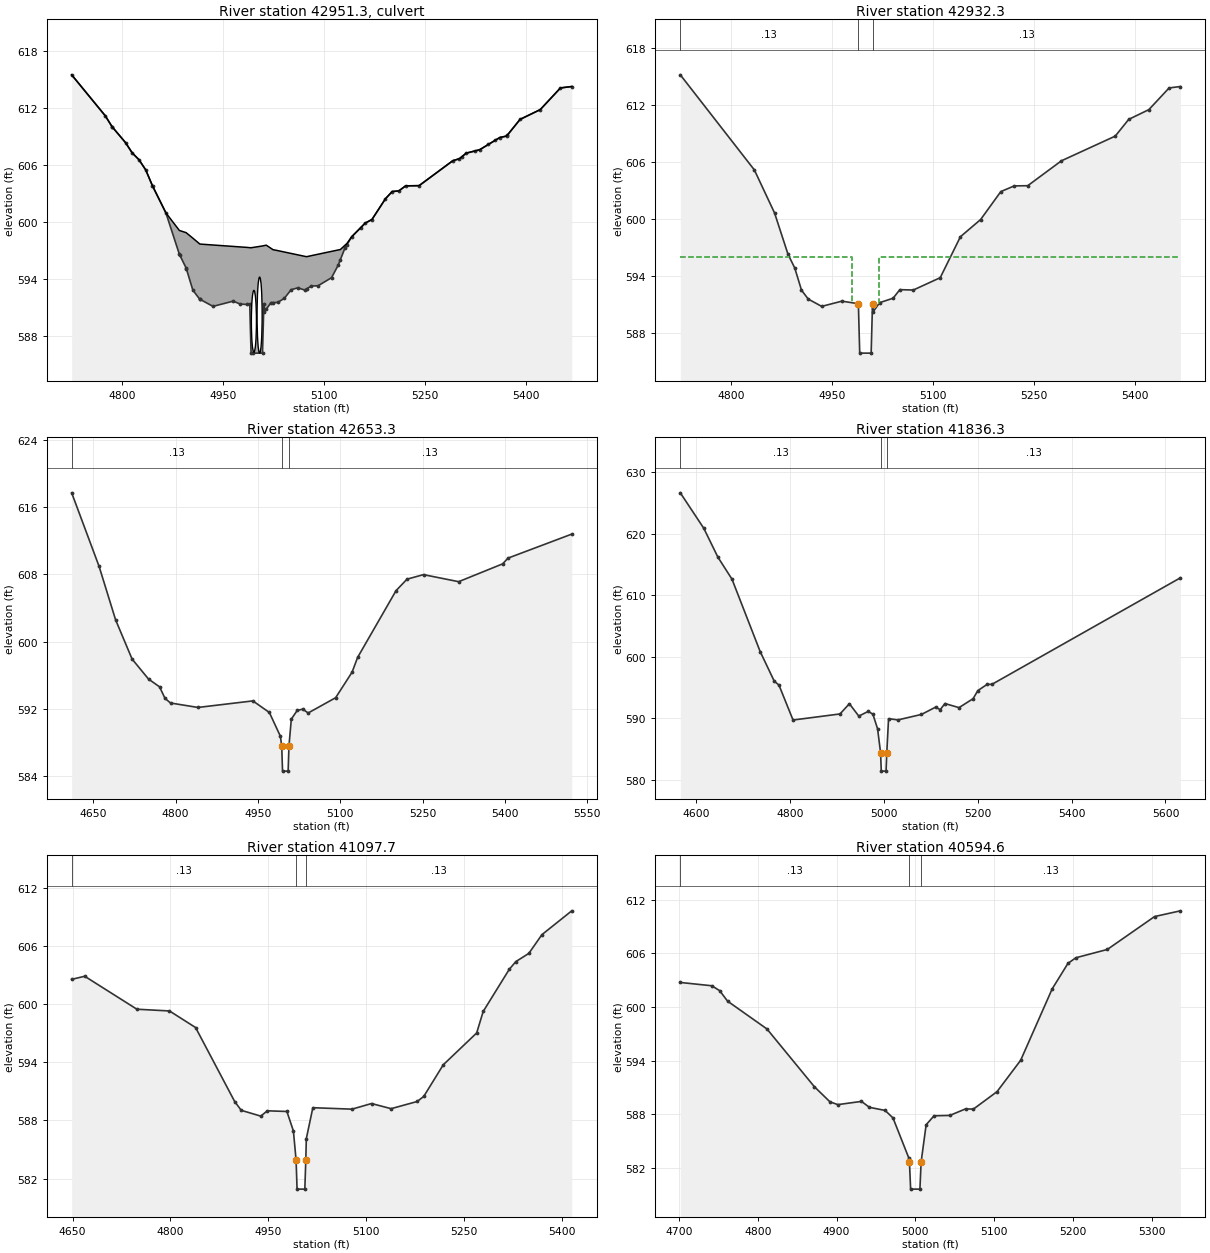
Type RM Length L Ch R = 2 ,42951.3 ,,,
BEGIN DESCRIPTION:
Charley Ln-TOR
Structure ID: NCF-0093
Approximate Survey Structure
END DESCRIPTION:
Bridge Culvert--1,0,-1,-1, 0
Deck Dist Width WeirC Skew NumUp NumDn MinLoCord MaxHiCord MaxSubmerge Is_Ogee
10,18,3,0, 56, 56, , , 0.95, 0, 1,1,,
    4725    4775    4785    4805    4815    4825    4835    4845    4865    4885
    4895    4905  4915.4    4935    4965    4975    4985  4989.5  4991.5  5008.5
  5010.5  5011.1  5014.1  5021.1  5024.1  5031.1  5041.1  5051.1  5061.1  5071.1
  5074.1  5081.1  5091.1  5111.1  5121.1  5124.1  5131.1  5134.1  5141.1  5161.1
  5171.1  5191.1  5201.1  5211.1  5221.1  5241.1  5291.1  5301.1  5311.1  5331.1
  5361.1  5371.1  5391.1  5421.1  5451.1  5467.9
  615.49  611.17  610.03  608.36  607.27  606.56  605.49  603.82  600.96  599.11
  598.88   598.3  597.68  597.58  597.43  597.38  597.33   597.3  597.29  597.48
  597.51  597.52  597.56  597.23  597.09  596.99  596.84  596.69  596.54  596.39
  596.35  596.46  596.61  596.91  597.06   597.1  597.56  597.76  598.46  599.89
  600.27  602.45  603.21  603.28  603.81  603.83  606.45  606.67  607.25  607.61
   608.9  609.05   610.8  611.83  614.11  614.26
  615.49  611.17  610.03  608.35  607.26  606.55  605.48  603.81  600.95   596.6
  595.16  592.83  591.87  591.12  591.67  591.37  591.32   591.4   586.2   586.2
   591.4  590.52  590.82  591.51  591.52  591.53  591.98  592.88  593.07  592.84
  592.97  593.26  593.29  594.14  595.48  596.02  597.28  597.63  598.45  599.88
  600.26  602.44   603.2  603.27   603.8  603.82  606.44  606.66  607.24   607.6
  608.89  609.04   610.8  611.83  614.11  614.26
    4725    4775    4785    4805    4815    4825    4835    4845    4865    4885
    4895    4905  4915.4    4935    4965    4975    4985  4989.5  4991.5  5008.5
  5010.5  5011.1  5014.1  5021.1  5024.1  5031.1  5041.1  5051.1  5061.1  5071.1
  5074.1  5081.1  5091.1  5111.1  5121.1  5124.1  5131.1  5134.1  5141.1  5161.1
  5171.1  5191.1  5201.1  5211.1  5221.1  5241.1  5291.1  5301.1  5311.1  5331.1
  5361.1  5371.1  5391.1  5421.1  5451.1  5467.9
  615.49  611.17  610.03  608.36  607.27  606.56  605.49  603.82  600.96  599.11
  598.88   598.3  597.68  597.58  597.43  597.38  597.33   597.3  597.29  597.48
  597.51  597.52  597.56  597.23  597.09  596.99  596.84  596.69  596.54  596.39
  596.35  596.46  596.61  596.91  597.06   597.1  597.56  597.76  598.46  599.89
  600.27  602.45  603.21  603.28  603.81  603.83  606.45  606.67  607.25  607.61
   608.9  609.05   610.8  611.83  614.11  614.26
   615.4  611.08  609.94  608.26  607.17  606.46  605.39  603.72  600.86  596.51
  595.07  592.74  591.78  591.03  591.58  591.28  591.23  591.31  586.11  586.11
  591.31  590.43  590.73  591.42  591.43  591.44  591.89  592.79  592.98  592.75
  592.88  593.17   593.2  594.05  595.39  595.93  597.19  597.54  598.36  599.79
  600.17  602.35  603.11  603.18  603.71  603.73  606.35  606.57  607.15  607.51
   608.8  608.95  610.71  611.74  614.02  614.17
BR Coef= 1 , 0 , 0 ,1.25, 0 ,,,0.8,-1,2,0,
WSPro=,,,, 1 ,,,, 0 ,,,, 0 ,,,,-1 ,-1 ,-1 , 0 , 0 , 0 , 0 , 0
Culvert=4,6.5,7.5,18,0.015,0.4,1,29,1,586.3,4995.7,586.11,4995.7,Culvert #1  , 0 ,10
Culvert Bottom n=0.015
Culvert=4,8,7.5,18,0.015,0.4,1,29,1,586.2,5004.2,586.11,5004.2,Culvert #2  , 0 ,10
Culvert Bottom n=0.015
BR U #Sta/Elev= 68
    4725  615.49    4775  611.17    4785  610.03  4785.4     610    4805  608.35
    4815  607.26    4825  606.55    4835  605.48    4845  603.81  4845.4  603.75
    4865  600.95    4885   596.6  4885.4  596.54    4895  595.16  4895.4  595.07
    4905  592.83    4915  591.89  4915.4  591.87    4935  591.12    4965  591.67
    4975  591.37    4985  591.32  4989.5   591.4  4991.5   586.2  4994.1   586.2
  5008.5   586.2  5010.5   591.4  5011.1  590.52  5014.1  590.82  5021.1  591.51
  5024.1  591.52  5031.1  591.53  5041.1  591.98  5051.1  592.88  5061.1  593.07
  5071.1  592.84  5074.1  592.97  5081.1  593.26  5091.1  593.29  5111.1  594.14
  5121.1  595.48  5124.1  596.02  5131.1  597.28  5134.1  597.63  5141.1  598.45
  5154.1  599.38  5161.1  599.88  5171.1  600.26  5191.1  602.44  5201.1   603.2
  5211.1  603.27  5221.1   603.8  5241.1  603.82  5291.1  606.44  5301.1  606.66
  5304.1  606.83  5311.1  607.24  5324.1  607.47  5331.1   607.6  5344.1  608.16
  5354.1  608.59  5361.1  608.89  5371.1  609.04  5372.4  609.15  5391.1   610.8
  5421.1  611.83  5451.1  614.11  5467.9  614.26
BR U #Mann= 3
    4725     .13  4989.5    .045  5010.5     .13
BR U Banks=4989.5,5010.5
BR D #Sta/Elev= 68
    4725   615.4    4775  611.08    4785  609.94  4785.4  609.91    4805  608.26
    4815  607.17    4825  606.46    4835  605.39    4845  603.72  4845.4  603.66
    4865  600.86    4885  596.51  4885.4  596.45    4895  595.07  4895.4  594.98
    4905  592.74    4915   591.8  4915.4  591.78    4935  591.03    4965  591.58
    4975  591.28    4985  591.23  4989.5  591.31  4991.5  586.11  4994.1  586.11
  5008.5  586.11  5010.5  591.31  5011.1  590.43  5014.1  590.73  5021.1  591.42
  5024.1  591.43  5031.1  591.44  5041.1  591.89  5051.1  592.79  5061.1  592.98
  5071.1  592.75  5074.1  592.88  5081.1  593.17  5091.1   593.2  5111.1  594.05
  5121.1  595.39  5124.1  595.93  5131.1  597.19  5134.1  597.54  5141.1  598.36
  5154.1  599.29  5161.1  599.79  5171.1  600.17  5191.1  602.35  5201.1  603.11
  5211.1  603.18  5221.1  603.71  5241.1  603.73  5291.1  606.35  5301.1  606.57
  5304.1  606.74  5311.1  607.15  5324.1  607.38  5331.1  607.51  5344.1  608.07
  5354.1   608.5  5361.1   608.8  5371.1  608.95  5372.4  609.06  5391.1  610.71
  5421.1  611.74  5451.1  614.02  5467.9  614.17
BR D #Mann= 3
    4725     .13  4989.5    .045  5010.5     .13
BR D Banks=4989.5,5010.5
BC Design=,, 0 ,, 0 ,,,,,,
BC HTab HWMax=615.42

Type RM Length L Ch R = 1 ,42932.3 ,279,279,279
BEGIN DESCRIPTION:
Downstream Section of Bridge/Culvert/Weir
END DESCRIPTION:
XS GIS Cut Line= 3
      1863119.61        800992.6       1863386.4       801028.18
      1863859.93       801042.57
#Sta/Elev= 30
    4725  615.16    4835  605.15    4865  600.62    4885  596.27    4895  594.83
    4905   592.5    4915  591.56    4935  590.79    4965  591.34  4989.5  591.07
  4991.5  585.87  5008.5  585.87  5010.5  591.07  5011.1  590.19  5021.1  591.18
  5041.1  591.65  5051.1  592.55  5071.1  592.51  5111.1  593.81  5141.1  598.12
  5171.1  599.93  5201.1  602.87  5221.1  603.47  5241.1  603.49  5291.1  606.11
  5371.1  608.71  5391.1  610.47  5421.1   611.5  5451.1  613.78  5467.9  613.93
#Mann= 3 , 1 , 0
    4725     .13       0  4989.5    .045       0  5010.5     .13       0
#XS Ineff= 2 , 0
       0    4980     596    5020       0     596
Permanent Ineff=
       F       F
Bank Sta=4989.5,5010.5
XS Rating Curve= 0
Exp/Cntr=0.5,0.3

Type RM Length L Ch R = 1 ,42653.3 ,817,817,817
BEGIN DESCRIPTION:
Rock Creek 1 48.0
END DESCRIPTION:
XS GIS Cut Line= 4
      1863043.83       801059.23      1863385.87        801267.9
      1863616.05       801375.45      1863872.04        801373.3
#Sta/Elev= 30
  4610.9  617.73  4660.9  608.95  4690.9  602.59  4720.9  597.92  4750.9  595.53
  4770.9  594.61  4780.9  593.23  4790.9  592.68  4840.9  592.15  4940.9  592.93
  4970.9  591.55  4990.9  588.73  4993.4  587.56  4994.9  584.56  5005.1  584.56
  5006.6  587.56  5010.9  590.76  5021.6  591.79  5031.6  591.95  5041.6  591.49
  5091.6  593.31  5121.6  596.36  5131.6  598.11  5201.6  606.07  5221.6  607.44
  5251.6  607.98  5315.6  607.14  5395.6  609.26  5405.6  609.95  5521.6  612.81
#Mann= 3 , 1 , 0
  4610.9     .13       0  4993.4    .045       0  5006.6     .13       0
Bank Sta=4993.4,5006.6
XS Rating Curve= 0
Exp/Cntr=0.3,0.1

Type RM Length L Ch R = 1 ,41836.3 ,738.6,738.6,738.6
BEGIN DESCRIPTION:
Rock Creek 1 47.0
END DESCRIPTION:
XS GIS Cut Line= 3
      1862944.87       801883.14      1863361.31       801762.98
      1863874.19       801394.82
#Sta/Elev= 30
    4567  626.64    4617  620.87    4647  616.18    4677   612.6    4737  600.83
    4767  596.01    4777  595.38    4807  589.69    4907  590.68    4927  592.34
    4947  590.33    4967  591.09    4977  590.65    4987  588.26  4993.4  584.38
  4994.9  581.38  5005.1  581.38  5006.6  584.38  5010.4  589.91  5030.4  589.71
  5080.4   590.6  5110.4  591.78  5120.4  591.38  5130.4  592.37  5160.4  591.71
  5190.4  593.16  5200.4  594.47  5220.4   595.5  5230.4  595.49  5631.8  612.82
#Mann= 3 , 1 , 0
    4567     .13       0  4993.4    .045       0  5006.6     .13       0
Bank Sta=4993.4,5006.6
XS Rating Curve= 0
Exp/Cntr=0.3,0.1

Type RM Length L Ch R = 1 ,41097.7 ,503.1,503.1,503.1
BEGIN DESCRIPTION:
Rock Creek 1 45.0
END DESCRIPTION:
XS GIS Cut Line= 4
      1863338.54       802470.41      1863523.55       802173.55
      1863689.19       802012.21      1863874.19         801995.
#Sta/Elev= 30
  4648.5  602.55  4668.5  602.87  4748.5  599.47  4798.5  599.29  4838.5  597.58
  4898.5  589.94  4908.5  589.04  4938.5  588.44  4948.5  588.99  4978.5  588.92
  4988.5  586.91  4992.6  583.91  4994.1  580.91    5006  580.91  5007.5  583.91
  5008.3  586.12  5018.3  589.31  5078.3  589.16  5108.3  589.74  5138.3  589.21
  5178.3  589.95  5188.3  590.47  5218.3  593.74  5269.5  597.02  5279.5  599.24
  5319.5  603.59  5329.5  604.38  5349.5  605.23  5369.5  607.16  5415.3  609.62
#Mann= 3 , 1 , 0
  4648.5     .13       0  4992.6    .045       0  5007.5     .13       0
Bank Sta=4992.6,5007.5
XS Rating Curve= 0
Exp/Cntr=0.3,0.1

Type RM Length L Ch R = 1 ,40594.6 ,451.3,451.3,451.3
BEGIN DESCRIPTION:
Rock Creek 1 44.0
END DESCRIPTION:
XS GIS Cut Line= 3
      1863321.33       802474.72       1863618.2       802530.65
      1863949.48       802498.38
#Sta/Elev= 30
  4701.7  602.76  4741.7  602.39  4751.7  601.84  4761.7  600.67  4811.7  597.56
  4871.7  591.12  4891.7  589.41  4901.7   589.1  4931.7  589.46  4941.7   588.8
  4961.7  588.45  4971.7  587.61  4991.7  583.15  4992.6  582.67  4994.1  579.65
  5005.9  579.65  5007.4  582.67  5013.8  586.85  5023.8  587.85  5043.8  587.89
  5063.8  588.62  5073.8   588.6  5103.8  590.55  5133.8  594.06  5173.8  602.04
  5193.8  604.89  5203.8  605.52  5243.8  606.45  5303.8  610.13  5336.6  610.77
#Mann= 3 , 1 , 0
  4701.7     .13       0  4992.6    .045       0  5007.4     .13       0
Bank Sta=4992.6,5007.4
XS Rating Curve= 0
Exp/Cntr=0.3,0.1

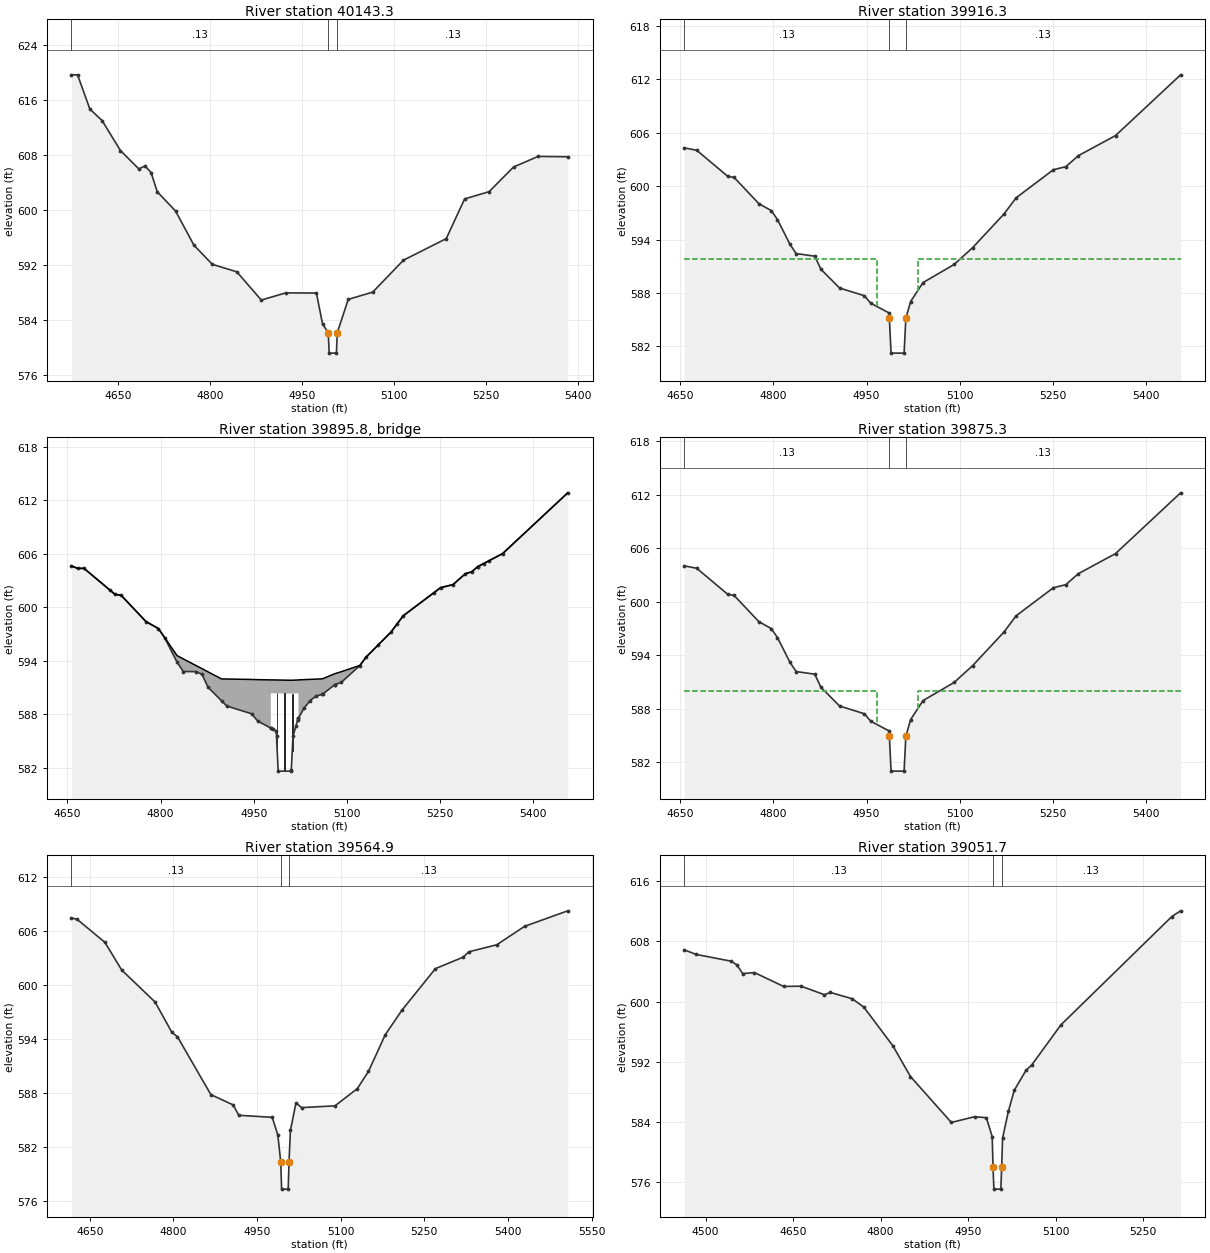
Type RM Length L Ch R = 1 ,40143.3 ,227,227,227
BEGIN DESCRIPTION:
Rock Creek 1 43.0
END DESCRIPTION:
XS GIS Cut Line= 3
      1863129.88       802778.03       1863534.3        802898.5
      1863904.31       803016.82
#Sta/Elev= 30
  4573.3  619.71  4583.3   619.7  4603.3  614.72  4623.3  613.04  4653.3  608.66
  4683.3  605.99  4693.3  606.42  4703.3  605.46  4713.3  602.66  4743.3  599.84
  4773.3  594.86  4803.3  592.07  4843.3  590.98  4883.3  586.86  4923.3  587.91
  4973.3  587.88  4983.3  583.37  4992.6  582.12  4994.1  579.12  5005.9  579.12
  5007.4  582.12  5025.3  586.96  5065.3  588.02  5115.3  592.67  5185.3  595.82
  5215.3  601.61  5255.3  602.67  5295.3  606.27  5335.3  607.81  5383.7  607.76
#Mann= 3 , 1 , 0
  4573.3     .13       0  4992.6    .045       0  5007.4     .13       0
Bank Sta=4992.6,5007.4
XS Rating Curve= 0
Exp/Cntr=0.5,0.3

Type RM Length L Ch R = 1 ,39916.3 ,41,41,41
BEGIN DESCRIPTION:
Upstream Section of Bridge/Culvert/Weir
END DESCRIPTION:
XS GIS Cut Line= 3
      1863212.25       803010.18      1863542.78       803105.81
      1863985.19        803212.6
#Sta/Elev= 30
  4656.6  604.29  4676.6  604.02  4726.6  601.09  4736.6  600.98  4776.6  598.03
  4796.6  597.25  4806.6  596.24  4826.6  593.48  4836.6  592.43  4866.6  592.13
  4876.6  590.66  4906.6  588.56  4946.6  587.69  4956.6  586.86  4986.6  585.75
  4986.8  585.15  4989.5  581.25  5010.5  581.25  5013.3  585.15    5021  587.04
    5041  589.17    5091   591.2    5121   593.1    5171  596.84    5191  598.69
    5251  601.84    5271  602.18    5291  603.41    5351  605.67  5455.8  612.49
#Mann= 3 , 1 , 0
  4656.6     .13       0  4986.8    .045       0  5013.3     .13       0
#XS Ineff= 2 , 0
       0  4967.6   591.8  5032.1       0   591.8
Permanent Ineff=
       F       F
Bank Sta=4986.8,5013.3
XS Rating Curve= 0
Exp/Cntr=0.5,0.3

Type RM Length L Ch R = 3 ,39895.8 ,,,
BEGIN DESCRIPTION:
Russell Mcpherson Rd-TOR
Structure ID: NCF-0092
Approximate Survey Structure
END DESCRIPTION:
Bridge Culvert--1,0,-1,-1, 0
Deck Dist Width WeirC Skew NumUp NumDn MinLoCord MaxHiCord MaxSubmerge Is_Ogee
10,21,2.6,0, 56, 56, , , 0.95, 0, 1,1,,
  4656.6  4666.6  4676.6  4718.3  4726.6  4736.6  4776.6  4796.6  4806.6  4826.6
  4836.6  4856.6  4866.6  4876.6  4898.3  4906.6  4946.6  4956.6 4977.61  4977.7
  4981.7  4986.6  4986.8  4989.5  5010.5  5010.6  5013.3  5018.2    5021 5022.09
  5022.2    5031    5041    5051  5060.6    5061  5080.6    5081    5091    5121
    5131  5150.6    5171  5180.6    5191  5240.6    5251    5271    5291    5301
  5310.6    5311  5320.6  5329.2    5351  5455.8
  604.64  604.35  604.37  601.94  601.45  601.34  598.39  597.61   596.6  594.57
   594.2  593.47  593.11  592.74  591.95  591.94  591.89  591.87  591.84  591.84
  591.84  591.83  591.83  591.83   591.8   591.8  591.81  591.82  591.83  591.84
  591.84  591.87   591.9  591.93  591.96  591.97  592.53  592.54  592.76  593.46
   594.4  595.77   597.2  598.09  599.05  601.65   602.2  602.54  603.77  603.97
  604.54  604.56  604.91  605.23  606.02  612.84
  604.64  604.35  604.37  601.93  601.44  601.33  598.38   597.6  596.59  593.83
  592.78  592.77  592.48  591.01  589.49  588.91  588.04  587.21  586.43  590.34
  590.34  590.33  590.33  590.33   590.3   590.3  590.31  590.32  590.33  590.34
  587.54  588.65  589.52  590.05  590.22  590.23   591.3  591.32  591.55  593.45
  594.39  595.76  597.19  598.08  599.04  601.64  602.19  602.53  603.76  603.96
  604.53  604.55   604.9  605.22  606.02  612.84
  4656.6  4666.6  4676.6  4718.3  4726.6  4736.6  4776.6  4796.6  4806.6  4826.6
  4836.6  4856.6  4866.6  4876.6  4898.3  4906.6  4946.6  4956.6 4977.61  4977.7
  4981.7  4986.6  4986.8  4989.5  5010.5  5010.6  5013.3  5018.2    5021 5022.09
  5022.2    5031    5041    5051  5060.6    5061  5080.6    5081    5091    5121
    5131  5150.6    5171  5180.6    5191  5240.6    5251    5271    5291    5301
  5310.6    5311  5320.6  5329.2    5351  5455.8
  604.64  604.35  604.37  601.94  601.45  601.34  598.39  597.61   596.6  594.57
   594.2  593.47  593.11  592.74  591.95  591.94  591.89  591.87  591.84  591.84
  591.84  591.83  591.83  591.83   591.8   591.8  591.81  591.82  591.83  591.84
  591.84  591.87   591.9  591.93  591.96  591.97  592.53  592.54  592.76  593.46
   594.4  595.77   597.2  598.09  599.05  601.65   602.2  602.54  603.77  603.97
  604.54  604.56  604.91  605.23  606.02  612.84
  604.39   604.1  604.12  601.68  601.19  601.08  598.13  597.35  596.34  593.58
  592.53  592.52  592.23  590.76  589.24  588.66  587.79  586.96  586.18  590.09
  590.09  590.08  590.08  590.08  590.05  590.05  590.06  590.07  590.08  590.09
  587.29   588.4  589.27   589.8  589.97  589.98  591.05  591.07   591.3   593.2
  594.14  595.51  596.94  597.83  598.79  601.39  601.94  602.28  603.51  603.71
  604.28   604.3  604.65  604.97  605.77  612.59
Pier Skew, UpSta & Num, DnSta & Num=  ,4987.8, 2 ,4987.8, 2 , 0 , 0 , 0 ,,
       1       1
  582.33  591.33
       1       1
  582.08  591.08
Pier Skew, UpSta & Num, DnSta & Num=  ,5000, 2 ,5000, 2 , 0 , 0 , 0 ,,
       1       1
   580.6  591.32
       1       1
  580.35  591.07
Pier Skew, UpSta & Num, DnSta & Num=  ,5012.1, 2 ,5012.1, 2 , 0 , 0 , 0 ,,
       1       1
  582.13  591.31
       1       1
  581.88  591.06
Abutment Skew #Up #Dn= , 2 , 2
  4977.5  4981.7
  590.34  586.28
  4977.5  4981.7
  590.09  586.03
Abutment Skew #Up #Dn= , 2 , 2
  5018.2 5022.29
   586.7  590.34
  5018.2 5022.29
  586.45  590.09
BR Coef= 1 , 1 , 0 ,1.25, 0 ,,,0.8,0,2,0,
WSPro=,,,, 1 ,,,, 0 ,,,, 0 ,,,,-1 ,-1 ,-1 , 0 , 0 , 0 , 0 , 0
BR U #Sta/Elev= 56
  4656.6  604.64  4666.6  604.35  4676.6  604.37  4718.3  601.93  4726.6  601.44
  4736.6  601.33  4776.6  598.38  4796.6   597.6  4806.6  596.59  4826.6  593.83
  4836.6  592.78  4856.6  592.77  4866.6  592.48  4876.6  591.01  4898.3  589.49
  4906.6  588.91  4946.6  588.04  4956.6  587.21 4977.61  586.43  4977.7  586.43
  4981.7  586.28  4986.6   586.1  4986.8   585.5  4989.5   581.6  5010.5   581.6
  5010.6  581.74  5013.3   585.5  5018.2   586.7    5021  587.39 5022.09  587.53
  5022.2  587.54    5031  588.65    5041  589.52    5051  590.05  5060.6  590.22
    5061  590.23  5080.6   591.3    5081  591.32    5091  591.55    5121  593.45
    5131  594.39  5150.6  595.76    5171  597.19  5180.6  598.08    5191  599.04
  5240.6  601.64    5251  602.19    5271  602.53    5291  603.76    5301  603.96
  5310.6  604.53    5311  604.55  5320.6   604.9  5329.2  605.22    5351  606.02
  5455.8  612.84
BR U #Mann= 3
  4656.6     .13  4986.8    .045  5013.3     .13
BR U Banks=4986.8,5013.3
BR D #Sta/Elev= 56
  4656.6  604.39  4666.6   604.1  4676.6  604.12  4718.3  601.68  4726.6  601.19
  4736.6  601.08  4776.6  598.13  4796.6  597.35  4806.6  596.34  4826.6  593.58
  4836.6  592.53  4856.6  592.52  4866.6  592.23  4876.6  590.76  4898.3  589.24
  4906.6  588.66  4946.6  587.79  4956.6  586.96 4977.61  586.18  4977.7  586.18
  4981.7  586.03  4986.6  585.85  4986.8  585.25  4989.5  581.35  5010.5  581.35
  5010.6  581.49  5013.3  585.25  5018.2  586.45    5021  587.14 5022.09  587.28
  5022.2  587.29    5031   588.4    5041  589.27    5051   589.8  5060.6  589.97
    5061  589.98  5080.6  591.05    5081  591.07    5091   591.3    5121   593.2
    5131  594.14  5150.6  595.51    5171  596.94  5180.6  597.83    5191  598.79
  5240.6  601.39    5251  601.94    5271  602.28    5291  603.51    5301  603.71
  5310.6  604.28    5311   604.3  5320.6  604.65  5329.2  604.97    5351  605.77
  5455.8  612.59
BR D #Mann= 3
  4656.6     .13  4986.8    .045  5013.3     .13
BR D Banks=4986.8,5013.3
BC Design=,, 0 ,, 0 ,,,,,,
BC HTab HWMax=612.49

Type RM Length L Ch R = 1 ,39875.3 ,310.4,310.4,310.4
BEGIN DESCRIPTION:
Downstream Section of Bridge/Culvert/Weir
END DESCRIPTION:
XS GIS Cut Line= 3
      1863212.25       803051.18      1863542.78       803146.81
      1863985.19        803253.6
#Sta/Elev= 30
  4656.6  604.03  4676.6  603.76  4726.6  600.83  4736.6  600.72  4776.6  597.77
  4796.6  596.99  4806.6  595.98  4826.6  593.22  4836.6  592.17  4866.6  591.87
  4876.6   590.4  4906.6   588.3  4946.6  587.43  4956.6   586.6  4986.6  585.49
  4986.8  584.89  4989.5  580.99  5010.5  580.99  5013.3  584.89    5021  586.78
    5041  588.91    5091  590.94    5121  592.84    5171  596.58    5191  598.43
    5251  601.58    5271  601.92    5291  603.15    5351  605.41  5455.8  612.23
#Mann= 3 , 1 , 0
  4656.6     .13       0  4986.8    .045       0  5013.3     .13       0
#XS Ineff= 2 , 0
       0  4967.6     590  5032.1       0     590
Permanent Ineff=
       F       F
Bank Sta=4986.8,5013.3
XS Rating Curve= 0
Exp/Cntr=0.5,0.3

Type RM Length L Ch R = 1 ,39564.9 ,513.2,513.2,513.2
BEGIN DESCRIPTION:
Rock Creek 1 40.0
END DESCRIPTION:
XS GIS Cut Line= 3
      1863057.93       803120.28      1863354.66       803361.87
      1863822.09       803558.82
#Sta/Elev= 30
  4617.3  607.43  4627.3  607.28  4677.3  604.72  4707.3  601.65  4767.3  598.09
  4797.3  594.73  4807.3  594.24  4867.3  587.81  4907.3  586.67  4917.3  585.52
  4977.3  585.29  4987.3  583.34  4992.6  580.32  4994.1  577.32  5005.9  577.32
  5007.4  580.32  5009.9  583.84  5019.9   586.9  5029.9  586.37  5089.9  586.57
  5129.9  588.48  5149.9  590.39  5179.9  594.45  5209.9  597.19  5269.9   601.8
  5319.9  603.08  5329.9  603.67  5379.9  604.45  5429.9   606.5  5507.2  608.22
#Mann= 3 , 1 , 0
  4617.3     .13       0  4992.6    .045       0  5007.4     .13       0
Bank Sta=4992.6,5007.4
XS Rating Curve= 0
Exp/Cntr=0.3,0.1

Type RM Length L Ch R = 1 ,39051.7 ,394.6,394.6,394.6
BEGIN DESCRIPTION:
Rock Creek 1 39.0
END DESCRIPTION:
XS GIS Cut Line= 4
      1862784.82       803356.62      1862939.76       803574.58
      1863178.72       803695.37      1863420.31       803897.58
#Sta/Elev= 30
  4463.7  606.86  4483.7  606.26  4543.7  605.36  4553.7  604.87  4563.7  603.71
  4583.7  603.85  4633.7  602.01  4663.7  602.04  4703.7  600.91  4713.7  601.21
  4751.1  600.38  4771.1  599.27  4821.1  594.11  4851.1  590.05  4921.1  583.96
  4961.1  584.72  4981.1  584.59  4991.1  582.08  4992.5  578.11    4994  575.11
  5005.9  575.11  5007.4  578.11  5008.9  581.87  5018.9  585.45  5028.9  588.22
  5048.9  590.86  5058.9  591.59  5108.9  596.91  5298.9  611.28  5313.9  612.04
#Mann= 3 , 1 , 0
  4463.7     .13       0  4992.5    .045       0  5007.4     .13       0
Bank Sta=4992.5,5007.4
XS Rating Curve= 0
Exp/Cntr=0.3,0.1