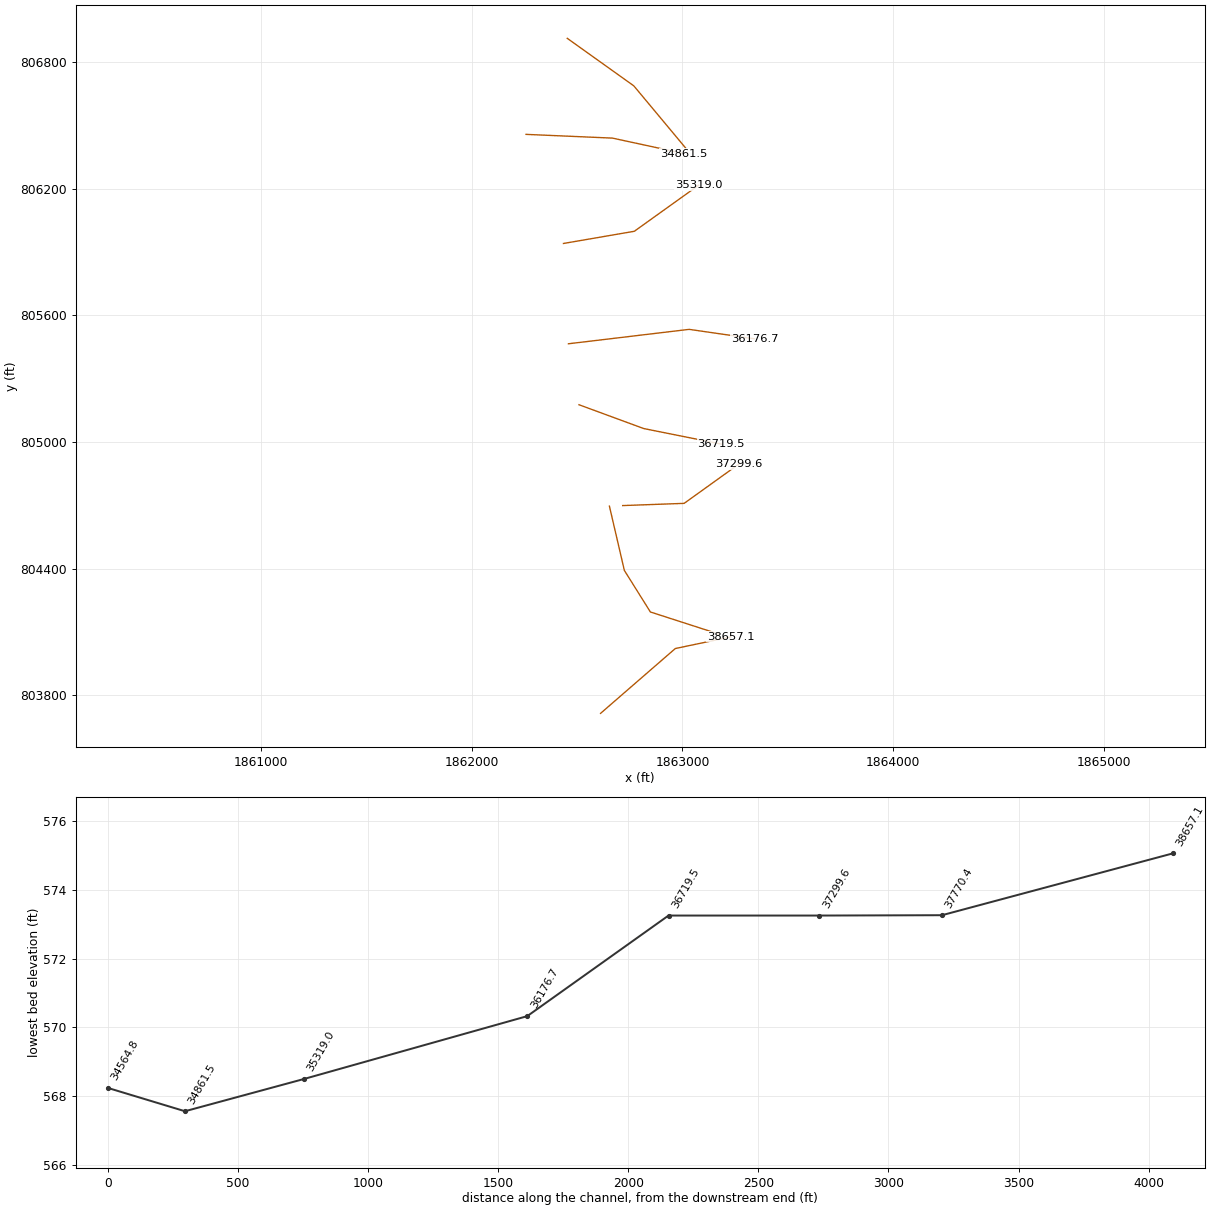
HEC-RAS study ROCK CREEK 1.PRJ: Rock Creek 1

--- ROCK CREEK 1.g01 (geometry) --- (continued)

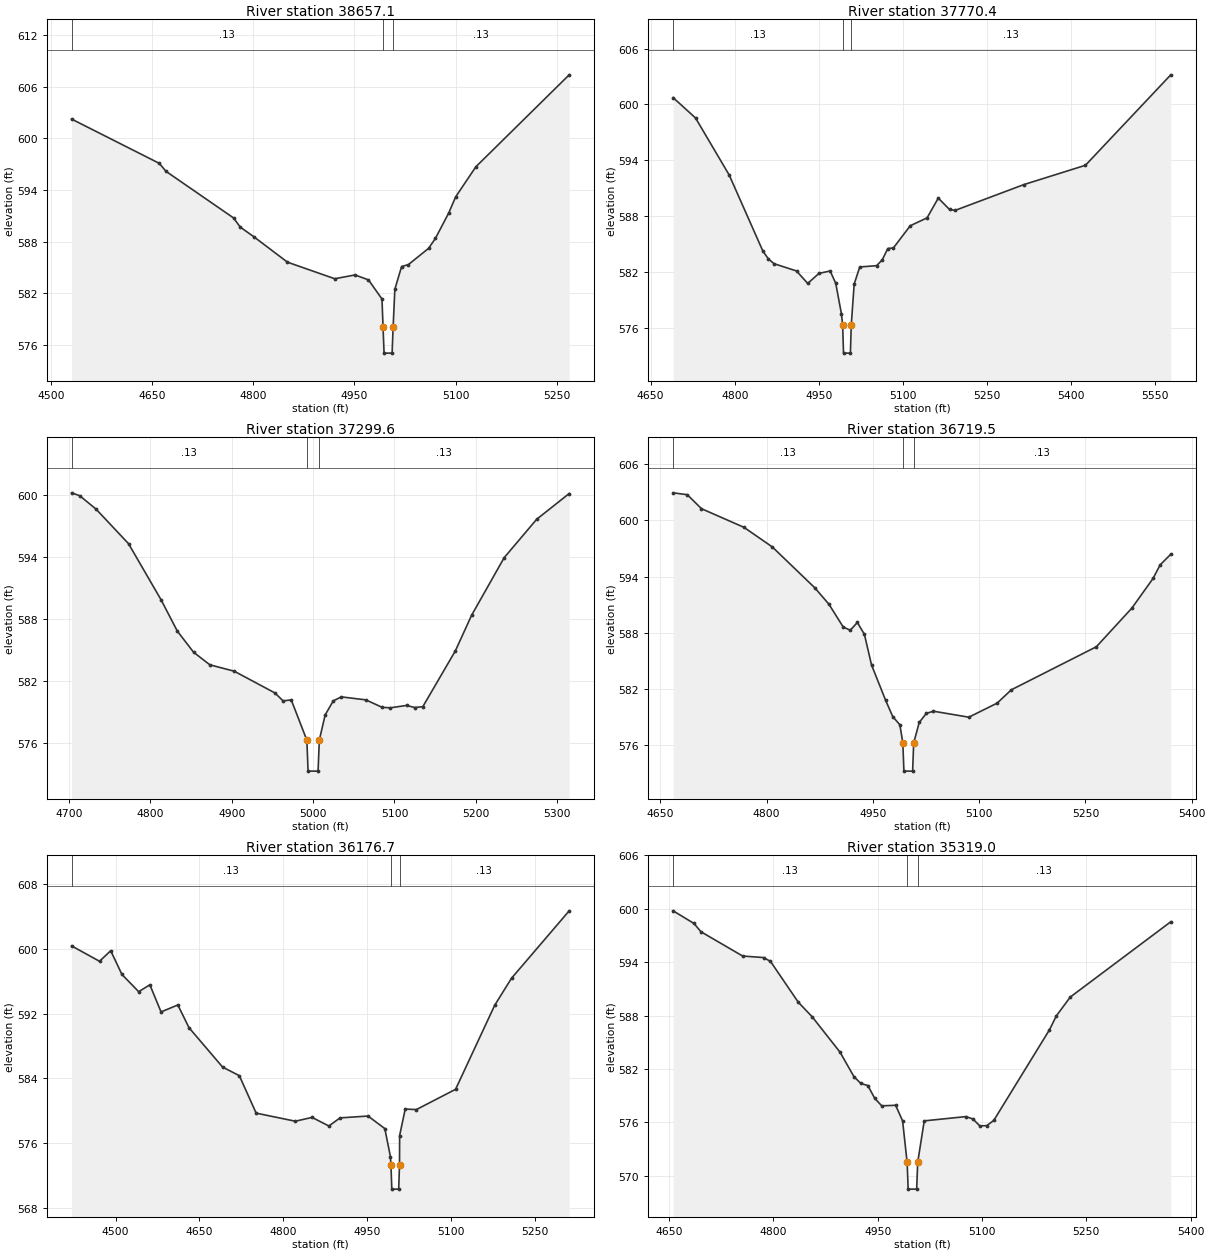
Type RM Length L Ch R = 1 ,38657.1 ,886.7,886.7,886.7
BEGIN DESCRIPTION:
Rock Creek 1 38.0
END DESCRIPTION:
XS GIS Cut Line= 3
      1862611.51       803713.76      1862966.02         804021.
      1863228.62       804076.14
#Sta/Elev= 24
  4530.9  602.23  4660.9  597.09  4670.9  596.16  4770.9  590.76  4780.9  589.69
  4800.9  588.58  4850.9  585.62  4920.9   583.7  4950.9  584.14  4970.9  583.57
  4990.9  581.35  4992.5  578.07    4994  575.07  5005.9  575.07  5007.4  578.07
    5010  582.49    5020  585.12    5030  585.34    5060  587.23    5070  588.37
    5090  591.36    5100  593.19    5130  596.69  5268.3  607.36
#Mann= 3 , 1 , 0
  4530.9     .13       0  4992.5    .045       0  5007.4     .13       0
Bank Sta=4992.5,5007.4
XS Rating Curve= 0
Exp/Cntr=0.3,0.1

Type RM Length L Ch R = 1 ,37770.4 ,470.8,470.8,470.8
BEGIN DESCRIPTION:
Rock Creek 1 37.0
END DESCRIPTION:
XS GIS Cut Line= 4
      1862653.52       804695.88      1862724.43       804391.26
      1862847.85       804194.31      1863173.47       804089.27
#Sta/Elev= 30
  4690.1  600.73  4730.1  598.54  4790.1  592.41  4850.1  584.24  4860.1  583.38
  4870.1  582.88  4910.1   582.1  4930.1  580.76  4950.1  581.84  4970.1   582.1
  4980.1  580.76  4990.1  577.52  4992.4  576.27  4993.9  573.27  5006.2  573.27
  5007.7  576.27  5012.9  580.69  5022.9  582.53  5052.9  582.67  5062.9  583.29
  5072.9  584.51  5082.9  584.58  5112.9  586.96  5142.9  587.81  5162.9  589.93
  5182.9  588.71  5192.9  588.61  5315.3  591.38  5425.3  593.46  5577.4  603.18
#Mann= 3 , 1 , 0
  4690.1     .13       0  4992.4    .045       0  5007.7     .13       0
Bank Sta=4992.4,5007.7
XS Rating Curve= 0
Exp/Cntr=0.3,0.1

Type RM Length L Ch R = 1 ,37299.6 ,580.1,580.1,580.1
BEGIN DESCRIPTION:
Rock Creek 1 36.0
END DESCRIPTION:
XS GIS Cut Line= 3
      1862716.55        804698.5      1863008.03       804709.01
      1863268.01       804895.45
#Sta/Elev= 30
  4703.1  600.25  4713.1  599.97  4733.1  598.68  4773.1  595.32  4813.1  589.88
  4833.1  586.84  4853.1  584.79  4873.1  583.57  4903.1  582.95  4953.1  580.84
  4963.1  580.07  4973.1  580.17  4992.3  576.26  4993.8  573.26  5006.1  573.26
  5007.6  576.26  5014.8  578.71  5024.8  580.08  5034.8  580.46  5064.8  580.17
  5084.8  579.45  5094.8   579.4  5114.8  579.63  5124.8  579.43  5134.8  579.51
  5174.8  584.92  5194.8  588.38  5234.8  593.96  5274.8  597.69  5314.7  600.18
#Mann= 3 , 1 , 0
  4703.1     .13       0  4992.3    .045       0  5007.6     .13       0
Bank Sta=4992.3,5007.6
XS Rating Curve= 0
Exp/Cntr=0.3,0.1

Type RM Length L Ch R = 1 ,36719.5 ,542.8,542.8,542.8
BEGIN DESCRIPTION:
Rock Creek 1 34.0
END DESCRIPTION:
XS GIS Cut Line= 3
      1862509.09       805176.43      1862816.34       805063.52
      1863183.97       804989.99
#Sta/Elev= 30
  4668.2  602.93  4688.2  602.73  4708.2  601.24  4768.2  599.25  4808.2  597.16
  4868.2   592.8  4888.2  591.04  4908.2  588.63  4918.2  588.28  4928.2  589.11
  4938.2  587.83  4948.2  584.58  4968.2  580.79  4978.2  579.07  4988.2   578.2
  4992.4  576.26  4993.9  573.26  5006.2  573.26  5007.7  576.26  5015.5  578.45
  5025.5  579.41  5035.5  579.65  5085.5  579.01  5125.5  580.51  5145.5  581.93
  5265.5  586.52  5315.5  590.63  5345.5   593.8  5355.5  595.25  5370.5  596.38
#Mann= 3 , 1 , 0
  4668.2     .13       0  4992.4    .045       0  5007.7     .13       0
Bank Sta=4992.4,5007.7
XS Rating Curve= 0
Exp/Cntr=0.3,0.1

Type RM Length L Ch R = 1 ,36176.7 ,857.7,857.7,857.7
BEGIN DESCRIPTION:
Rock Creek 1 33.0
END DESCRIPTION:
XS GIS Cut Line= 3
       1862459.2       805465.29      1863031.67       805533.57
      1863341.53       805488.93
#Sta/Elev= 30
  4421.3  600.38  4471.3  598.48  4491.3  599.78  4511.3  596.86  4541.3  594.72
  4561.3  595.57  4581.3  592.22  4611.3  593.08  4631.3  590.27  4691.3  585.41
  4721.3  584.34  4751.3  579.72  4821.3  578.72  4851.3  579.19  4881.3  578.13
  4901.3  579.13  4951.3  579.36  4981.3  577.81  4991.3  574.36  4992.3  573.33
  4993.8  570.33  5006.1  570.33  5007.6  573.33  5007.8  576.95  5017.8  580.22
  5037.8  580.16  5107.8  582.66  5177.8  593.05  5207.8  596.38  5310.9  604.71
#Mann= 3 , 1 , 0
  4421.3     .13       0  4992.3    .045       0  5007.6     .13       0
Bank Sta=4992.3,5007.6
XS Rating Curve= 0
Exp/Cntr=0.3,0.1

Type RM Length L Ch R = 1 ,35319.0 ,457.5,457.5,457.5
BEGIN DESCRIPTION:
Rock Creek 1 32.0
END DESCRIPTION:
XS GIS Cut Line= 3
      1862435.57        805940.6      1862771.69       805998.37
      1863076.31       806216.33
#Sta/Elev= 30
  4655.9  599.77  4685.9  598.35  4695.9  597.42  4755.9  594.69  4785.9  594.52
  4795.9  594.09  4835.9   589.5  4855.9  587.86  4895.9  583.89  4915.9  581.14
  4925.9  580.37  4935.9  580.14  4945.9  578.69  4955.9  577.86  4975.9  577.92
  4985.9  576.16  4992.4   571.5  4993.9   568.5  5006.1   568.5  5007.6   571.5
    5017  576.17    5077  576.65    5087  576.38    5097   575.6    5107  575.64
    5117  576.22    5197  586.39    5207  587.97    5227  590.08  5371.5  598.54
#Mann= 3 , 1 , 0
  4655.9     .13       0  4992.4    .045       0  5007.6     .13       0
Bank Sta=4992.4,5007.6
XS Rating Curve= 0
Exp/Cntr=0.3,0.1

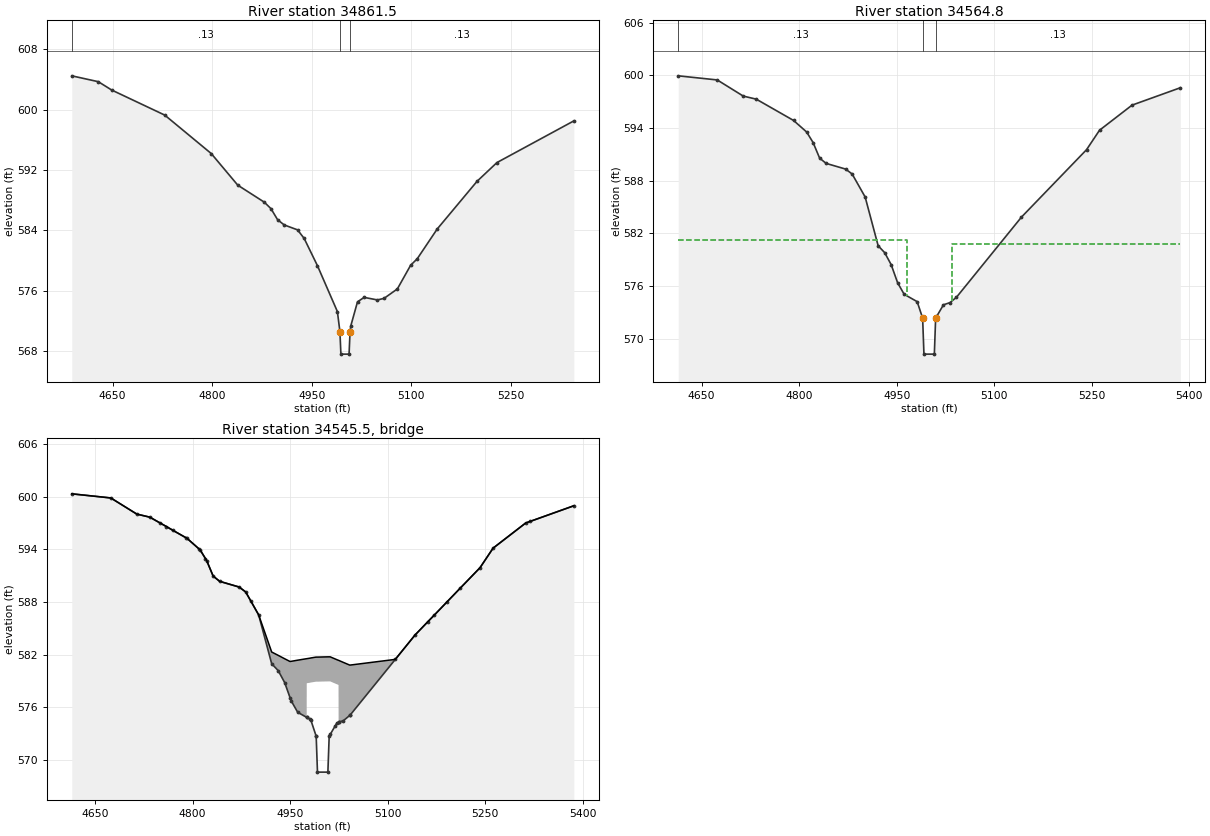
Type RM Length L Ch R = 1 ,34861.5 ,296.75,296.75,296.75
BEGIN DESCRIPTION:
Rock Creek 1 30.0
END DESCRIPTION:
XS GIS Cut Line= 3
       1862258.1       806457.65      1862668.06       806439.91
      1863005.98        806366.9
#Sta/Elev= 30
  4588.6  604.49  4628.6  603.71  4648.6  602.61  4728.6  599.28  4798.6  594.18
  4838.6  589.98  4878.6  587.72  4888.6  586.86  4898.6  585.39  4908.6   584.7
  4928.6  584.05  4938.6  582.91  4958.6  579.29  4988.6  573.21  4992.4  570.56
  4993.9  567.56  5006.2  567.56  5007.7  570.56  5008.9  571.34  5018.9   574.5
  5028.9  575.09  5048.9  574.75  5058.9  574.96  5078.9  576.21  5098.9  579.35
  5108.9  580.22  5138.9  584.16  5198.9  590.49  5228.9  592.98  5344.7  598.51
#Mann= 3 , 1 , 0
  4588.6     .13       0  4992.4    .045       0  5007.7     .13       0
Bank Sta=4992.4,5007.7
XS Rating Curve= 0
Exp/Cntr=0.5,0.3

Type RM Length L Ch R = 1 ,34564.8 ,38.5,38.5,38.5
BEGIN DESCRIPTION:
Upstream Section of Bridge/Culvert/Weir
END DESCRIPTION:
XS GIS Cut Line= 3
      1862453.58       806912.73      1862769.02       806687.79
      1863015.42       806392.52
#Sta/Elev= 30
  4614.2  599.96  4674.2  599.49  4714.2  597.65  4734.2   597.3  4791.6  594.87
  4811.6  593.56  4821.6  592.35  4831.6  590.58  4841.6  589.98  4871.6  589.33
  4881.6  588.77  4901.6  586.15  4921.6  580.59  4931.6  579.81  4941.6  578.44
  4951.6  576.36  4961.6  575.06  4981.6  574.22    4990  572.34    4992  568.24
    5008  568.24    5010  572.34    5022  573.86    5032  574.11    5042  574.72
    5142  583.86    5242  591.54    5262  593.76    5312  596.62  5386.2   598.6
#Mann= 3 , 1 , 0
  4614.2     .13       0    4990    .045       0    5010     .13       0
#XS Ineff= 2 , 0
       0  4965.4  581.21  5034.4       0   580.8
Permanent Ineff=
       F       F
Bank Sta=4990,5010
XS Rating Curve= 0
Exp/Cntr=0.5,0.3

Type RM Length L Ch R = 3 ,34545.5 ,,,
BEGIN DESCRIPTION:
Holt Crossroads-TOR
Structure ID: NCF-0090
Approximate Survey Structure
END DESCRIPTION:
Bridge Culvert--1,0,-1,-1, 0
Deck Dist Width WeirC Skew NumUp NumDn MinLoCord MaxHiCord MaxSubmerge Is_Ogee
10,18.5,2.6,0, 53, 53, , , 0.95, 0, 1,1,,
  4614.2  4674.2  4714.2  4734.2  4749.8  4759.8  4769.8  4789.8  4791.6  4809.8
  4811.6  4819.8  4821.6  4831.6  4841.6  4871.6  4881.6  4889.8  4901.6  4921.6
  4931.6  4941.6  4949.8  4951.6  4961.6 4975.41  4975.5  4980.5  4981.6  4989.8
    4990    4992    5008    5010  5011.6  5019.5    5022 5024.39  5024.5    5032
  5041.6    5042  5111.6    5142  5161.6  5171.6  5191.6  5211.6    5242    5262
    5312    5319  5386.2
  600.32  599.85  598.01  597.66  597.01  596.59  596.16  595.32  595.24  594.05
  593.93  592.94  592.72  590.95  590.35   589.7  589.14  588.07  586.52  582.29
  581.91  581.52  581.21  581.23  581.36  581.53  581.53  581.59  581.61  581.71
  581.71  581.71  581.74  581.74  581.74  581.49  581.41  581.34  581.34   581.1
   580.8   580.8  581.45  584.23  585.74   586.5  588.04  589.58  591.91  594.13
  596.99  597.18  598.96
  600.32  599.85  598.01  597.66     597  596.58  596.15  595.31  595.23  594.04
  593.92  592.93  592.71  590.94  590.34  589.69  589.13  588.06  586.51  580.95
  580.17   578.8  577.09  576.72  575.42  574.84  578.73  578.79  578.81  578.91
  578.91  578.91  578.94  578.94  578.94  578.69  578.61  578.54  574.28  574.47
  575.06  575.08  581.44  584.22  585.73  586.49  588.03  589.57   591.9  594.12
  596.98  597.17  598.96
  4614.2  4674.2  4714.2  4734.2  4749.8  4759.8  4769.8  4789.8  4791.6  4809.8
  4811.6  4819.8  4821.6  4831.6  4841.6  4871.6  4881.6  4889.8  4901.6  4921.6
  4931.6  4941.6  4949.8  4951.6  4961.6 4975.41  4975.5  4980.5  4981.6  4989.8
    4990    4992    5008    5010  5011.6  5019.5    5022 5024.39  5024.5    5032
  5041.6    5042  5111.6    5142  5161.6  5171.6  5191.6  5211.6    5242    5262
    5312    5319  5386.2
  600.32  599.85  598.01  597.66  597.01  596.59  596.16  595.32  595.24  594.05
  593.93  592.94  592.72  590.95  590.35   589.7  589.14  588.07  586.52  582.29
  581.91  581.52  581.21  581.23  581.36  581.53  581.53  581.59  581.61  581.71
  581.71  581.71  581.74  581.74  581.74  581.49  581.41  581.34  581.34   581.1
   580.8   580.8  581.45  584.23  585.74   586.5  588.04  589.58  591.91  594.13
  596.99  597.18  598.96
  600.07   599.6  597.76  597.41  596.75  596.33   595.9  595.06  594.98  593.79
  593.67  592.68  592.46  590.69  590.09  589.44  588.88  587.81  586.26   580.7
  579.92  578.55  576.84  576.47  575.17  574.59  578.48  578.54  578.56  578.66
  578.66  578.66  578.69  578.69  578.69  578.44  578.36  578.29  574.03  574.22
  574.81  574.83  581.19  583.97  585.48  586.24  587.78  589.32  591.65  593.87
  596.73  596.92  598.71
Abutment Skew #Up #Dn= , 2 , 2
  4975.3  4980.5
  578.73  574.63
  4975.3  4980.5
  578.48  574.38
Abutment Skew #Up #Dn= , 2 , 2
  5019.5 5024.59
   573.9  578.54
  5019.5 5024.59
  573.65  578.29
BR Coef= 1 , 1 , 0 ,1.25, 0 ,,,0.8,0,2,0,
WSPro=,,,, 1 ,,,, 0 ,,,, 0 ,,,,-1 ,-1 ,-1 , 0 , 0 , 0 , 0 , 0
BR U #Sta/Elev= 53
  4614.2  600.32  4674.2  599.85  4714.2  598.01  4734.2  597.66  4749.8     597
  4759.8  596.58  4769.8  596.15  4789.8  595.31  4791.6  595.23  4809.8  594.04
  4811.6  593.92  4819.8  592.93  4821.6  592.71  4831.6  590.94  4841.6  590.34
  4871.6  589.69  4881.6  589.13  4889.8  588.06  4901.6  586.51  4921.6  580.95
  4931.6  580.17  4941.6   578.8  4949.8  577.09  4951.6  576.72  4961.6  575.42
 4975.41  574.84  4975.5  574.84  4980.5  574.63  4981.6  574.58  4989.8  572.74
    4990   572.7    4992   568.6    5008   568.6    5010   572.7  5011.6   572.9
  5019.5   573.9    5022  574.22 5024.39  574.28  5024.5  574.28    5032  574.47
  5041.6  575.06    5042  575.08  5111.6  581.44    5142  584.22  5161.6  585.73
  5171.6  586.49  5191.6  588.03  5211.6  589.57    5242   591.9    5262  594.12
    5312  596.98    5319  597.17  5386.2  598.96
BR U #Mann= 3
  4614.2     .13    4990    .045    5010     .13
BR U Banks=4990,5010
BR D #Sta/Elev= 53
  4614.2  600.07  4674.2   599.6  4714.2  597.76  4734.2  597.41  4749.8  596.75
  4759.8  596.33  4769.8   595.9  4789.8  595.06  4791.6  594.98  4809.8  593.79
  4811.6  593.67  4819.8  592.68  4821.6  592.46  4831.6  590.69  4841.6  590.09
  4871.6  589.44  4881.6  588.88  4889.8  587.81  4901.6  586.26  4921.6   580.7
  4931.6  579.92  4941.6  578.55  4949.8  576.84  4951.6  576.47  4961.6  575.17
 4975.41  574.59  4975.5  574.59  4980.5  574.38  4981.6  574.33  4989.8  572.49
    4990  572.45    4992  568.35    5008  568.35    5010  572.45  5011.6  572.65
  5019.5  573.65    5022  573.97 5024.39  574.03  5024.5  574.03    5032  574.22
  5041.6  574.81    5042  574.83  5111.6  581.19    5142  583.97  5161.6  585.48
  5171.6  586.24  5191.6  587.78  5211.6  589.32    5242  591.65    5262  593.87
    5312  596.73    5319  596.92  5386.2  598.71
BR D #Mann= 3
  4614.2     .13    4990    .045    5010     .13
BR D Banks=4990,5010
BC Design=,, 0 ,, 0 ,,,,,,
BC HTab HWMax=599.96