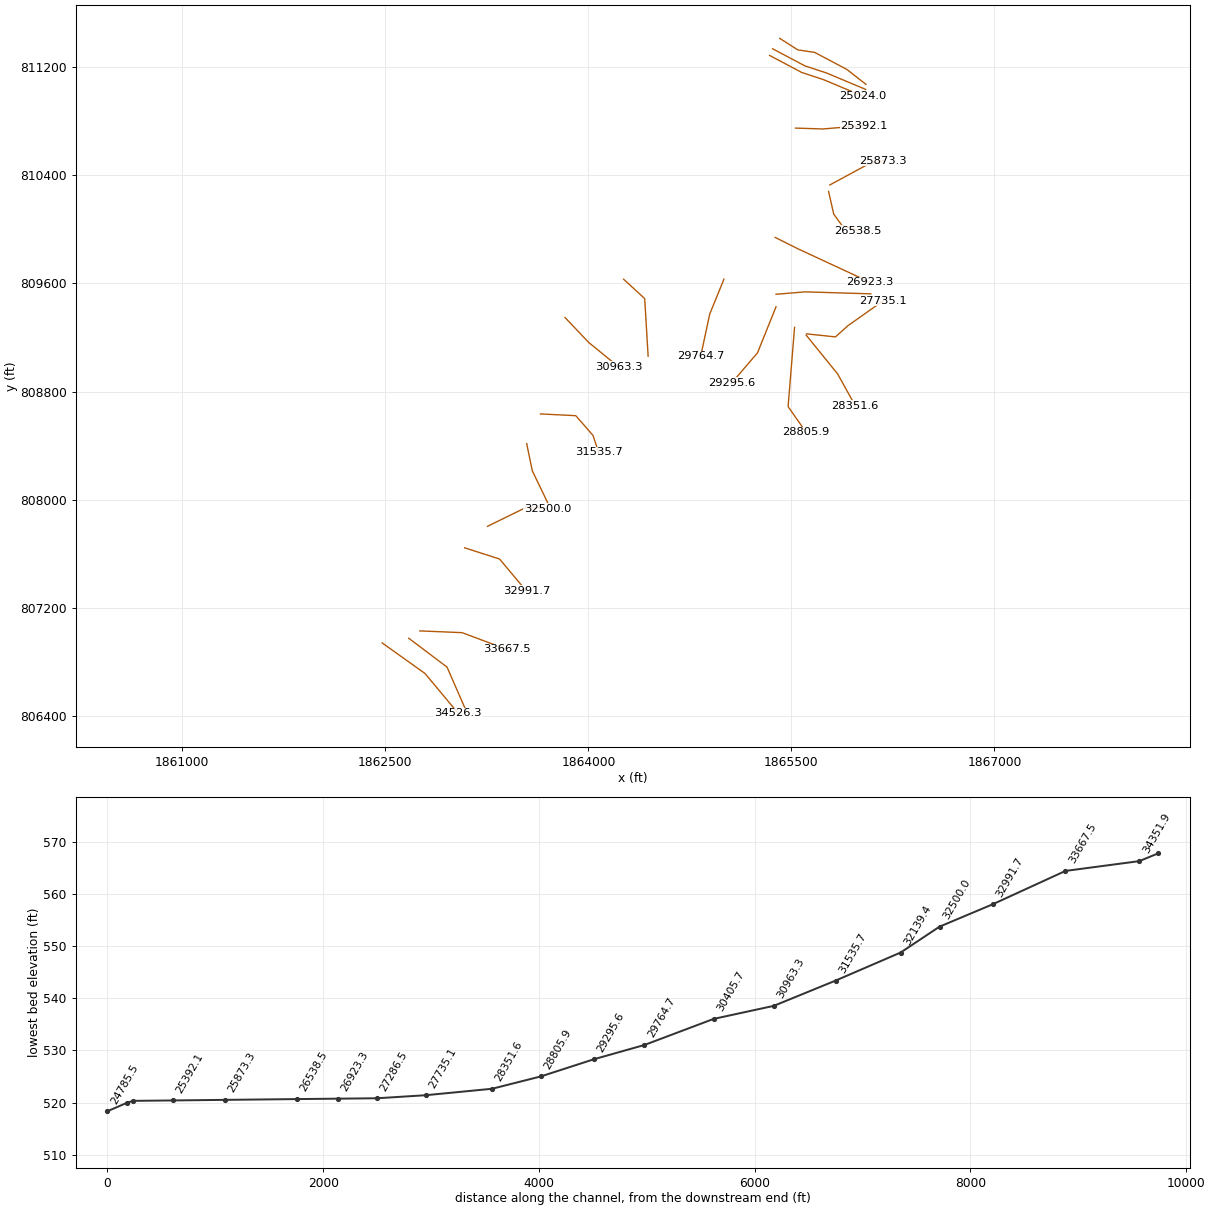
HEC-RAS study ROCK CREEK 1.PRJ: Rock Creek 1

--- ROCK CREEK 1.g01 (geometry) --- (continued)

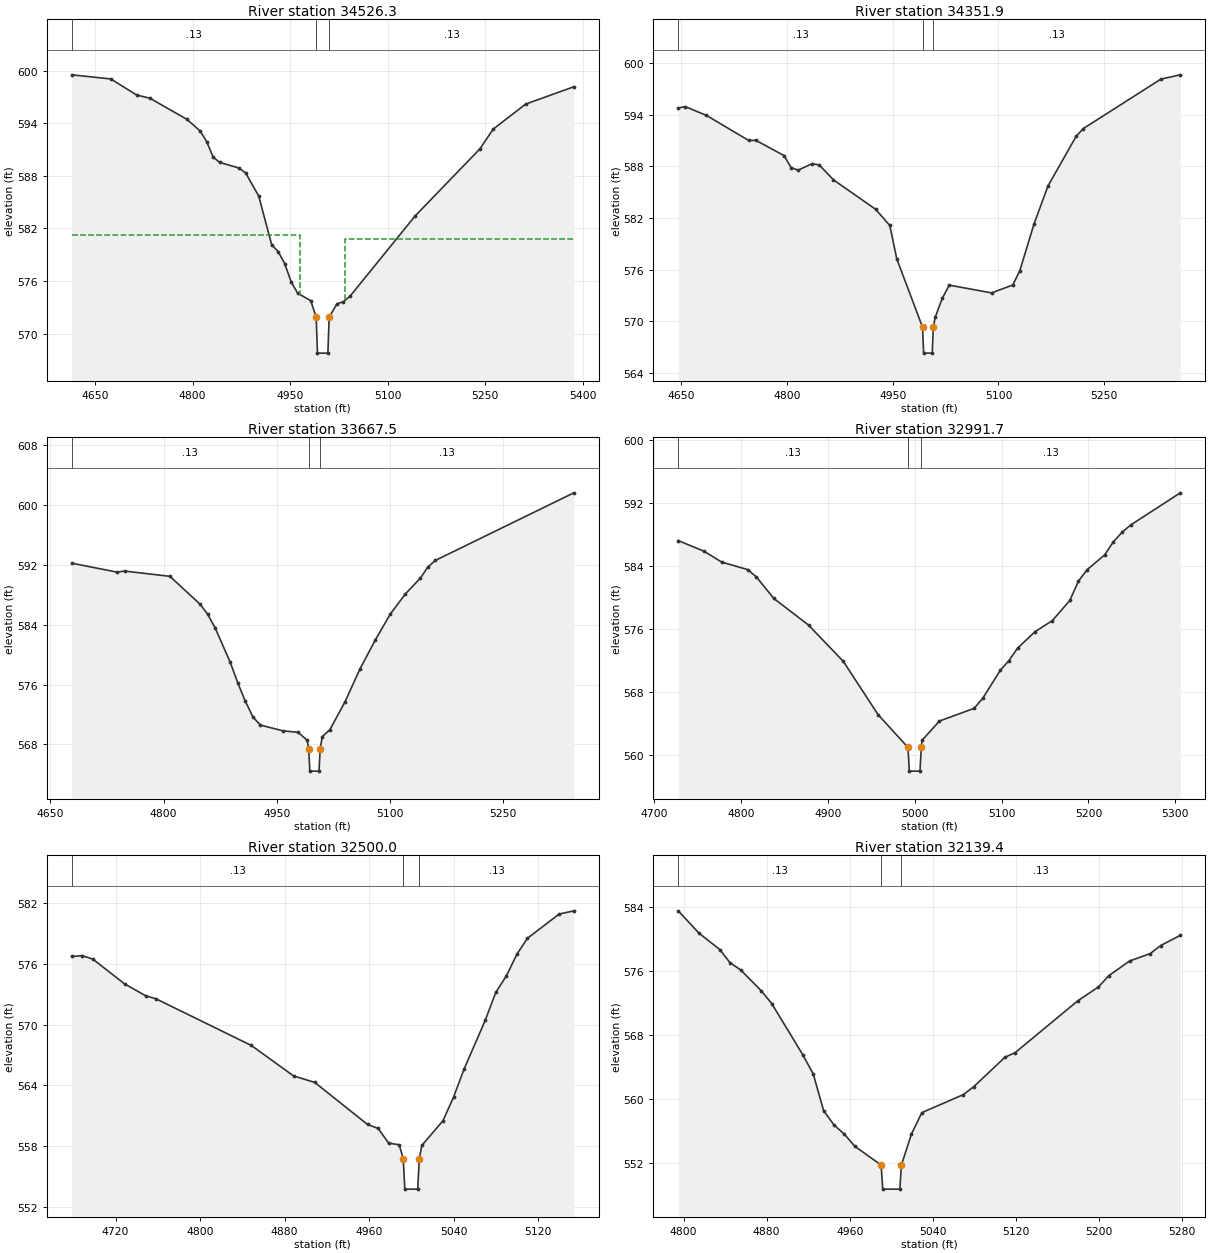
Type RM Length L Ch R = 1 ,34526.3 ,174.35,174.35,174.35
BEGIN DESCRIPTION:
Downstream Section of Bridge/Culvert/Weir
END DESCRIPTION:
XS GIS Cut Line= 3
      1862477.11        806943.2      1862792.54       806718.27
      1863038.95         806423.
#Sta/Elev= 30
  4614.2  599.51  4674.2  599.04  4714.2   597.2  4734.2  596.85  4791.6  594.42
  4811.6  593.11  4821.6   591.9  4831.6  590.13  4841.6  589.53  4871.6  588.88
  4881.6  588.32  4901.6   585.7  4921.6  580.14  4931.6  579.36  4941.6  577.99
  4951.6  575.91  4961.6  574.61  4981.6  573.77    4990  571.89    4992  567.79
    5008  567.79    5010  571.89    5022  573.41    5032  573.66    5042  574.27
    5142  583.41    5242  591.09    5262  593.31    5312  596.17  5386.2  598.15
#Mann= 3 , 1 , 0
  4614.2     .13       0    4990    .045       0    5010     .13       0
#XS Ineff= 2 , 0
       0  4965.4  581.21  5034.4       0   580.8
Permanent Ineff=
       F       F
Bank Sta=4990,5010
XS Rating Curve= 0
Exp/Cntr=0.5,0.3

Type RM Length L Ch R = 1 ,34351.9 ,684.4,684.4,684.4
BEGIN DESCRIPTION:
Rock Creek 1 27.0
END DESCRIPTION:
XS GIS Cut Line= 3
      1862672.62       806978.28      1862955.76       806765.13
      1863098.92       806437.45
#Sta/Elev= 30
  4645.9  594.76  4655.9  594.92  4685.9   593.9  4745.9  590.99  4755.9  591.01
  4795.9  589.24  4805.9  587.85  4815.9  587.55  4835.9   588.3  4845.9  588.15
  4865.9  586.43  4925.9     583  4945.9  581.13  4955.9  577.23  4992.4  569.31
  4993.9  566.31  5006.1  566.31  5007.6  569.31  5010.3  570.46  5020.3  572.67
  5030.3   574.2  5090.3   573.3  5120.3  574.22  5130.3  575.87  5150.3  581.27
  5170.3  585.72  5210.3  591.49  5220.3  592.37  5330.3  598.11  5357.9  598.61
#Mann= 3 , 1 , 0
  4645.9     .13       0  4992.4    .045       0  5007.6     .13       0
Bank Sta=4992.4,5007.6
XS Rating Curve= 0
Exp/Cntr=0.3,0.1

Type RM Length L Ch R = 1 ,33667.5 ,675.8,675.8,675.8
BEGIN DESCRIPTION:
Rock Creek 1 26.0
END DESCRIPTION:
XS GIS Cut Line= 3
      1862755.33       807032.36      1863067.11       807019.64
      1863397.97       806895.57
#Sta/Elev= 30
  4678.4   592.2  4738.4  591.01  4748.4  591.15  4808.4  590.45  4848.4  586.73
  4858.4   585.4  4868.4  583.56  4888.4  578.97  4898.4  576.22  4908.4  573.77
  4918.4  571.68  4928.4  570.58  4958.4  569.81  4978.4  569.61  4990.4  568.55
  4992.4  567.43  4993.9  564.43  5006.1  564.43  5007.6  567.43  5010.4  569.04
  5020.4  569.95  5040.4  573.66  5060.4  578.08  5080.4   581.9  5100.4  585.38
  5120.4  588.08  5140.4  590.21  5150.4   591.7  5160.4  592.58  5343.8   601.6
#Mann= 3 , 1 , 0
  4678.4     .13       0  4992.4    .045       0  5007.6     .13       0
Bank Sta=4992.4,5007.6
XS Rating Curve= 0
Exp/Cntr=0.3,0.1

Type RM Length L Ch R = 1 ,32991.7 ,491.7,491.7,491.7
BEGIN DESCRIPTION:
Rock Creek 1 25.0
END DESCRIPTION:
XS GIS Cut Line= 3
       1863086.2       807646.37      1863343.89       807563.66
      1863541.13       807328.23
#Sta/Elev= 30
  4727.9   587.2  4757.9  585.84  4777.9  584.48  4807.9  583.53  4817.9  582.59
  4837.9  579.88  4877.9   576.5  4917.9  571.91  4957.9  565.17  4992.3  561.02
  4993.8  558.02  5006.1  558.02  5007.6  561.02  5008.5  561.93  5028.5  564.36
  5068.5  565.97  5078.5  567.27  5098.5  570.78  5108.5  572.02  5118.5   573.6
  5138.5  575.67  5158.5  577.08  5178.5  579.62  5188.5  582.08  5198.5  583.52
  5218.5  585.38  5228.5  587.02  5238.5  588.24  5248.5  589.17  5305.7  593.25
#Mann= 3 , 1 , 0
  4727.9     .13       0  4992.3    .045       0  5007.6     .13       0
Bank Sta=4992.3,5007.6
XS Rating Curve= 0
Exp/Cntr=0.3,0.1

Type RM Length L Ch R = 1 ,32500.0 ,360.6,360.6,360.6
BEGIN DESCRIPTION:
Rock Creek 1 23.0
END DESCRIPTION:
XS GIS Cut Line= 3
      1863254.81       807805.44      1863543.52       807946.66
      1863697.02       807935.88
#Sta/Elev= 28
  4678.6  576.74  4688.6  576.82  4698.6  576.47  4728.6  574.03  4748.6  572.85
  4758.6  572.54  4848.6  567.94  4888.6  564.93  4908.6  564.29  4958.6  560.13
  4968.6  559.74  4978.6  558.29  4988.6  558.12  4992.4  556.74  4993.9  553.74
  5006.1  553.74  5007.6  556.74    5010  558.06    5030   560.5    5040  562.83
    5050  565.61    5070  570.42    5080  573.19    5090  574.81    5100  576.96
    5110  578.54    5140  580.93  5153.9  581.25
#Mann= 3 , 1 , 0
  4678.6     .13       0  4992.4    .045       0  5007.6     .13       0
Bank Sta=4992.4,5007.6
XS Rating Curve= 0
Exp/Cntr=0.3,0.1

Type RM Length L Ch R = 1 ,32139.4 ,603.7,603.7,603.7
BEGIN DESCRIPTION:
Rock Creek 1 22.0
END DESCRIPTION:
XS GIS Cut Line= 3
      1863544.31       808416.27      1863585.67       808215.84
      1863706.57       807964.51
#Sta/Elev= 30
  4794.9  583.52  4814.9  580.73  4834.9  578.69  4844.9  577.02  4854.9  576.16
  4874.9  573.53  4884.9  571.95  4914.9  565.54  4924.9  563.15  4934.9  558.58
  4944.9  556.79  4954.9  555.64  4964.9  554.13  4990.3  551.78  4991.8  548.78
  5008.3  548.78  5009.8  551.78  5019.5  555.66  5029.5  558.33  5069.5  560.58
  5079.5  561.57  5109.5  565.24  5119.5  565.83  5179.5  572.27  5199.5  574.01
  5209.5  575.42  5229.5  577.25  5249.5  578.19  5259.5  579.19  5278.4  580.46
#Mann= 3 , 1 , 0
  4794.9     .13       0  4990.3    .045       0  5009.8     .13       0
Bank Sta=4990.3,5009.8
XS Rating Curve= 0
Exp/Cntr=0.3,0.1

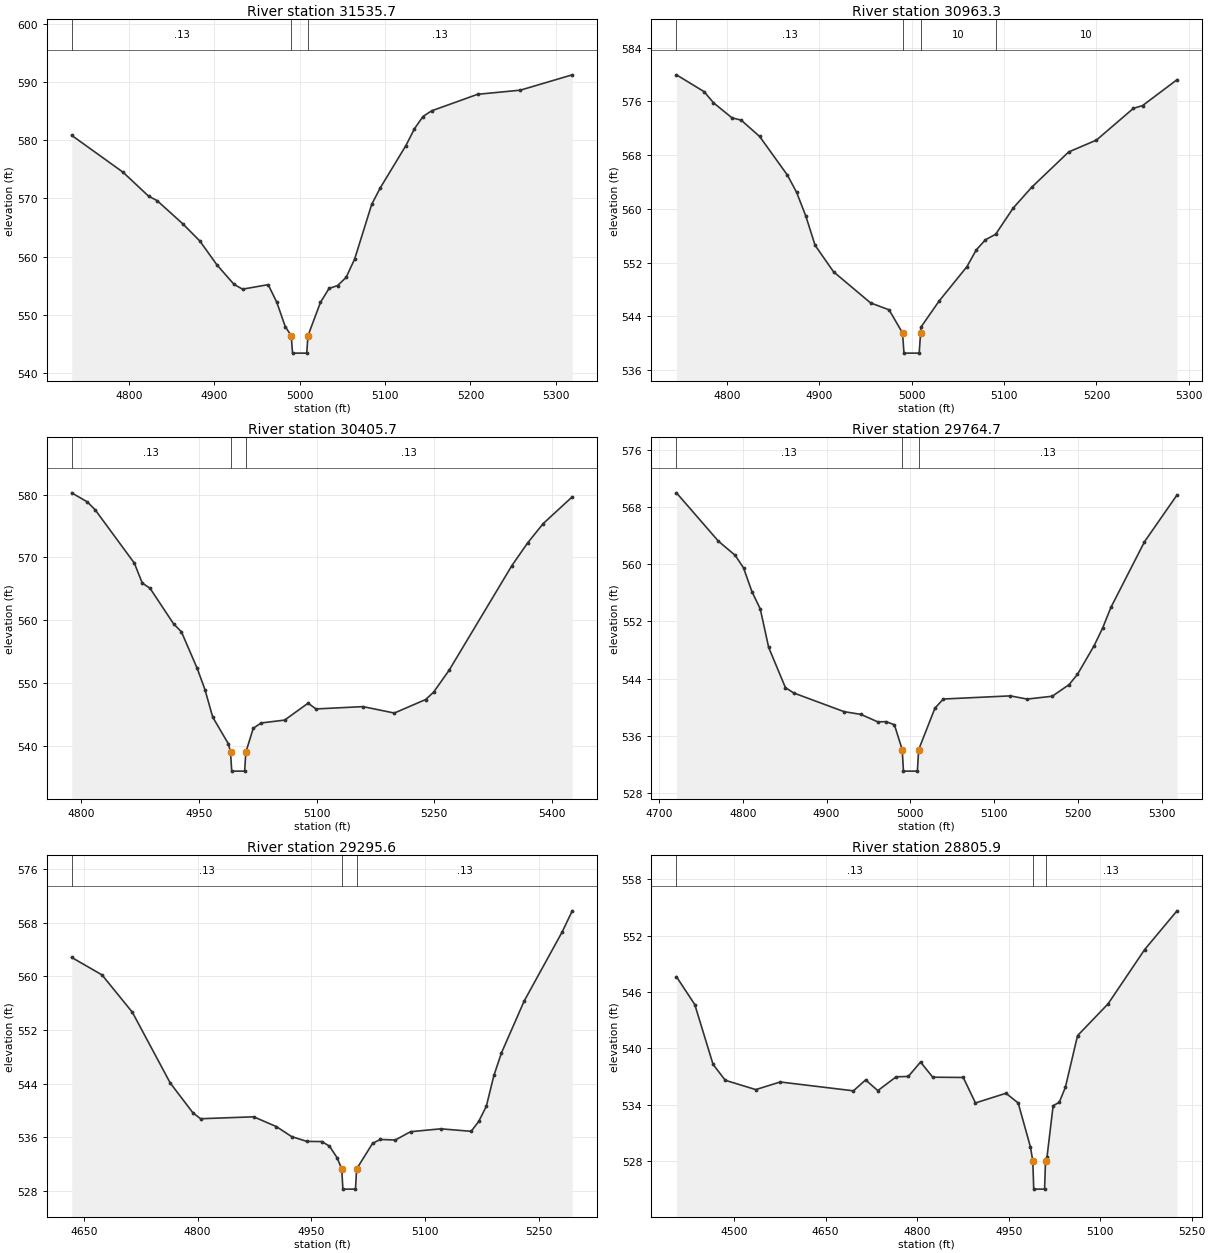
Type RM Length L Ch R = 1 ,31535.7 ,572.4,572.4,572.4
BEGIN DESCRIPTION:
Rock Creek 1 21.0
END DESCRIPTION:
XS GIS Cut Line= 4
      1863646.12       808635.78      1863906.99       808623.06
      1864034.25       808476.71      1864075.61       808352.64
#Sta/Elev= 30
  4733.2  580.85  4793.2  574.52  4823.2  570.39  4833.2  569.62  4863.2  565.64
  4883.2  562.68  4903.2  558.57  4923.2  555.22  4933.2  554.39  4963.2  555.17
  4973.2  552.16  4983.2  547.95  4990.2  546.39  4991.7  543.39  5008.3  543.39
  5009.8  546.39  5024.4  552.12  5034.4  554.51  5044.4  555.01  5054.4  556.41
  5064.4  559.57  5084.4  568.99  5094.4  571.82  5124.4  579.09  5134.4  581.98
  5144.4  584.09  5154.4  585.06  5208.3  587.91  5258.3  588.62  5319.1  591.26
#Mann= 3 , 1 , 0
  4733.2     .13       0  4990.2    .045       0  5009.8     .13       0
Bank Sta=4990.2,5009.8
XS Rating Curve= 0
Exp/Cntr=0.3,0.1

Type RM Length L Ch R = 1 ,30963.3 ,557.6,557.6,557.6
BEGIN DESCRIPTION:
Rock Creek 1 20.0
END DESCRIPTION:
XS GIS Cut Line= 3
      1863827.46       809348.41      1864002.43       809163.89
      1864225.13       808982.55
#Sta/Elev= 30
  4745.6  579.94  4775.6  577.43  4785.6  575.79  4805.6  573.55  4815.6   573.2
  4835.6  570.77  4865.6  565.03  4875.6  562.46  4885.6  558.91  4895.6  554.58
  4915.6  550.64  4955.6  546.02  4975.6  544.99  4990.2  541.55  4991.7  538.55
  5008.2  538.55  5009.7  541.55  5009.9  542.38  5029.9  546.33  5059.9  551.42
  5069.9   553.9  5079.9  555.41  5090.9  556.23  5109.9  560.13  5129.9  563.22
  5169.9  568.47  5199.9  570.23  5239.9  574.95  5249.9  575.37  5287.1  579.21
#Mann= 4 , 1 , 0
  4745.6     .13       0  4990.2    .045       0  5009.7      10       0
  5090.9      10       0
Bank Sta=4990.2,5009.7
XS Rating Curve= 0
Exp/Cntr=0.3,0.1

Type RM Length L Ch R = 1 ,30405.7 ,641,641,641
BEGIN DESCRIPTION:
Rock Creek 1 19.0
END DESCRIPTION:
XS GIS Cut Line= 3
      1864260.13       809631.56      1864416.01       809488.39
      1864441.46       809062.09
#Sta/Elev= 30
  4787.5  580.27  4807.5  578.82  4817.5  577.57  4867.5  569.09  4877.5  565.94
  4887.5   565.1  4917.5  559.46  4927.5  558.19  4947.5  552.42  4957.5  549.02
  4967.5  544.62  4987.5  540.38  4990.2  539.05  4991.7  536.05  5008.2  536.05
  5009.7  539.05  5019.2  542.86  5029.2   543.7  5059.2  544.16  5089.2  546.85
  5099.2  545.93  5159.2   546.3  5199.2  545.28  5239.2  547.43  5249.2  548.58
  5269.2   552.1  5349.2  568.71  5369.2   572.3  5389.2  575.39  5426.2  579.63
#Mann= 3 , 1 , 0
  4787.5     .13       0  4990.2    .045       0  5009.7     .13       0
Bank Sta=4990.2,5009.7
XS Rating Curve= 0
Exp/Cntr=0.3,0.1

Type RM Length L Ch R = 1 ,29764.7 ,469.1,469.1,469.1
BEGIN DESCRIPTION:
Rock Creek 1 17.0
END DESCRIPTION:
XS GIS Cut Line= 3
      1865001.39       809631.56       1864896.4       809373.86
      1864829.59       809062.09
#Sta/Elev= 30
  4720.9  569.99  4770.9  563.23  4790.9  561.25  4800.9  559.49  4810.9  556.18
  4820.9  553.73  4830.9  548.36  4850.9  542.73  4860.9  541.98  4920.9  539.37
  4940.9  538.99  4960.9  537.95  4970.9  537.97  4980.9  537.54  4990.2  534.05
  4991.7  531.05  5008.3  531.05  5009.8  534.05  5029.2  539.85  5039.2  541.14
  5119.2  541.58  5139.2  541.13  5169.2  541.53  5189.2  543.15  5199.2  544.58
  5219.2  548.62  5229.2  551.05  5239.2  553.97  5279.2  563.14    5318  569.69
#Mann= 3 , 1 , 0
  4720.9     .13       0  4990.2    .045       0  5009.8     .13       0
Bank Sta=4990.2,5009.8
XS Rating Curve= 0
Exp/Cntr=0.3,0.1

Type RM Length L Ch R = 1 ,29295.6 ,489.7,489.7,489.7
BEGIN DESCRIPTION:
Rock Creek 1 16.0
END DESCRIPTION:
XS GIS Cut Line= 3
      1865386.34       809427.95      1865249.54       809087.54
      1865058.65       808864.84
#Sta/Elev= 30
    4634  562.81    4674  560.21    4714  554.65    4764  544.11    4794  539.66
    4804  538.79    4874  539.08    4904  537.62    4924  536.14    4944  535.42
    4964  535.39    4974  534.71    4984     533  4990.2  531.31  4991.7  528.31
  5008.3  528.31  5009.8  531.31  5030.9  535.13  5040.9   535.7  5060.9  535.63
  5080.9  536.86  5120.9  537.29  5160.9  536.92  5170.9   538.4  5180.9  540.65
  5190.9  545.24  5200.9  548.61  5230.9  556.34  5280.9   566.6  5294.2  569.75
#Mann= 3 , 1 , 0
    4634     .13       0  4990.2    .045       0  5009.8     .13       0
Bank Sta=4990.2,5009.8
XS Rating Curve= 0
Exp/Cntr=0.3,0.1

Type RM Length L Ch R = 1 ,28805.9 ,454.3,454.3,454.3
BEGIN DESCRIPTION:
Rock Creek 1 15.0
END DESCRIPTION:
XS GIS Cut Line= 3
      1865523.14       809275.24      1865475.41       808689.87
      1865609.03       808498.98
#Sta/Elev= 30
  4405.6  547.63  4435.6  544.67  4465.6   538.3  4485.6  536.61  4535.6  535.62
  4575.6  536.43  4695.6  535.49  4715.6  536.65  4735.6  535.51  4765.6  536.98
  4785.6  537.02  4805.6  538.55  4825.6  536.94  4875.6  536.91  4895.6   534.2
  4945.6  535.23  4965.6   534.2  4985.6  529.54  4989.6  528.03  4991.1  525.03
  5008.9  525.03  5010.4  528.03  5012.9  528.46  5022.9  533.91  5032.9  534.26
  5042.9  535.85  5062.9  541.36  5112.9  544.74  5172.9  550.52  5225.9  554.64
#Mann= 3 , 1 , 0
  4405.6     .13       0  4989.6    .045       0  5010.4     .13       0
Bank Sta=4989.6,5010.4
XS Rating Curve= 0
Exp/Cntr=0.3,0.1

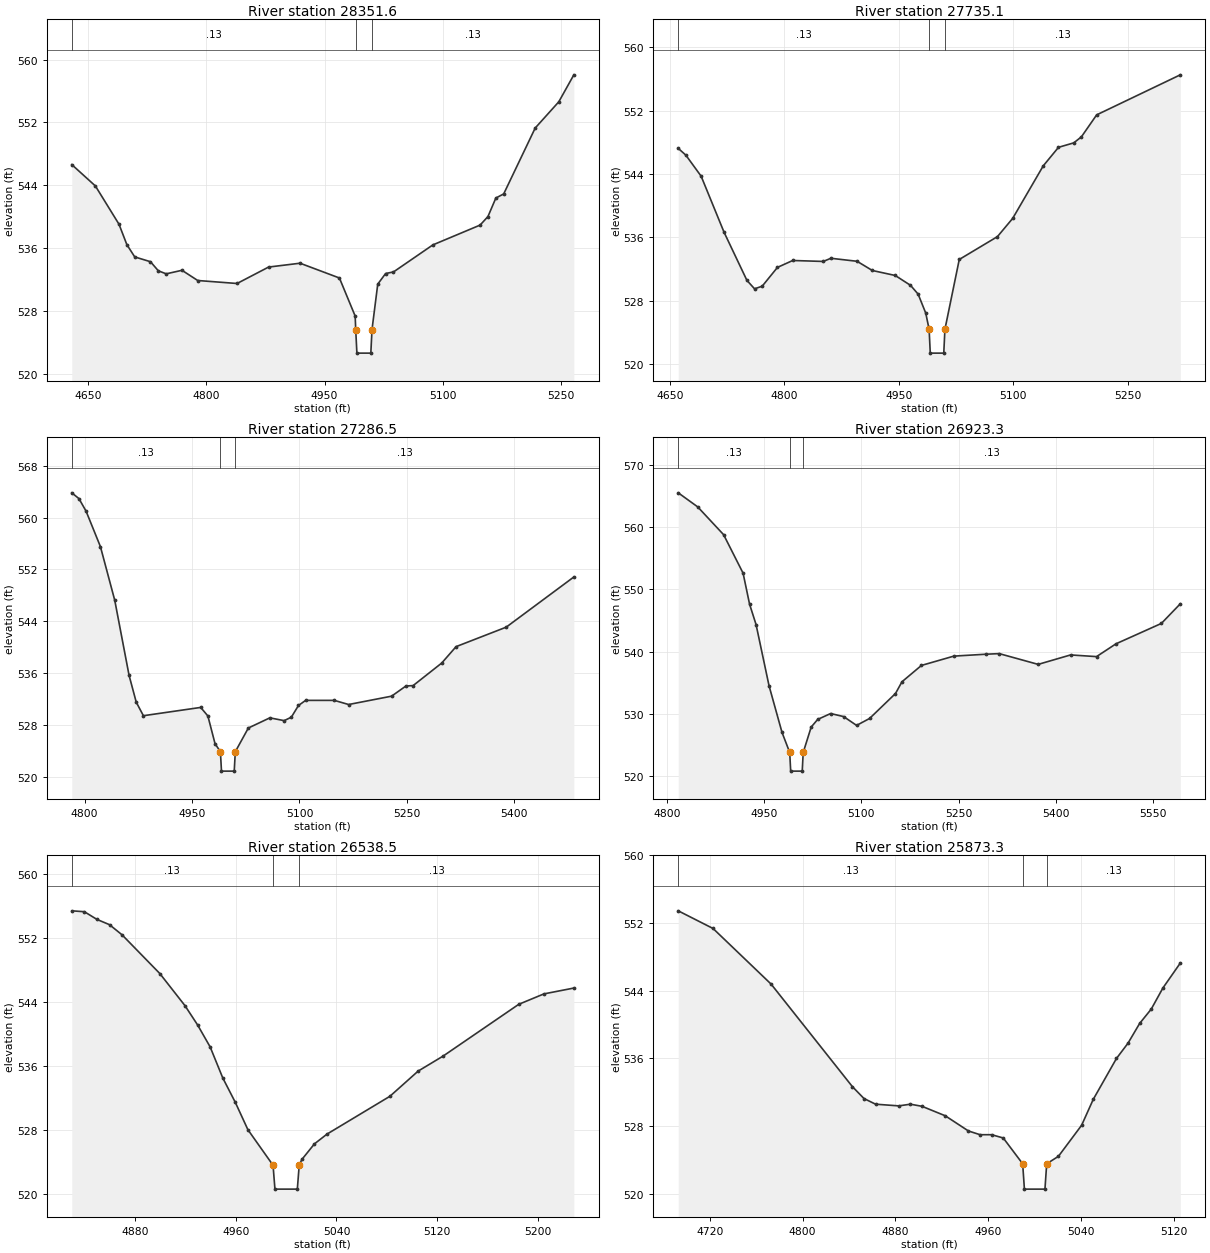
Type RM Length L Ch R = 1 ,28351.6 ,616.5,616.5,616.5
BEGIN DESCRIPTION:
Rock Creek 1 13.0
END DESCRIPTION:
XS GIS Cut Line= 3
      1865609.03       809217.98      1865841.27       808931.65
      1865971.71       808696.23
#Sta/Elev= 30
  4628.9  546.64  4658.9  543.92  4688.9  539.05  4698.9  536.45  4708.9  534.89
  4728.9  534.28  4738.9  533.12  4748.9  532.74  4768.9  533.19  4788.9  531.89
  4838.9  531.51  4878.9   533.6  4918.9  534.09  4968.9  532.21  4988.9  527.37
  4989.6  525.65  4991.1  522.65  5008.8  522.65  5010.3  525.65  5017.6  531.43
  5027.6  532.78  5037.6  532.98  5087.6  536.42  5147.6  538.94  5157.6  540.03
  5167.6  542.38  5177.6  542.91  5217.6  551.29  5247.6  554.63  5266.7  558.06
#Mann= 3 , 1 , 0
  4628.9     .13       0  4989.6    .045       0  5010.3     .13       0
Bank Sta=4989.6,5010.3
XS Rating Curve= 0
Exp/Cntr=0.3,0.1

Type RM Length L Ch R = 1 ,27735.1 ,448.6,448.6,448.6
BEGIN DESCRIPTION:
Rock Creek 1 10.0
END DESCRIPTION:
XS GIS Cut Line= 4
      1865612.21       809227.52      1865825.37       809205.25
      1865917.63       809287.97       1866178.5       809472.49
#Sta/Elev= 30
  4660.9  547.23  4670.9  546.37  4690.9  543.72  4720.9  536.66  4750.9  530.58
  4760.9  529.52  4770.9  529.85  4790.9  532.22  4810.9  533.09  4850.9  532.97
  4860.9  533.37  4895.2  532.99  4915.2  531.83  4945.2   531.2  4965.2  529.96
  4975.2  528.85  4985.2  526.45  4989.6  524.41  4991.1  521.41  5008.8  521.41
  5010.3  524.41  5029.1  533.22  5079.1   536.1  5099.1   538.4  5139.1  545.02
  5159.1  547.36  5179.1  547.92  5189.1  548.68  5209.1  551.45  5318.7   556.5
#Mann= 3 , 1 , 0
  4660.9     .13       0  4989.6    .045       0  5010.3     .13       0
Bank Sta=4989.6,5010.3
XS Rating Curve= 0
Exp/Cntr=0.3,0.1

Type RM Length L Ch R = 1 ,27286.5 ,363.2,363.2,363.2
BEGIN DESCRIPTION:
Rock Creek 1 9.0
END DESCRIPTION:
XS GIS Cut Line= 3
      1865386.34       809520.21      1865602.15       809538.02
      1866086.24       809523.39
#Sta/Elev= 30
  4782.1  563.82  4792.1  562.93  4802.1  560.98  4822.1  555.51  4842.1  547.22
  4862.1  535.62  4872.1  531.48  4882.1  529.39  4962.1  530.67  4972.1  529.35
  4982.1  525.07  4989.6  523.83  4991.1  520.83  5008.9  520.83  5010.4  523.83
  5028.6  527.49  5058.6  529.06  5078.6  528.63  5088.6  529.16  5098.6  530.97
  5108.6  531.76  5148.6  531.76  5168.6  531.12  5228.6  532.41  5248.6  533.98
  5258.6  534.04  5298.6  537.53  5318.6  540.06  5388.6  543.07    5483  550.82
#Mann= 3 , 1 , 0
  4782.1     .13       0  4989.6    .045       0  5010.4     .13       0
Bank Sta=4989.6,5010.4
XS Rating Curve= 0
Exp/Cntr=0.3,0.1

Type RM Length L Ch R = 1 ,26923.3 ,384.8,384.8,384.8
BEGIN DESCRIPTION:
Rock Creek 1 7.0
END DESCRIPTION:
XS GIS Cut Line= 3
      1865379.97       809940.13      1865545.41       809857.43
      1866079.88       809609.29
#Sta/Elev= 30
  4817.7  565.54  4847.7  563.28  4887.7   558.8  4917.7  552.61  4927.7  547.62
  4937.7  544.34  4957.7   534.5  4977.7  526.99  4989.6  523.75  4991.1  520.75
  5008.9  520.75  5010.4  523.75  5022.7  527.84  5032.7  529.07  5052.7  530.02
  5072.7  529.53  5092.7  528.11  5112.7  529.22  5152.7  533.24  5162.7  535.13
  5192.7  537.76  5242.7  539.26  5292.7  539.57  5312.7  539.66  5372.7  537.93
  5422.7  539.45  5462.7  539.18  5492.7  541.24  5562.7  544.52  5591.9  547.68
#Mann= 3 , 1 , 0
  4817.7     .13       0  4989.6    .045       0  5010.4     .13       0
Bank Sta=4989.6,5010.4
XS Rating Curve= 0
Exp/Cntr=0.3,0.1

Type RM Length L Ch R = 1 ,26538.5 ,665.2,665.2,665.2
BEGIN DESCRIPTION:
Rock Creek 1 5.0
END DESCRIPTION:
XS GIS Cut Line= 4
      1865774.46       810280.56      1865812.64       810111.95
      1865873.09       810029.23       1865990.8       809991.05
#Sta/Elev= 26
  4829.6  555.41  4839.6   555.3  4849.6  554.34  4859.6  553.68  4869.6  552.41
  4899.6  547.58  4919.6  543.57  4929.6  541.17  4939.6  538.42  4949.6  534.56
  4959.6   531.5  4969.6  528.09  4989.5  523.67  4989.6  523.65  4991.1  520.67
  5008.9  520.67  5010.4  523.67  5012.5  524.37  5022.5  526.32  5032.5  527.54
  5082.5  532.26  5104.9   535.4  5124.9  537.29  5184.9  543.74  5204.9  545.04
  5228.7  545.77
#Mann= 3 , 1 , 0
  4829.6     .13       0  4989.5    .045       0  5010.4     .13       0
Bank Sta=4989.5,5010.4
XS Rating Curve= 0
Exp/Cntr=0.3,0.1

Type RM Length L Ch R = 1 ,25873.3 ,481.2,481.2,481.2
BEGIN DESCRIPTION:
Rock Creek 1 3.0
END DESCRIPTION:
XS GIS Cut Line= 3
      1865784.01       810328.28      1866054.43       810474.62
      1866175.32       810506.44
#Sta/Elev= 27
  4692.9  553.45  4722.9  551.36  4772.9  544.78  4842.9  532.65  4852.9  531.24
  4862.9  530.57  4882.9  530.37  4892.9  530.57  4902.9  530.32  4922.9   529.2
  4942.9   527.4  4952.9  526.96  4962.9  526.96  4972.9  526.57  4989.6  523.52
  4991.1  520.52  5008.8  520.52  5010.3  523.52  5020.4   524.4  5040.4  528.08
  5050.4  531.14  5070.4  535.98  5080.4   537.8  5090.4  540.13  5100.4  541.83
  5110.4  544.32  5125.4  547.27
#Mann= 3 , 1 , 0
  4692.9     .13       0  4989.6    .045       0  5010.3     .13       0
Bank Sta=4989.6,5010.3
XS Rating Curve= 0
Exp/Cntr=0.3,0.1

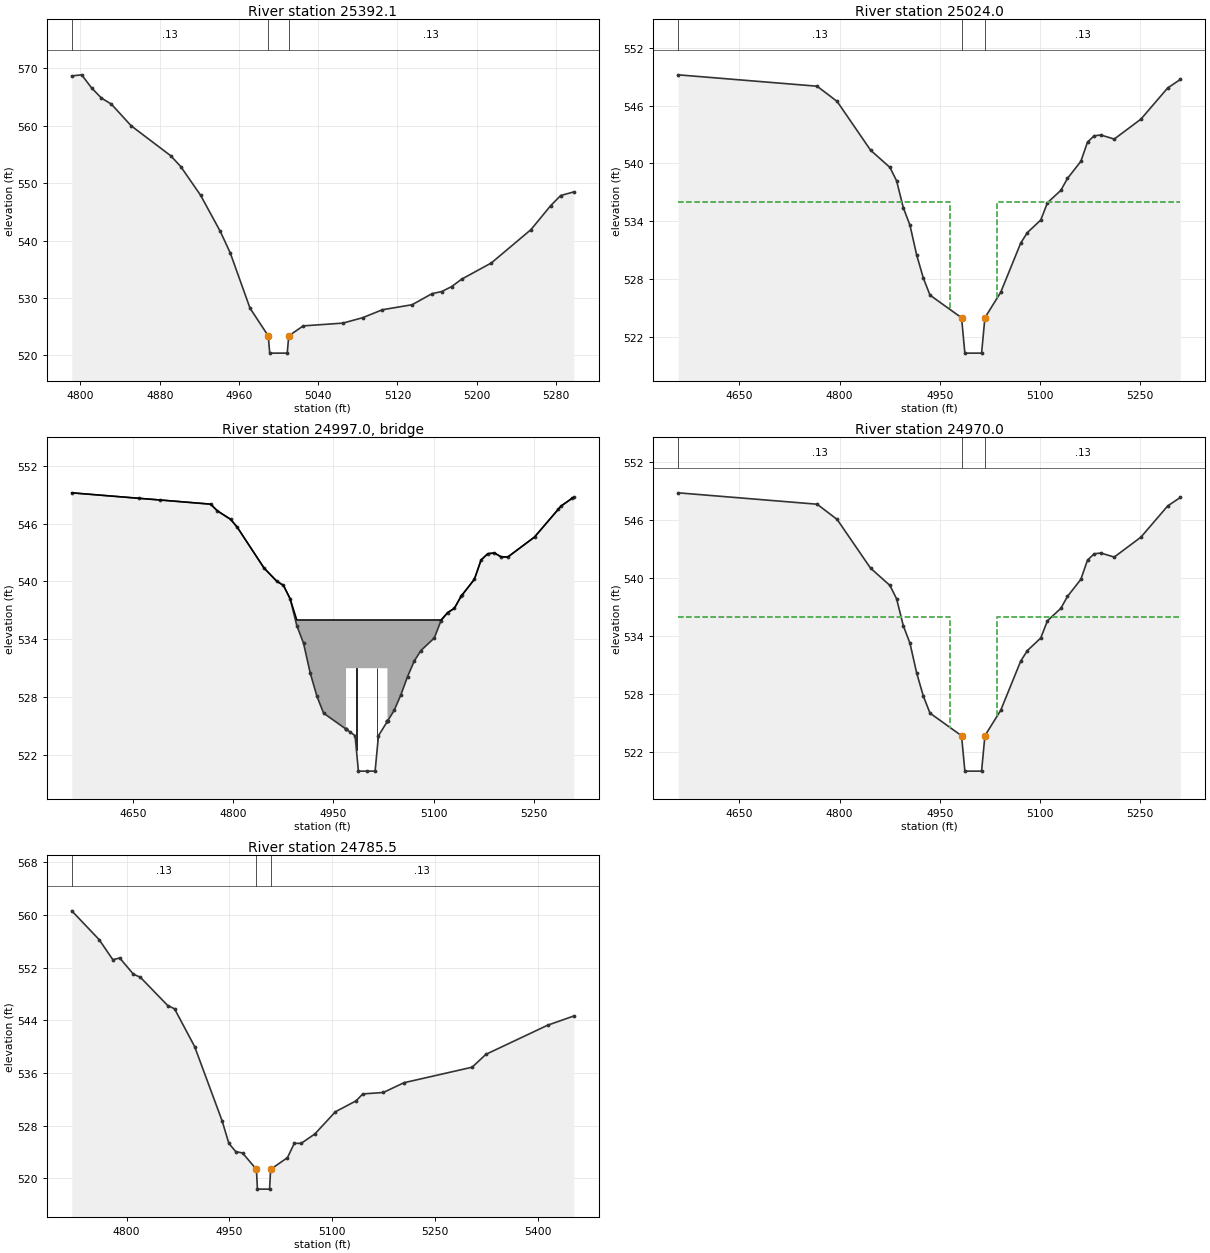
Type RM Length L Ch R = 1 ,25392.1 ,368.1,368.1,368.1
BEGIN DESCRIPTION:
Rock Creek 1 2.0
END DESCRIPTION:
XS GIS Cut Line= 3
       1865529.5       810748.22      1865733.11       810741.86
      1866035.34       810767.31
#Sta/Elev= 30
  4791.2  568.64  4801.2  568.83  4811.2  566.56  4821.2  564.78  4831.2  563.73
  4851.2  559.96  4891.2  554.74  4901.2  552.88  4921.2   547.9  4941.2  541.58
  4951.2  537.86  4971.2  528.23  4989.6  523.41  4991.1  520.41  5008.8  520.41
  5010.3  523.41  5024.9  525.15  5064.9  525.63  5084.9  526.57  5104.9  527.96
  5134.9  528.83  5154.9  530.75  5164.9  531.13  5174.9     532  5184.9  533.28
  5214.9   536.1  5254.9   541.9  5274.9  546.09  5284.9  547.83  5298.2  548.46
#Mann= 3 , 1 , 0
  4791.2     .13       0  4989.6    .045       0  5010.3     .13       0
Bank Sta=4989.6,5010.3
XS Rating Curve= 0
Exp/Cntr=0.5,0.3

Type RM Length L Ch R = 1 ,25024.0 ,54,54,54
BEGIN DESCRIPTION:
Upstream Section of Bridge/Culvert/Weir
END DESCRIPTION:
XS GIS Cut Line= 4
      1865339.05       811285.06      1865577.28       811158.82
      1865738.13       811105.88       1866026.4       810984.85
#Sta/Elev= 30
  4558.4  549.18  4766.3     548  4796.3  546.42  4846.3  541.37  4875.3  539.58
  4885.3  538.19  4895.3  535.41  4905.3  533.59  4915.3  530.51  4925.3  528.11
  4935.3  526.34  4982.5     524  4987.5  520.33  5012.5  520.33  5017.5     524
  5041.1  526.63  5071.1  531.74  5081.1  532.83  5101.1  534.13  5111.1  535.92
  5131.1   537.2  5141.1  538.44  5161.1  540.21  5171.1  542.21  5181.1  542.86
  5191.1  542.94  5211.1  542.52  5251.1  544.59  5291.1  547.82    5310   548.7
#Mann= 3 , 1 , 0
  4558.4     .13       0  4982.5    .045       0  5017.5     .13       0
#XS Ineff= 2 , 0
       0  4965.9     536  5035.8       0     536
Permanent Ineff=
       F       F
Bank Sta=4982.5,5017.5
XS Rating Curve= 0
Exp/Cntr=0.5,0.3

Type RM Length L Ch R = 3 ,24997.0 ,,,
BEGIN DESCRIPTION:
Friendship Patterson Mill Rd - TOR
Structure ID: Friendship Patterson Mill Rd
Approximate Survey Structure
END DESCRIPTION:
Bridge Culvert--1,0,-1,-1, 0
Deck Dist Width WeirC Skew NumUp NumDn MinLoCord MaxHiCord MaxSubmerge Is_Ogee
10,34,2.6,0, 51, 51, , , 0.95, 0, 1,1,,
  4558.4  4658.4  4690.9  4766.3  4776.3  4796.3  4806.3  4846.3  4865.3  4875.3
  4885.3  4895.3  4905.3  4915.3  4925.3  4935.3 4968.91    4969  4969.1  4975.3
  4982.5  4987.5    5000  5012.5  5017.5  5030.8 5030.89    5031  5031.1  5041.1
  5051.1  5061.1  5071.1  5081.1  5101.1  5111.1  5121.1  5131.1  5141.1    5143
  5161.1  5171.1  5181.1  5191.1  5201.1  5211.1  5251.1  5286.6  5291.1  5307.9
    5310
  549.18  548.62  548.44  548.01  547.32  546.43   545.6  541.38  540.02  539.59
   538.2     536     536     536     536     536     536     536     536     536
     536     536     536     536     536     536     536     536     536     536
     536     536     536     536     536     536  536.77  537.21  538.45  538.62
  540.22  542.22  542.87  542.95  542.55  542.53   544.6  547.47  547.82  548.64
   548.7
  549.18  548.61  548.43     548  547.31  546.42  545.59  541.37  540.01  539.58
  538.19  535.41  533.59  530.51  528.11  526.34  524.69     531     531     531
     531     531     531     531     531     531     531   525.5  525.51  526.63
  528.24  530.13  531.74  532.83  534.13  535.92  536.76   537.2  538.44  538.61
  540.21  542.21  542.86  542.94  542.54  542.52  544.59  547.46  547.82  548.64
   548.7
  4558.4  4658.4  4690.9  4766.3  4776.3  4796.3  4806.3  4846.3  4865.3  4875.3
  4885.3  4895.3  4905.3  4915.3  4925.3  4935.3 4968.91    4969  4969.1  4975.3
  4982.5  4987.5    5000  5012.5  5017.5  5030.8 5030.89    5031  5031.1  5041.1
  5051.1  5061.1  5071.1  5081.1  5101.1  5111.1  5121.1  5131.1  5141.1    5143
  5161.1  5171.1  5181.1  5191.1  5201.1  5211.1  5251.1  5286.6  5291.1  5307.9
    5310
  549.18  548.62  548.44  548.01  547.32  546.43   545.6  541.38  540.02  539.59
   538.2     536     536     536     536     536     536     536     536     536
     536     536     536     536     536     536     536     536     536     536
     536     536     536     536     536     536  536.77  537.21  538.45  538.62
  540.22  542.22  542.87  542.95  542.55  542.53   544.6  547.47  547.82  548.64
   548.7
  548.93  548.36  548.18  547.75  547.06  546.17  545.34  541.12  539.76  539.33
  537.94  535.16  533.34  530.26  527.86  526.09  524.44  530.75  530.75  530.75
  530.75  530.75  530.75  530.75  530.75  530.75  530.75  525.25  525.26  526.38
  527.99  529.88  531.49  532.58  533.88  535.67  536.51  536.95  538.19  538.36
  539.96  541.96  542.61  542.69  542.29  542.27  544.34  547.21  547.57  548.39
  548.45
Pier Skew, UpSta & Num, DnSta & Num=  ,4984.5, 2 ,4984.5, 2 , 0 , 0 , 0 ,,
       1       1
  521.16     532
       1       1
  520.91  531.75
Pier Skew, UpSta & Num, DnSta & Num=  ,5015.5, 2 ,5015.5, 2 , 0 , 0 , 0 ,,
       1       1
  521.16     532
       1       1
  520.91  531.75
BR Coef= 1 , 1 , 0 ,1.25, 0 ,,,0.8,0,2,0,
WSPro=,,,, 1 ,,,, 0 ,,,, 0 ,,,,-1 ,-1 ,-1 , 0 , 0 , 0 , 0 , 0
BR U #Sta/Elev= 51
  4558.4  549.18  4658.4  548.61  4690.9  548.43  4766.3     548  4776.3  547.31
  4796.3  546.42  4806.3  545.59  4846.3  541.37  4865.3  540.01  4875.3  539.58
  4885.3  538.19  4895.3  535.41  4905.3  533.59  4915.3  530.51  4925.3  528.11
  4935.3  526.34 4968.91  524.69    4969  524.69  4969.1  524.68  4975.3  524.38
  4982.5     524  4987.5  520.33    5000  520.33  5012.5  520.33  5017.5     524
  5030.8  525.48 5030.89  525.49    5031   525.5  5031.1  525.51  5041.1  526.63
  5051.1  528.24  5061.1  530.13  5071.1  531.74  5081.1  532.83  5101.1  534.13
  5111.1  535.92  5121.1  536.76  5131.1   537.2  5141.1  538.44    5143  538.61
  5161.1  540.21  5171.1  542.21  5181.1  542.86  5191.1  542.94  5201.1  542.54
  5211.1  542.52  5251.1  544.59  5286.6  547.46  5291.1  547.82  5307.9  548.64
    5310   548.7
BR U #Mann= 3
  4558.4     .13  4982.5    .045  5017.5     .13
BR U Banks=4982.5,5017.5
BR D #Sta/Elev= 51
  4558.4  548.93  4658.4  548.36  4690.9  548.18  4766.3  547.75  4776.3  547.06
  4796.3  546.17  4806.3  545.34  4846.3  541.12  4865.3  539.76  4875.3  539.33
  4885.3  537.94  4895.3  535.16  4905.3  533.34  4915.3  530.26  4925.3  527.86
  4935.3  526.09 4968.91  524.44    4969  524.44  4969.1  524.43  4975.3  524.13
  4982.5  523.75  4987.5  520.08    5000  520.08  5012.5  520.08  5017.5  523.75
  5030.8  525.23 5030.89  525.24    5031  525.25  5031.1  525.26  5041.1  526.38
  5051.1  527.99  5061.1  529.88  5071.1  531.49  5081.1  532.58  5101.1  533.88
  5111.1  535.67  5121.1  536.51  5131.1  536.95  5141.1  538.19    5143  538.36
  5161.1  539.96  5171.1  541.96  5181.1  542.61  5191.1  542.69  5201.1  542.29
  5211.1  542.27  5251.1  544.34  5286.6  547.21  5291.1  547.57  5307.9  548.39
    5310  548.45
BR D #Mann= 3
  4558.4     .13  4982.5    .045  5017.5     .13
BR D Banks=4982.5,5017.5
BC Design=,, 0 ,, 0 ,,,,,,
BC HTab HWMax=549.18

Type RM Length L Ch R = 1 ,24970.0 ,184.5,184.5,184.5
BEGIN DESCRIPTION:
Downstream Section of Bridge/Culvert/Weir
END DESCRIPTION:
XS GIS Cut Line= 4
      1865360.95       811334.42      1865599.18       811208.18
      1865760.03       811155.24      1866048.31       811034.21
#Sta/Elev= 30
  4558.4  548.84  4766.3  547.66  4796.3  546.08  4846.3  541.03  4875.3  539.24
  4885.3  537.85  4895.3  535.07  4905.3  533.25  4915.3  530.17  4925.3  527.77
  4935.3     526  4982.5  523.66  4987.5  519.99  5012.5  519.99  5017.5  523.66
  5041.1  526.29  5071.1   531.4  5081.1  532.49  5101.1  533.79  5111.1  535.58
  5131.1  536.86  5141.1   538.1  5161.1  539.87  5171.1  541.87  5181.1  542.52
  5191.1   542.6  5211.1  542.18  5251.1  544.25  5291.1  547.48    5310  548.36
#Mann= 3 , 1 , 0
  4558.4     .13       0  4982.5    .045       0  5017.5     .13       0
#XS Ineff= 2 , 0
       0  4965.9     536  5035.8       0     536
Permanent Ineff=
       F       F
Bank Sta=4982.5,5017.5
XS Rating Curve= 0
Exp/Cntr=0.5,0.3

Type RM Length L Ch R = 1 ,24785.5 ,0,0,0
BEGIN DESCRIPTION:
Rock Creek 1 1.0
END DESCRIPTION:
XS GIS Cut Line= 5
      1865413.12       811411.54       1865547.5       811326.02
      1865671.71        811307.7      1865909.93       811181.46
      1866050.42       811071.51
#Sta/Elev= 30
  4720.1  560.61  4760.1  556.23  4780.1  553.18  4790.1  553.45  4810.1  550.98
  4820.1  550.53  4860.1  546.23  4870.1  545.73  4899.4     540  4939.4  528.75
  4949.4  525.29  4959.4  524.04  4969.4  523.83  4989.6  521.34  4991.1  518.34
  5008.8  518.34  5010.3  521.34  5034.9  523.12  5044.9   525.3  5054.9  525.29
  5074.9  526.72  5104.9  530.09  5134.9  531.74  5144.9   532.8  5174.9  533.02
  5204.9   534.5  5304.5  536.86  5324.5  538.81  5414.5  543.23  5452.9  544.64
#Mann= 3 , 1 , 0
  4720.1     .13       0  4989.6    .045       0  5010.3     .13       0
Bank Sta=4989.6,5010.3
XS Rating Curve= 0
Exp/Cntr=0.3,0.1

Chan Stop Cuts=-1