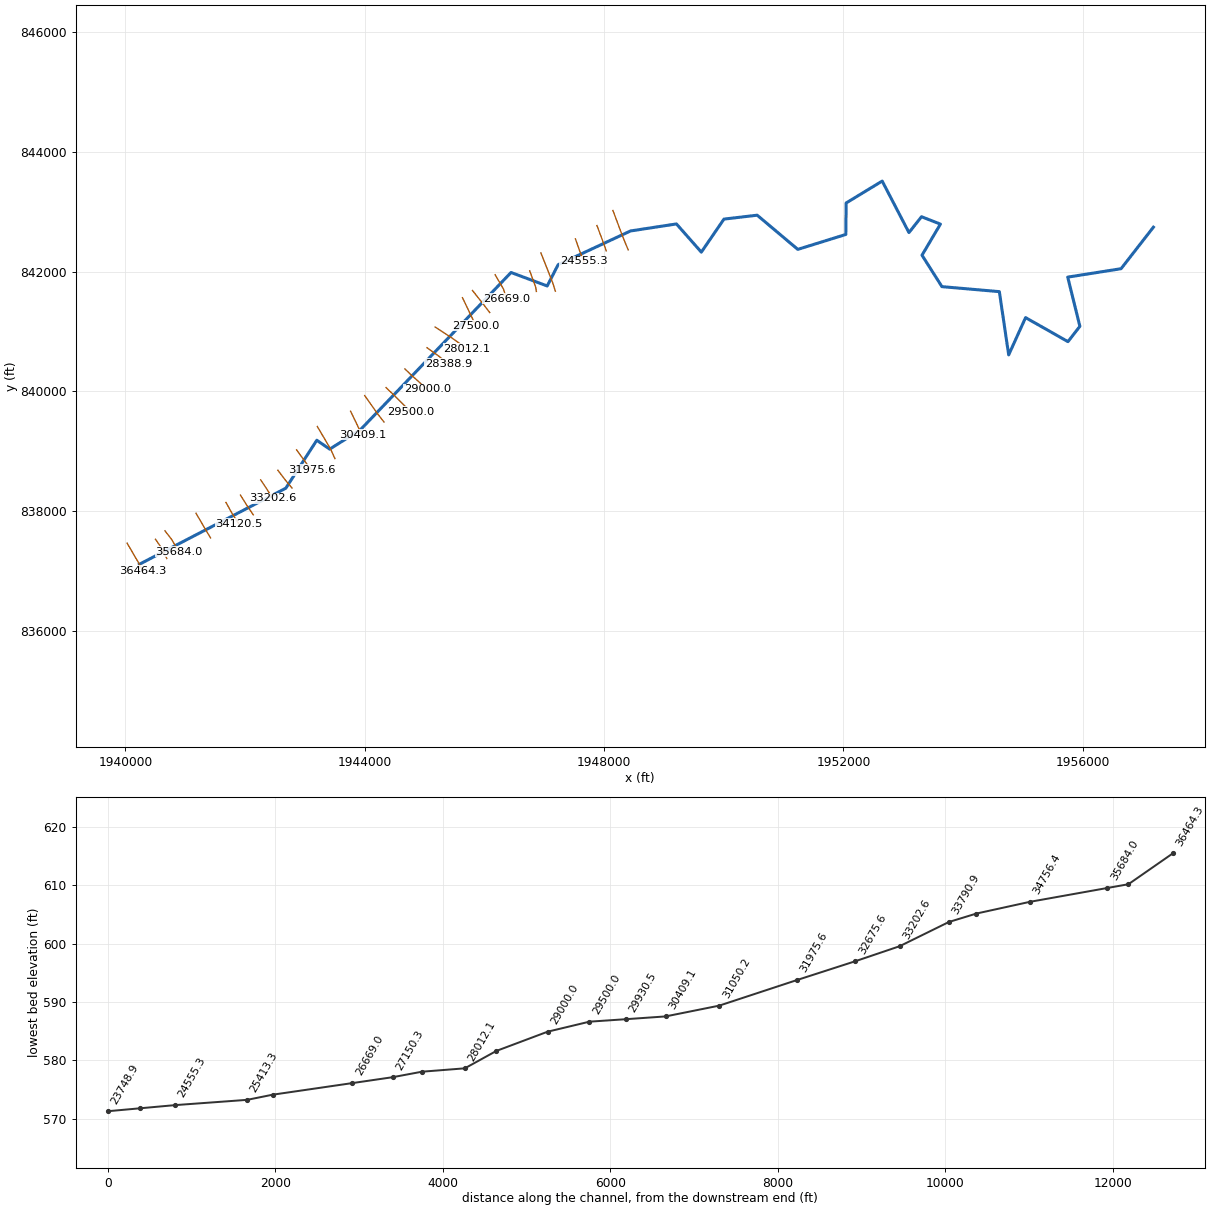
--- Sevenmile_Creek_FINAL.prj (project) ---

Proj Title=Sevenmile Creek
Current Plan=p02
Default Exp/Contr=0.3,0.1
English Units
Geom File=g01
Flow File=f02
Plan File=p02
Y Axis Title=Elevation
X Axis Title(PF)=Main Channel Distance
X Axis Title(XS)=Station
BEGIN DESCRIPTION:
####(Watershed Name)####
SEVENMILE CREEK
HCFCD Unit X###-##-##
(Flood Hazard, Floodway) Model
10, 2, 1, 0.2% Event
Filename:  n:\NC_flood\60138\Orange\URS\Limited_Detail\ENG\Sevenmile Creek\Sevenmile Creek.prj
Prepared by:  ________     Date: ________
Reviewed by:  ________     Date: ________
STATUS (Draft RAS, SVSQ, FINAL)
END DESCRIPTION:
DSS Export Rating Curves= 0
DSS Export Rating Curve Sorted= 0
DSS Export Volume Flow Curves= 0
DXF OffsetX= 0
DXF OffsetY= 0
DXF ScaleX= 1
DXF ScaleY= 10

--- Sevenmile_Creek_FINAL.p02 (plan) ---

Plan Title=floodway
Version=Version 3.0.1  Mar 2001
Short Identifier=fw
Geom File=g01
Flow File=f02
Subcritical Flow
K Sum by GR= 0
Std Step Tol= 0.01
Critical Tol= 0.01
Num of Std Step Trials= 20
Max Error Tol= 0.3
Flow Tol Ratio= 0.001
Split Flow NTrial= 30
Split Flow Tol= 0.02
Split Flow Ratio= 0.02
Log Output Level= 0
Friction Slope Method= 1
Unsteady Friction Slope Method= 2
Parabolic Critical Depth
Global Vel Dist= 0 , 0 , 0
Global Log Level= 0
CheckData=True
Encroach Param=-1 ,0,0, 2
Encroach River=Sevenmile Creek
Encroach Reach=Reach - 1
Encroach Node=36464.3
       1    4871    5013
Encroach Node=35934.7
       1 4989.01 5009.48
Encroach Node=35684.0
       1 4958.22  5084.2
Encroach Node=34756.4
       1    4985    5040
Encroach Node=34120.5
       1 4920.04 5123.17
Encroach Node=33790.9
       1 4938.58 5084.75
Encroach Node=33202.6
       1 4928.12 5041.12
Encroach Node=32675.6
       1 4950.94 5070.98
Encroach Node=31975.6
       1    4824    5012
Encroach Node=31050.2
       1    4929    5015
Encroach Node=30409.1
       1 4825.66 5024.25
Encroach Node=29930.5
       1 4969.01 5081.91
Encroach Node=29500.0
       1 4937.92 5099.14
Encroach Node=29000.0
       1 4940.86 5125.84
Encroach Node=28388.9
       1 4881.34 5054.18
Encroach Node=28012.1
       1  4910.8 5081.78
Encroach Node=27500.0
       1 4881.77 5024.84
Encroach Node=27150.3
       1 4939.81 5089.89
Encroach Node=26669.0
       1 4908.07 5036.57
Encroach Node=25716.7
       1 4887.36    5010
Encroach Node=25413.3
       1    4835    5020
Encroach Node=24555.3
       1 4972.52  5053.1
Encroach Node=24131.7
       1  4939.2 5062.48
Encroach Node=23748.9
       1  4970.4 5075.43
Encroach Node=23000.0
       1    4945    5020
Encroach Node=22528.7
       1    4960 5047.19
Encroach Node=21679.4
       1    4905    5018
Encroach Node=21135.7
       1 4944.85 5055.05
Encroach Node=21112.9
       1 4944.85 5055.05
Encroach Node=21090.2
       1 4944.85 5055.05
Encroach Node=20701.0
       1 4945.09 5030.65
Encroach Node=19998.9
       1  4963.4 5017.15
Encroach Node=19407.7
       1 4714.38 5032.81
Encroach Node=18869.5
       1 4934.18 5018.63
Encroach Node=18436.5
       1 4987.77 5051.48
Encroach Node=18066.4
       1    4980    5083
Encroach Node=17606.3
       1    4980    5145
Encroach Node=17000.0
       1 4984.81    5053
Encroach Node=16710.2
       1 4973.35 5024.63
Encroach Node=16384.5
       1 4730.12 5023.32
Encroach Node=15618.8
       1    4975    5358
Encroach Node=14887.1
       1 4880.76 5079.92
Encroach Node=14540.3
       1    4980    5055
Encroach Node=14098.1
       1    4845    5020
Encroach Node=13425.2
       1 4945.97 5035.53
Encroach Node=12949.0
       1 4977.81 5034.96
Encroach Node=12589.7
       1  4979.5 5151.92
Encroach Node=11924.3
       1    4919    5013
Encroach Node=11410.1
       1 4945.56 5032.65
Encroach Node=10966.0
       1  4983.3 5039.67
Encroach Node=10504.4
       1 4975.01 5038.71
Encroach Node=9896.9
       1 4897.79 5034.65
Encroach Node=9206.8
       1  4971.4 5074.59
Encroach Node=8839.6
       1 4952.94  5089.5
Encroach Node=8442.9
       1 4915.12 5036.65
Encroach Node=7955.6
       1    4747    5017
Encroach Node=7534.1
       1    4715    5020
Encroach Node=7067.5
       1    4872    5128
Computation Interval=1HOUR
Output Interval=1HOUR
Run HTab= 0
Run UNet= 0
Run PostProcess= 0
UNET Theta= 1
UNET ZTol= 0.02
UNET ZSATol= 0.1
UNET MxIter= 20
UNET MaxInSteps= 20
UNET DtIC= 0
UNET DtMin= 0
UNET MaxCRTS= 20
UNET WFStab= 2
UNET SFStab= 1
UNET WFX= 1
UNET SFX= 1
UNET Convert EG Bridges=-1
UNET Use Existing IB Tables=-1
Instantaneous Interval=1HOUR
Write IC File= 0
Write Velocity= 0
Write Detailed= 0

--- Sevenmile_Creek_FINAL.f02 (steady flow) ---

Flow Title=100 Year floodway
Version=Version 3.0.1  Mar 2001
Number of Profiles= 2
Profile Names=100-Year,100 yr fw
River Rch & RM=Sevenmile Creek,Reach - 1       ,36464.3
     764     764
River Rch & RM=Sevenmile Creek,Reach - 1       ,34120.5
    1510    1510
River Rch & RM=Sevenmile Creek,Reach - 1       ,27500
    2995    2995
River Rch & RM=Sevenmile Creek,Reach - 1       ,18869.5
    3184    3184
River Rch & RM=Sevenmile Creek,Reach - 1       ,11410.1
    3920    3920
Boundary for River Rch & Prof#=Sevenmile Creek,Reach - 1       , 1
Up Type= 0
Dn Type= 1
Dn Known WS=532.7
Boundary for River Rch & Prof#=Sevenmile Creek,Reach - 1       , 2
Up Type= 0
Dn Type= 1
Dn Known WS=533.4
DSS Import GetInterval= 0
DSS Import GetPeak= 0
DSS Import FillOption= 0

--- Sevenmile_Creek_FINAL.g01 (geometry) ---

Geom Title=Geom 01 by CodeH2 for Windows

River Reach=Sevenmile Creek,Reach - 1
Reach XY= 30
 1940233.4167027 837113.09628810      1942680.29       838383.08
      1943197.54       839183.85      1943413.37        839035.7
      1943924.23       839356.26      1946444.22       841985.39
      1947048.83       841759.96      1947231.26        842115.7
      1948441.14       842678.61      1949208.64       842795.89
      1949624.38       842325.26      1950002.85       842876.68
      1950557.94       842941.83      1951236.76       842371.13
      1952039.38       842620.24      1952044.59       843145.63
      1952647.12       843511.52      1953094.33       842651.51
      1953304.38       842916.29      1953620.24       842793.28
      1953312.53       842273.89      1953645.36       841748.98
      1954605.16        841665.3      1954761.11       840609.14
      1955043.49       841231.83      1955751.95       840830.42
      1955950.94       841086.59      1955747.95        841907.7
       1956639.4       842048.37 1957179.7742462 842741.80367615

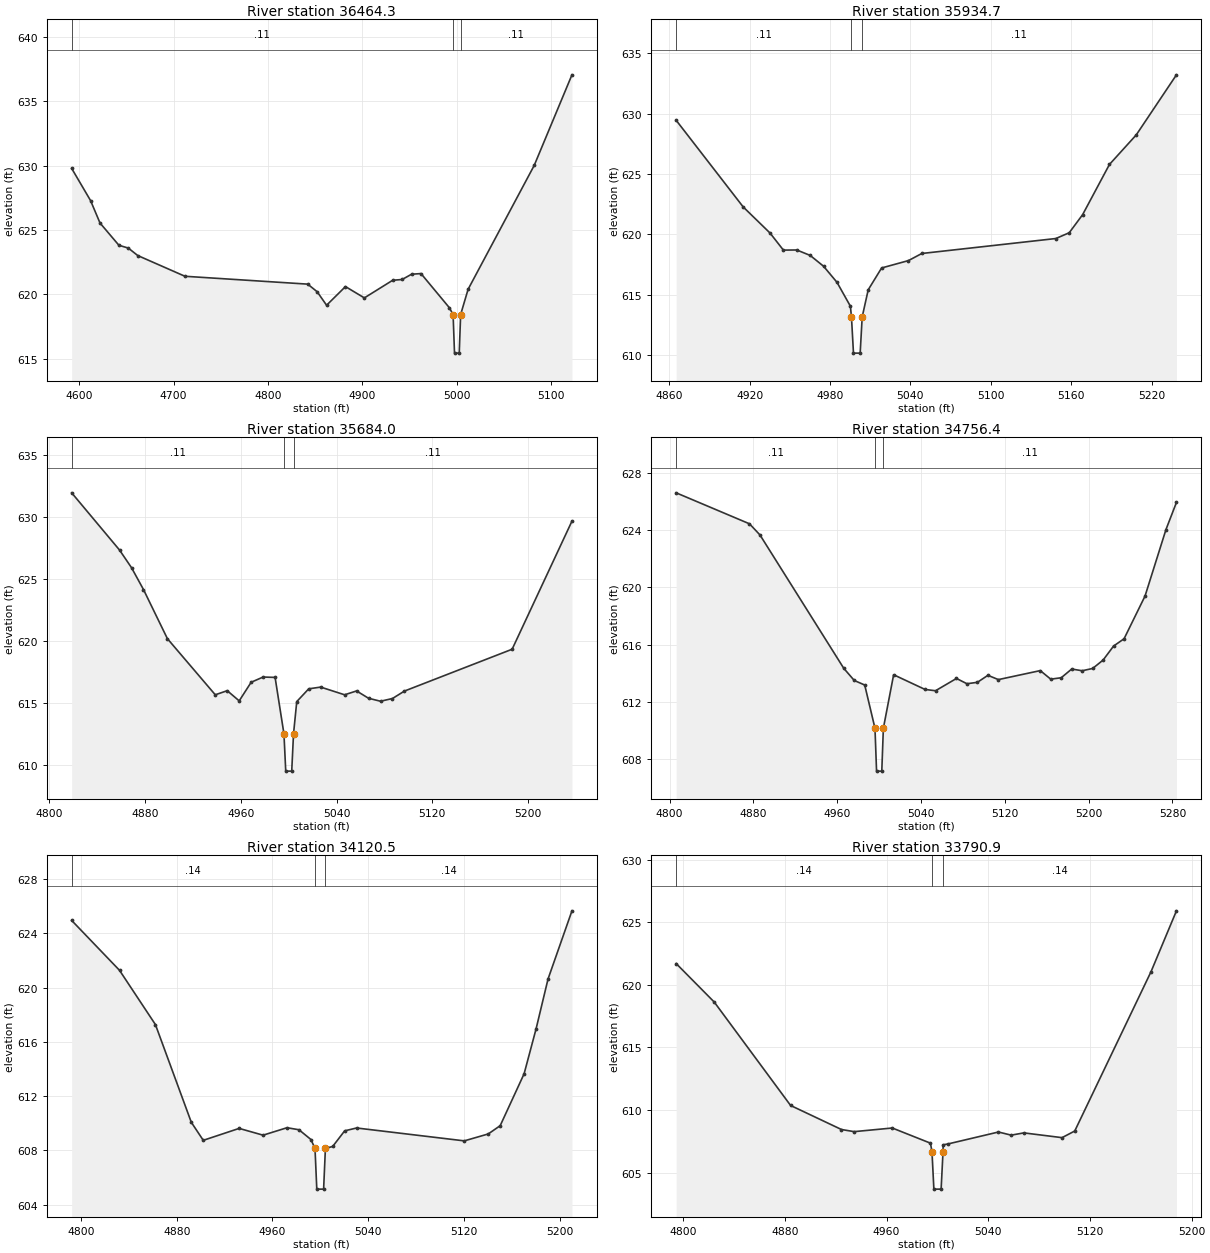
Type RM Length L Ch R = 1 ,36464.3,529.6,529.6,529.6
XS GIS Cut Line= 3
 1940027.6936689 837465.47737028 1940229.4073466 837120.17090507
 1940293.1604162 837006.83211455
BEGIN DESCRIPTION:
Sevenmile Creek 73.0
END DESCRIPTION:
#Sta/Elev= 24
    4592  629.79    4612  627.29    4622  625.55    4642  623.82    4652   623.6
    4662  623.02    4712  621.41    4842   620.8    4852  620.21    4862  619.16
    4882  620.61    4902  619.73    4932   621.1    4942  621.16    4952  621.57
    4962  621.62  4991.9  618.98    4996  618.44  4997.5  615.44  5002.5  615.44
    5004  618.44  5011.9   620.4  5081.9  630.02  5121.9  637.06
#Mann= 3 , 1 , 0
 4592.00    0.11       0    4996    0.04       0    5004    0.11       0
Bank Sta=4996.00,5004.00
Exp/Cntr=0.3,0.1

Type RM Length L Ch R = 1 ,35934.7,250.7,250.7,250.7
XS GIS Cut Line= 3
 1940501.9543491 837530.41626467 1940578.1326877 837421.03198366
 1940691.2001721 837209.33116173
BEGIN DESCRIPTION:
Sevenmile Creek 72.0
END DESCRIPTION:
#Sta/Elev= 23
  4865.2  629.46  4915.2  622.28  4935.2  620.12  4945.2   618.7  4955.2  618.71
  4965.2  618.26  4975.2  617.36  4985.2  616.03  4995.2  614.05    4996  613.16
  4997.5  610.16  5002.5  610.16    5004  613.16  5008.5  615.41  5018.5  617.22
  5038.5  617.83  5048.5  618.42  5148.5  619.66  5158.5  620.14  5168.5  621.64
  5188.5   625.8  5208.5  628.25  5238.5  633.23
#Mann= 3 , 1 , 0
 4865.20    0.11       0    4996    0.04       0    5004    0.11       0
Bank Sta=4996.00,5004.00
Exp/Cntr=0.3,0.1

Type RM Length L Ch R = 1 ,35684.0,927.6,927.6,927.6
XS GIS Cut Line= 3
 1940660.6006405 837671.21359607 1940769.5897377 837530.43601224
 1940894.0635196 837325.16345959
BEGIN DESCRIPTION:
Sevenmile Creek 71.0
END DESCRIPTION:
#Sta/Elev= 26
  4818.6  631.94  4858.6  627.33  4868.6  625.91  4878.6  624.15  4898.6  620.19
  4938.6  615.67  4948.6     616  4958.6  615.18  4968.6  616.68  4978.6   617.1
  4988.6  617.07    4996  612.52  4997.5  609.52  5002.5  609.52    5004  612.52
  5006.7  615.12  5016.7  616.15  5026.7  616.29  5046.7  615.67  5056.7  615.98
  5066.7  615.39  5076.7  615.15  5086.7  615.37  5096.7  615.97  5186.7  619.34
  5236.7  629.66
#Mann= 3 , 1 , 0
 4818.60    0.11       0    4996    0.04       0    5004    0.11       0
Bank Sta=4996.00,5004.00
Exp/Cntr=0.3,0.1

Type RM Length L Ch R = 1 ,34756.4,635.9,635.9,635.9
XS GIS Cut Line= 3
 1941179.8548449 837964.63325067 1941279.0022458 837793.68945601
 1941422.2140330 837553.09365344
BEGIN DESCRIPTION:
Sevenmile Creek 69.0
END DESCRIPTION:
#Sta/Elev= 30
  4806.2  626.63  4876.2  624.46  4886.2  623.68  4966.2  614.34  4976.2  613.49
  4986.2  613.17    4996  610.14  4997.5  607.14  5002.5  607.14    5004  610.14
  5013.8  613.89  5043.8  612.86  5053.8  612.77  5073.8  613.63  5083.8  613.26
  5093.8  613.36  5103.8  613.85  5113.8  613.55  5153.8  614.18  5163.8  613.58
  5173.8  613.68  5183.8  614.29  5193.8  614.17  5203.8  614.33  5213.8  614.92
  5223.8   615.9  5233.8  616.41  5253.8   619.4  5273.8  624.06  5283.8  625.96
#Mann= 3 , 1 , 0
 4806.20    0.11       0    4996    0.04       0    5004    0.11       0
Bank Sta=4996.00,5004.00
Exp/Cntr=0.3,0.1

Type RM Length L Ch R = 1 ,34120.5,329.6,329.6,329.6
XS GIS Cut Line= 3
 1941679.0107253 838145.83367301 1941781.5770021 837964.63325067
 1941894.4948243 837787.62693473
BEGIN DESCRIPTION:
Sevenmile Creek 68.0
END DESCRIPTION:
#Sta/Elev= 24
  4792.2  624.96  4832.2  621.28  4862.2  617.28  4892.2  610.07  4902.2  608.74
  4932.2  609.62  4952.2  609.12  4972.2  609.67  4982.2  609.52  4992.2   608.8
  4995.6  608.14  4997.1  605.14  5002.8  605.14  5004.3  608.14  5010.4  608.29
  5020.4  609.44  5030.4  609.65  5120.4   608.7  5140.4  609.21  5150.4  609.82
  5170.4  613.65  5180.4  616.96  5190.4  620.64  5210.4  625.67
#Mann= 3 , 1 , 0
 4792.20    0.14       0  4995.6    0.04       0  5004.3    0.14       0
Bank Sta=4995.60,5004.30
Exp/Cntr=0.3,0.1

Type RM Length L Ch R = 1 ,33790.9,588.3,588.3,588.3
XS GIS Cut Line= 3
 1941921.7509137 838268.91320516 1942034.5738181 838087.71278282
 1942136.4680996 837939.23825837
BEGIN DESCRIPTION:
Sevenmile Creek 67.0
END DESCRIPTION:
#Sta/Elev= 20
  4794.5   621.7  4824.5  618.62  4884.5  610.37  4924.5  608.45  4934.5  608.28
  4964.5  608.57  4994.5  607.36  4995.7  606.69  4997.2  603.69  5002.9  603.69
  5004.4  606.69  5004.5  607.23    5008  607.29    5048  608.25    5058     608
    5068  608.18    5098   607.8    5108  608.33    5168  621.05    5188  625.91
#Mann= 3 , 1 , 0
 4794.50    0.14       0  4995.7    0.04       0  5004.4    0.14       0
Bank Sta=4995.70,5004.40
Exp/Cntr=0.3,0.1

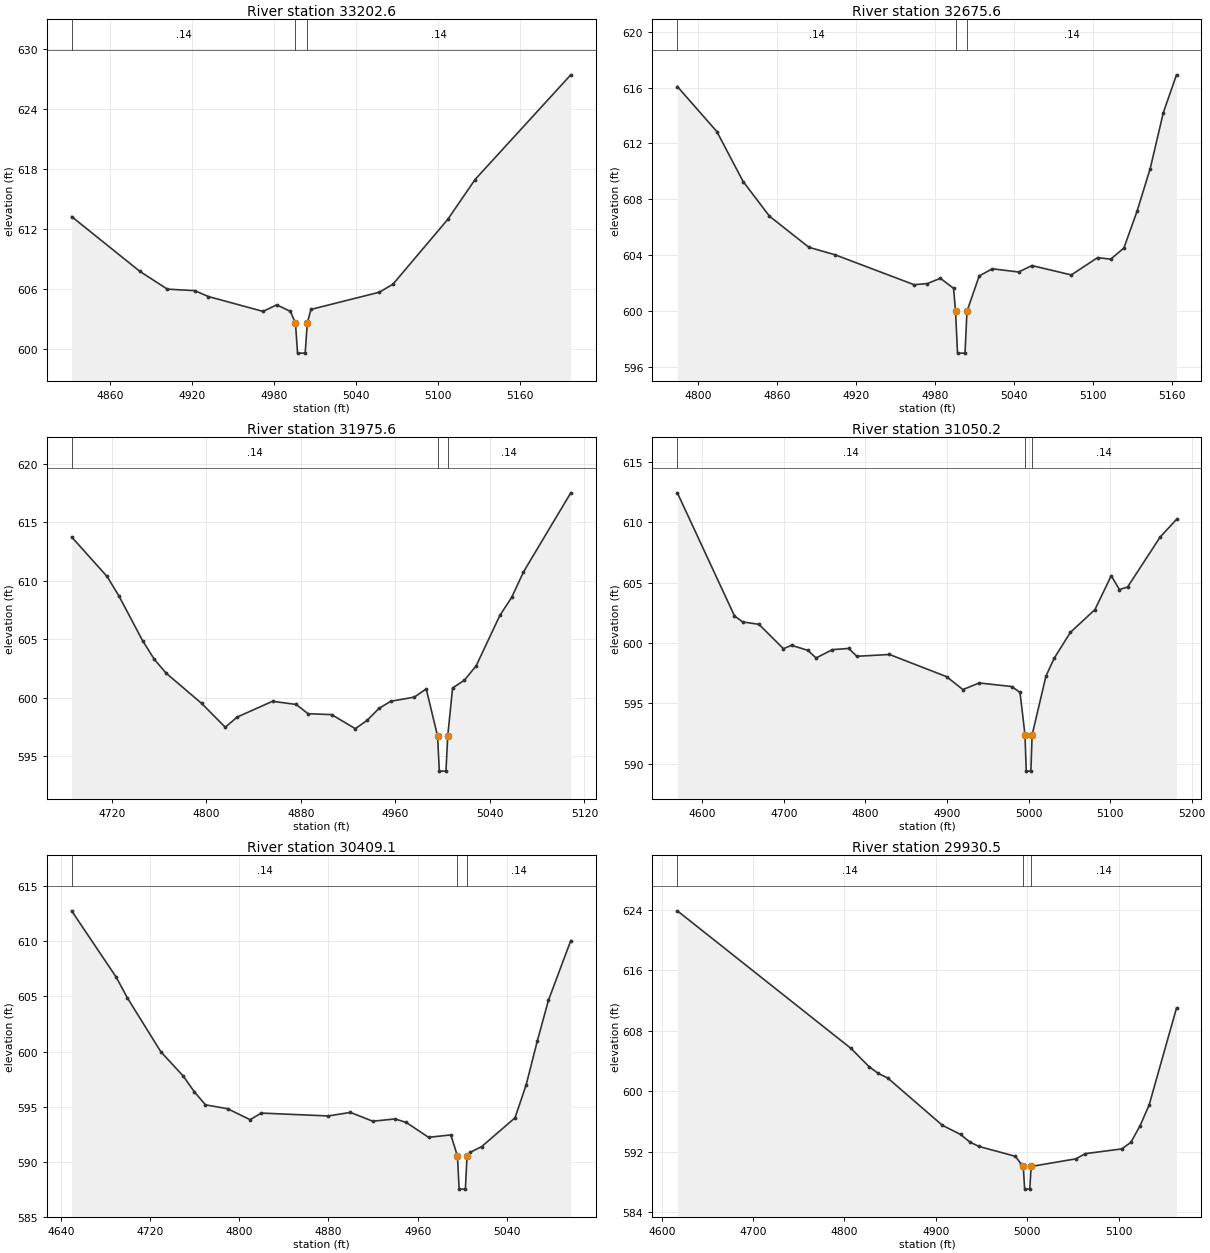
Type RM Length L Ch R = 1 ,33202.6,527,527,527
XS GIS Cut Line= 3
 1942260.2196271 838521.91002125 1942352.5292762 838385.15498552
 1942458.9275154 838215.78635979
BEGIN DESCRIPTION:
Sevenmile Creek 66.0
END DESCRIPTION:
#Sta/Elev= 18
    4832  613.22    4882  607.72    4902  605.95    4922   605.8    4932  605.21
    4972  603.72    4982  604.38    4992  603.72  4995.7  602.54  4997.2  599.54
  5002.8  599.54  5004.3  602.54    5007  603.92    5057  605.64    5067  606.45
    5107  612.93    5127  616.93    5197  627.42
#Mann= 3 , 1 , 0
 4832.00    0.14       0  4995.7    0.04       0  5004.3    0.14       0
Bank Sta=4995.70,5004.30
Exp/Cntr=0.3,0.1

Type RM Length L Ch R = 1 ,32675.6,700,700,700
XS GIS Cut Line= 3
 1942547.4052021 838682.59718823 1942680.7413619 838508.23451768
 1942783.8319394 838385.81445698
BEGIN DESCRIPTION:
Sevenmile Creek 65.0
END DESCRIPTION:
#Sta/Elev= 26
  4784.2  616.07  4814.2  612.85  4834.2  609.27  4854.2  606.79  4884.2  604.56
  4904.2  604.02  4964.2  601.88  4974.2  601.96  4984.2  602.34  4994.2  601.62
  4995.7  599.98  4997.2  596.98  5002.9  596.98  5004.4  599.98  5013.7  602.51
  5023.7  603.02  5043.7  602.79  5053.7  603.25  5083.7  602.58  5103.7  603.82
  5113.7  603.71  5123.7  604.51  5133.7  607.14  5143.7   610.2  5153.7  614.21
  5163.7  616.91
#Mann= 3 , 1 , 0
 4784.20    0.14       0  4995.7    0.04       0  5004.4    0.14       0
Bank Sta=4995.70,5004.40
Exp/Cntr=0.3,0.1

Type RM Length L Ch R = 1 ,31975.6,925.4,925.4,925.4
XS GIS Cut Line= 3
 1942859.6481214 839024.26015124 1943043.1422066 838771.48796145
 1943113.8598002 838687.30035002
BEGIN DESCRIPTION:
Sevenmile Creek 64.0
END DESCRIPTION:
#Sta/Elev= 30
  4686.1  613.76  4716.1  610.38  4726.1  608.72  4746.1   604.9  4756.1  603.29
  4766.1  602.11  4796.1  599.53  4816.1  597.49  4826.1  598.36  4856.1  599.71
  4876.1  599.44  4886.1  598.65  4906.1  598.57  4926.1  597.37  4936.1  598.08
  4946.1   599.1  4956.1  599.71  4976.1  600.07  4986.1  600.77  4995.7  596.74
  4997.2  593.74  5002.8  593.74  5004.3  596.74  5008.4  600.85  5018.4  601.51
  5028.4  602.75  5048.4  607.05  5058.4  608.59  5068.4  610.77  5108.4  617.53
#Mann= 3 , 1 , 0
 4686.10    0.14       0  4995.7    0.04       0  5004.3    0.14       0
Bank Sta=4995.70,5004.30
Exp/Cntr=0.3,0.1

Type RM Length L Ch R = 1 ,31050.2,641.1,641.1,641.1
XS GIS Cut Line= 3
 1943206.6953702 839413.42269570 1943426.0563066   839041.579157
 1943500.9652385 838877.82474784
BEGIN DESCRIPTION:
Sevenmile Creek 63.0
END DESCRIPTION:
#Sta/Elev= 30
  4569.6  612.44  4639.6  602.24  4649.6  601.74  4669.6  601.54  4699.6  599.52
  4709.6   599.8  4729.6  599.38  4739.6  598.75  4759.6  599.44  4779.6  599.54
  4789.6  598.89  4829.6  599.04  4899.6   597.2  4919.6  596.13  4939.6  596.68
  4979.6  596.38  4989.6  595.89  4995.7  592.37  4997.2  589.37  5002.9  589.37
  5004.4  592.37  5021.4  597.25  5031.4  598.72  5051.4  600.88  5081.4  602.76
  5101.4  605.57  5111.4  604.42  5121.4  604.63  5161.4  608.78  5181.4  610.24
#Mann= 3 , 1 , 0
 4569.60    0.14       0  4995.7    0.04       0  5004.4    0.14       0
Bank Sta=4995.70,5004.40
Exp/Cntr=0.3,0.1

Type RM Length L Ch R = 1 ,30409.1,478.6,478.6,478.6
XS GIS Cut Line= 3
 1943763.1200890 839667.95394925 1943918.3744353 839345.85911149
 1943973.1114468 839274.49313447
BEGIN DESCRIPTION:
Sevenmile Creek 61.0
END DESCRIPTION:
#Sta/Elev= 28
  4649.8  612.77  4689.8  606.75  4699.8  604.87  4729.8  599.98  4749.8  597.79
  4759.8  596.35  4769.8  595.17  4789.8  594.81  4809.8  593.82  4819.8  594.42
  4879.8  594.16  4899.8  594.48  4919.8  593.68  4939.8  593.89  4949.8  593.57
  4969.8  592.22  4989.8  592.44  4995.7  590.52  4997.2  587.52  5002.8  587.52
  5004.3  590.52  5007.3  590.87  5017.3  591.37  5047.3  593.99  5057.3  596.98
  5067.3  600.96  5077.3  604.66  5097.3  610.07
#Mann= 3 , 1 , 0
 4649.80    0.14       0  4995.7    0.04       0  5004.3    0.14       0
Bank Sta=4995.70,5004.30
Exp/Cntr=0.3,0.1

Type RM Length L Ch R = 1 ,29930.5,430.5,430.5,430.5
XS GIS Cut Line= 3
 1943998.7310156 839930.09108265  1944215.816638 839622.78805883
 1944320.8794479 839489.07175524
BEGIN DESCRIPTION:
Sevenmile Creek 60.0
END DESCRIPTION:
#Sta/Elev= 22
  4617.1  623.86  4807.1  605.66  4827.1  603.22  4837.1  602.34  4847.1  601.76
  4907.1  595.49  4927.1  594.27  4937.1  593.28  4947.1  592.69  4987.1  591.38
  4993.4  590.34  4995.7  590.04  4997.2  587.04  5002.8  587.04  5004.3  590.04
  5053.4  591.05  5063.4  591.73  5103.4  592.36  5113.4  593.22  5123.4   595.4
  5133.4  598.16  5163.4  611.01
#Mann= 3 , 1 , 0
 4617.10    0.14       0  4995.7    0.04       0  5004.3    0.14       0
Bank Sta=4995.70,5004.30
Exp/Cntr=0.3,0.1

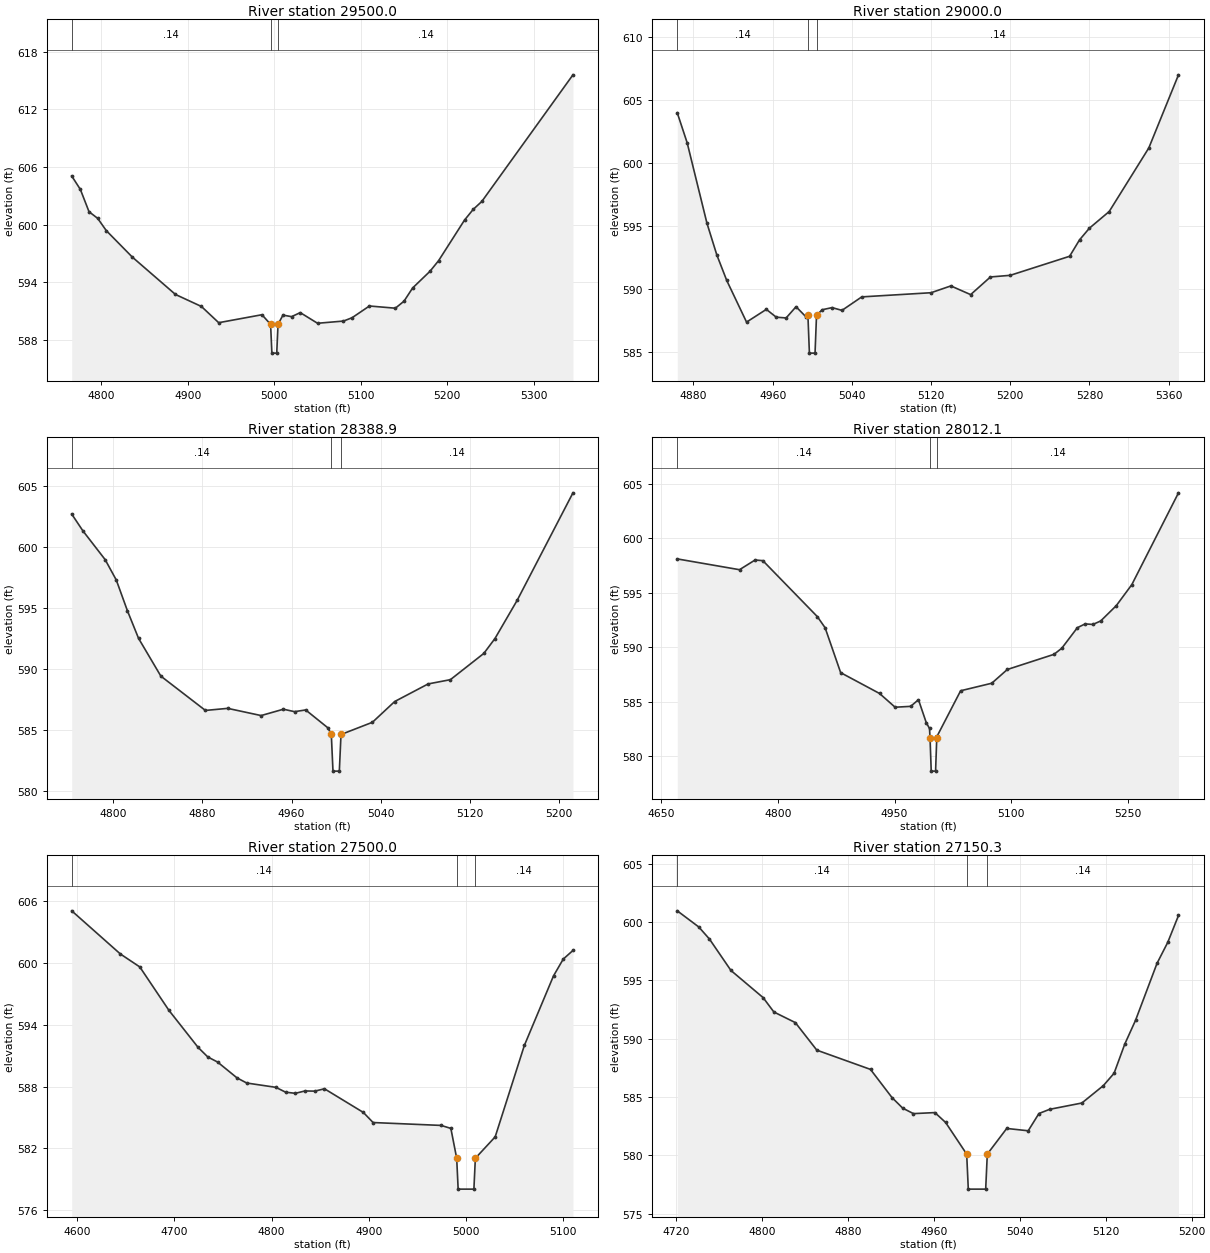
Type RM Length L Ch R = 1 ,29500.0,500,500,500
XS GIS Cut Line= 3
 1944355.9535761 840063.00959236 1944524.9376017 839900.71095102
 1944769.6745326 839656.97681777
BEGIN DESCRIPTION:
Sevenmile Creek 59.0
END DESCRIPTION:
#Sta/Elev= 30
  4765.7  605.07  4775.7  603.67  4785.7  601.35  4795.7  600.66  4805.7  599.38
  4835.7  596.63  4885.7  592.73  4915.7  591.48  4935.7  589.79  4985.7  590.62
  4995.7  589.62  4997.2  586.62  5002.8  586.62  5004.3  589.62    5010  590.58
    5020  590.42    5030  590.84    5050  589.73    5080  589.96    5090  590.31
    5110  591.53    5140   591.3    5150  592.03    5160  593.41    5180  595.14
    5190  596.25    5220  600.48    5230  601.59    5240  602.42  5345.4  615.61
#Mann= 3 , 1 , 0
 4765.70    0.14       0  4995.7    0.04       0  5004.3    0.14       0
Bank Sta=4995.70,5004.30
Exp/Cntr=0.3,0.1

Type RM Length L Ch R = 1 ,29000.0,611.1,611.1,611.1
XS GIS Cut Line= 3
 1944670.8789031 840374.85633840 1944769.1371106 840280.25202685
 1945044.8681338 840033.52699616
BEGIN DESCRIPTION:
Sevenmile Creek 58.0
END DESCRIPTION:
#Sta/Elev= 30
  4863.6  603.96  4873.6  601.58  4893.6   595.2  4903.6  592.68  4913.6  590.66
  4933.6  587.36  4953.6  588.37  4963.6  587.75  4973.6  587.69  4983.6  588.58
  4993.6  587.78  4995.6   587.9  4997.1   584.9  5002.8   584.9  5004.3   587.9
    5010  588.34    5020  588.51    5030  588.29    5050  589.36    5120  589.69
    5140  590.23    5160  589.54    5180  590.94    5200  591.07    5260  592.58
    5270  593.88    5280  594.81    5300  596.13    5340  601.17    5370  606.97
#Mann= 3 , 1 , 0
 4863.60    0.14       0  4995.6    0.04       0  5004.3    0.14       0
Bank Sta=4995.60,5004.30
Exp/Cntr=0.3,0.1

Type RM Length L Ch R = 1 ,28388.9,376.8,376.8,376.8
XS GIS Cut Line= 3
 1945039.0035575 840729.16987613 1945234.6416541 840590.32993659
 1945396.9585560 840457.08471863
BEGIN DESCRIPTION:
Sevenmile Creek 57.0
END DESCRIPTION:
#Sta/Elev= 26
  4762.7  602.66  4772.7  601.29  4792.7  598.93  4802.7  597.26  4812.7  594.74
  4822.7  592.48  4842.7  589.39  4882.7  586.58  4902.7  586.75  4932.7  586.16
  4952.7  586.68  4962.7  586.48  4972.7  586.62  4992.7  585.15  4995.7  584.61
  4997.2  581.61  5002.9  581.61  5004.4  584.61  5032.6  585.61  5052.6  587.31
  5082.6  588.75  5102.6   589.1  5132.6  591.25  5142.6  592.47  5162.6  595.61
  5212.6   604.4
#Mann= 3 , 1 , 0
 4762.70    0.14       0  4995.7    0.04       0  5004.4    0.14       0
Bank Sta=4995.70,5004.40
Exp/Cntr=0.3,0.1

Type RM Length L Ch R = 1 ,28012.1,512.1,512.1,512.1
XS GIS Cut Line= 3
         1945175          841075 1945446.6119595 840898.02876697
 1945708.3927912 840713.91917105
BEGIN DESCRIPTION:
Sevenmile Creek 56.0
END DESCRIPTION:
#Sta/Elev= 30
  4670.8  598.09  4750.8   597.1  4770.8  597.99  4780.8  597.93  4850.8   592.8
  4860.8  591.78  4880.8  587.66  4930.8  585.75  4950.8  584.49  4970.8  584.57
  4980.8  585.18  4990.8  583.08    4995  582.54  4995.7  581.63  4997.2  578.63
  5002.8  578.63  5004.3  581.63    5005  581.87    5035     586    5075  586.69
    5095  587.95    5155  589.34    5165   589.9    5185  591.78    5195  592.13
    5205  592.08    5215   592.4    5235   593.8    5255  595.73    5315  604.15
#Mann= 3 , 1 , 0
 4670.80    0.14       0  4995.7    0.04       0  5004.3    0.14       0
Bank Sta=4995.70,5004.30
Exp/Cntr=0.3,0.1

Type RM Length L Ch R = 1 ,27500.0,349.7,349.7,349.7
XS GIS Cut Line= 3
 1945632.7027861 841563.84348238 1945808.4256303 841198.28320582
 1945851.4809969 841097.06149017
BEGIN DESCRIPTION:
Sevenmile Creek 55.0
END DESCRIPTION:
#Sta/Elev= 28
  4594.4  605.09  4644.4   600.9  4664.4  599.64  4694.4  595.42  4724.4  591.82
  4734.4  590.89  4744.4   590.4  4764.4  588.86  4774.4  588.36  4804.4  587.94
  4814.4  587.47  4824.4  587.36  4834.4  587.59  4844.4  587.57  4854.4   587.8
  4894.4   585.5  4904.4  584.52  4974.4  584.24  4984.4  583.95  4990.4  581.05
  4991.9  578.05  5008.1  578.05  5009.6  581.05    5030  583.13    5060  592.01
    5090  598.77    5100   600.4    5110  601.24
#Mann= 3 , 1 , 0
 4594.40    0.14       0  4990.4    0.04       0  5009.6    0.14       0
Bank Sta=4990.40,5009.60
Exp/Cntr=0.3,0.1

Type RM Length L Ch R = 1 ,27150.3,481.3,481.3,481.3
XS GIS Cut Line= 3
 1945800.3907770 841684.38467770 1945972.1615618 841467.20322565
 1946087.6425001 841316.32386553
BEGIN DESCRIPTION:
Sevenmile Creek 54.0
END DESCRIPTION:
#Sta/Elev= 30
  4720.8  600.96  4740.8  599.58  4750.8  598.54  4770.8  595.85  4800.8  593.52
  4810.8  592.29  4830.8  591.38  4850.8  589.02  4900.8  587.37  4920.8  584.96
  4930.8  584.05  4940.8  583.58  4960.8  583.67  4970.8  582.82  4990.4  580.11
  4991.9  577.11  5008.1  577.11  5009.6  580.11  5027.7  582.31  5047.7  582.11
  5057.7  583.59  5067.7  583.95  5097.7  584.49  5117.7  585.98  5127.7  587.04
  5137.7  589.55  5147.7  591.58  5167.7  596.46  5177.7  598.26  5187.7  600.56
#Mann= 3 , 1 , 0
 4720.80    0.14       0  4990.4    0.04       0  5009.6    0.14       0
Bank Sta=4990.40,5009.60
Exp/Cntr=0.3,0.1

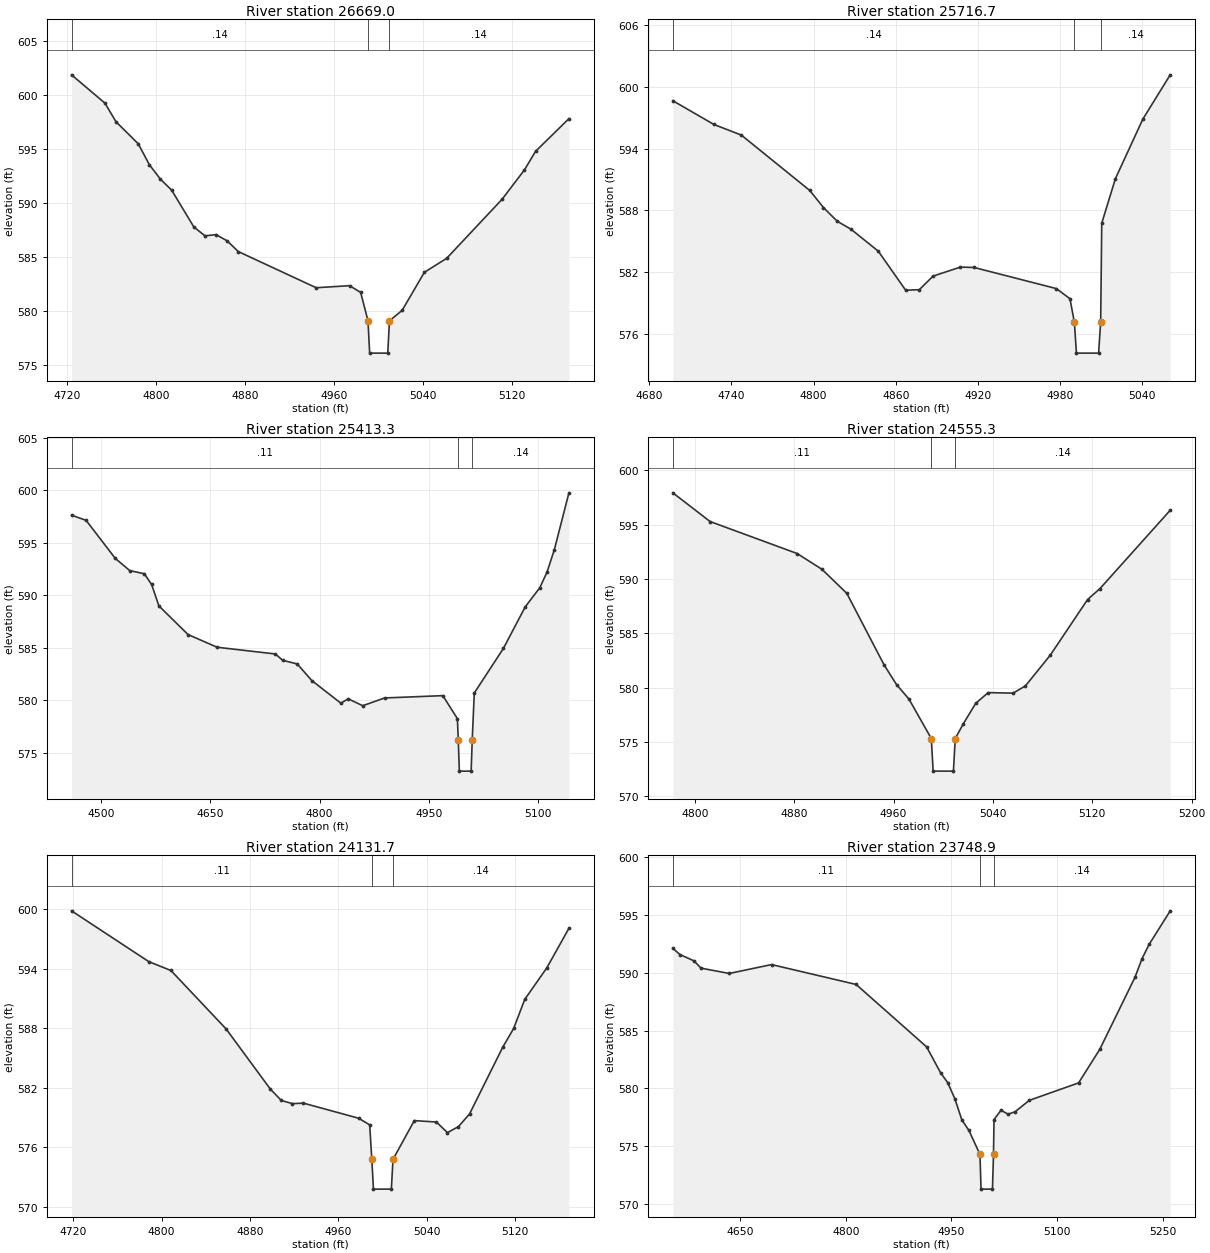
Type RM Length L Ch R = 1 ,26669.0,952.3,952.3,952.3
XS GIS Cut Line= 3
 1946178.1660983 841947.56807150 1946318.4253122 841708.30235364
 1946367.0672135 841545.45772764
BEGIN DESCRIPTION:
Sevenmile Creek 53.0
END DESCRIPTION:
#Sta/Elev= 26
  4723.7  601.89  4753.7  599.27  4763.7  597.54  4783.7   595.5  4793.7  593.56
  4803.7  592.21  4813.7  591.21  4833.7  587.79  4843.7  586.97  4853.7  587.08
  4863.7   586.5  4873.7  585.51  4943.7  582.16  4973.7  582.35  4983.7  581.73
  4990.3   579.1  4991.8   576.1  5008.1   576.1  5009.6   579.1    5021  580.06
    5041  583.59    5061  584.88    5111  590.37    5131  593.08    5141   594.8
    5171  597.83
#Mann= 3 , 1 , 0
 4723.70    0.14       0  4990.3    0.04       0  5009.6    0.14       0
Bank Sta=4990.30,5009.60
Exp/Cntr=0.3,0.1

Type RM Length L Ch R = 1 ,25716.7,303.4,303.4,303.4
XS GIS Cut Line= 3
 1946756.1752856 842013.52699582 1946856.8982654  841738.2175177
 1946867.7528312 841669.01966060
BEGIN DESCRIPTION:
Sevenmile Creek 52.0
END DESCRIPTION:
#Sta/Elev= 24
  4697.2  598.66  4727.2  596.35  4747.2  595.32  4797.2  589.93  4807.2  588.27
  4817.2  586.94  4827.2  586.17  4847.2  584.03  4867.2  580.23  4877.2  580.28
  4887.2   581.6  4907.2  582.48  4917.2  582.44  4977.2  580.39  4987.2   579.4
  4990.3  577.18  4990.4  577.11  4991.9  574.11  5008.1  574.11  5009.6  577.11
  5010.4  586.75  5020.4  591.09  5040.4  596.87  5060.4  601.18
#Mann= 3 , 1 , 0
 4697.20    0.14       0  4990.3    0.04       0  5009.6    0.14       0
Bank Sta=4990.30,5009.60
Exp/Cntr=0.3,0.1

Type RM Length L Ch R = 1 ,25413.3,858,858,858
XS GIS Cut Line= 3
 1946943.6693356 842311.80232629 1947143.2291214 841806.59503556
 1947184.8189211 841672.91353680
BEGIN DESCRIPTION:
Sevenmile Creek 50.0
END DESCRIPTION:
#Sta/Elev= 30
  4459.2  597.61  4479.2  597.12  4519.2   593.5  4539.2  592.33  4559.2  592.03
  4569.2  591.01  4579.2  588.97  4619.2  586.24  4659.2  585.03  4739.2  584.39
  4749.2  583.79  4769.2  583.44  4789.2  581.86  4829.2   579.7  4839.2  580.12
  4859.2  579.46  4889.2   580.2  4969.2  580.42  4989.2  578.23  4990.4  576.23
  4991.9  573.23  5008.1  573.23  5009.6  576.23  5012.4  580.67  5052.4  584.92
  5082.4  588.88  5102.4   590.7  5112.4   592.2  5122.4  594.33  5142.4  599.74
#Mann= 3 , 1 , 0
 4459.20    0.11       0  4990.4   0.045       0  5009.6    0.14       0
Bank Sta=4990.40,5009.60
Exp/Cntr=0.3,0.1

Type RM Length L Ch R = 1 ,24555.3,423.6,423.6,423.6
XS GIS Cut Line= 3
 1947520.5232908 842546.30058066 1947591.3411848 842344.62353487
 1947661.3597630 842171.76516971
BEGIN DESCRIPTION:
Sevenmile Creek 49.0
END DESCRIPTION:
#Sta/Elev= 21
  4782.4  597.92  4812.4  595.28  4882.4  592.34  4902.4  590.89  4922.4  588.68
  4952.4   582.1  4962.4  580.29  4972.4  578.96  4990.4  575.33  4991.9  572.33
  5008.2  572.33  5009.7  575.33  5016.2  576.69  5026.2  578.57  5036.2  579.55
  5056.2   579.5  5066.2  580.17  5086.2     583  5116.2  588.11  5126.2  589.12
  5182.7  596.32
#Mann= 3 , 1 , 0
 4782.40    0.11       0  4990.4   0.045       0  5009.7    0.14       0
Bank Sta=4990.40,5009.70
Exp/Cntr=0.3,0.1

Type RM Length L Ch R = 1 ,24131.7,382.8,382.8,382.8
XS GIS Cut Line= 3
 1947880.1678202 842769.11116576 1947978.6314459 842506.54149716
 1948035.0988628 842346.24689442
BEGIN DESCRIPTION:
Sevenmile Creek 48.0
END DESCRIPTION:
#Sta/Elev= 24
  4718.5  599.81  4788.5  594.69  4808.5   593.8  4858.5  587.91  4898.5  581.86
  4908.5  580.71  4918.5  580.39  4928.5  580.44  4978.5  578.92  4988.5  578.25
  4990.4  574.78  4991.9  571.78  5008.1  571.78  5009.6  574.78  5028.9  578.68
  5048.9  578.54  5058.9  577.47  5068.9  578.08  5078.9  579.35  5108.9  586.06
  5118.9  587.97  5128.9  590.89  5148.9  594.07  5168.9  598.05
#Mann= 3 , 1 , 0
 4718.50    0.11       0  4990.4   0.045       0  5009.6    0.14       0
Bank Sta=4990.40,5009.60
Exp/Cntr=0.3,0.1

Type RM Length L Ch R = 1 ,23748.9,748.9,748.9,748.9
XS GIS Cut Line= 3
 1948147.1136499 843020.74043149 1948306.8435317 842594.06472003
 1948401.8241312 842362.80760810
BEGIN DESCRIPTION:
Sevenmile Creek 47.0
END DESCRIPTION:
#Sta/Elev= 28
  4554.7  592.12  4564.7  591.58  4584.7  591.03  4594.7   590.4  4634.7  589.94
  4694.7  590.71  4814.7  588.99  4914.7  583.59  4934.7  581.33  4944.7  580.49
  4954.7  579.11  4964.7  577.27  4974.7  576.36  4990.4  574.28  4991.9  571.28
  5008.1  571.28  5009.6  574.28  5010.3   577.3  5020.3  578.11  5030.3  577.76
  5040.3  577.98  5060.3  578.96  5130.3  580.47  5160.3  583.37  5210.3  589.61
  5220.3  591.22  5230.3  592.45  5260.3  595.36
#Mann= 3 , 1 , 0
 4554.70    0.11       0  4990.4   0.045       0  5009.6    0.14       0
Bank Sta=4990.40,5009.60
Exp/Cntr=0.3,0.1