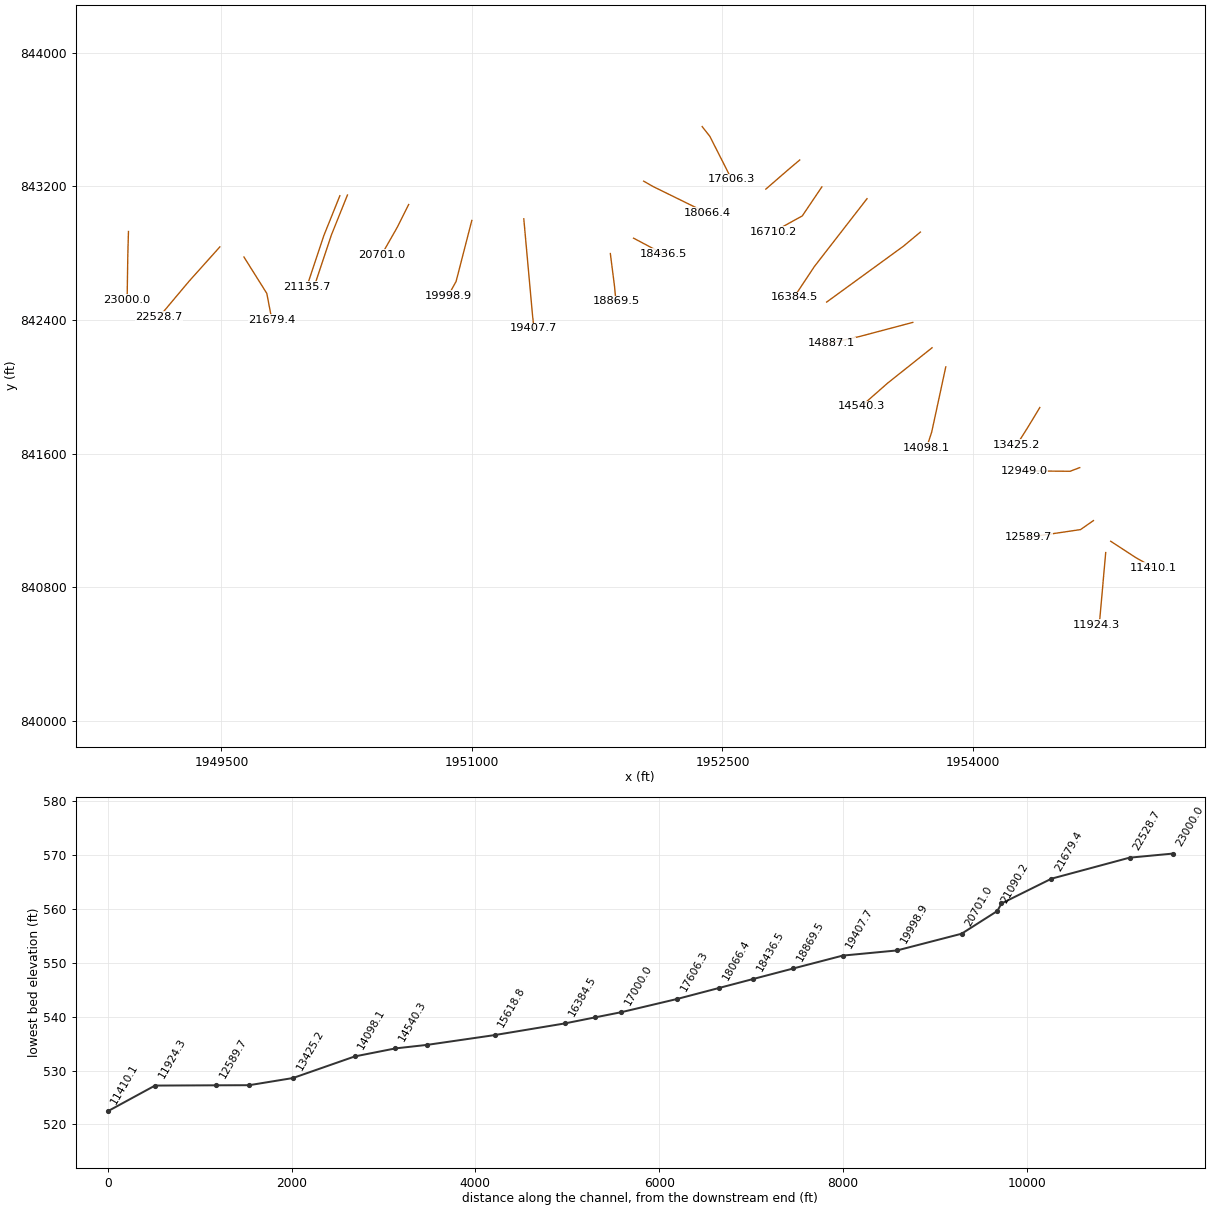
HEC-RAS study Sevenmile_Creek_FINAL.prj: Sevenmile Creek

--- Sevenmile_Creek_FINAL.g01 (geometry) --- (continued)

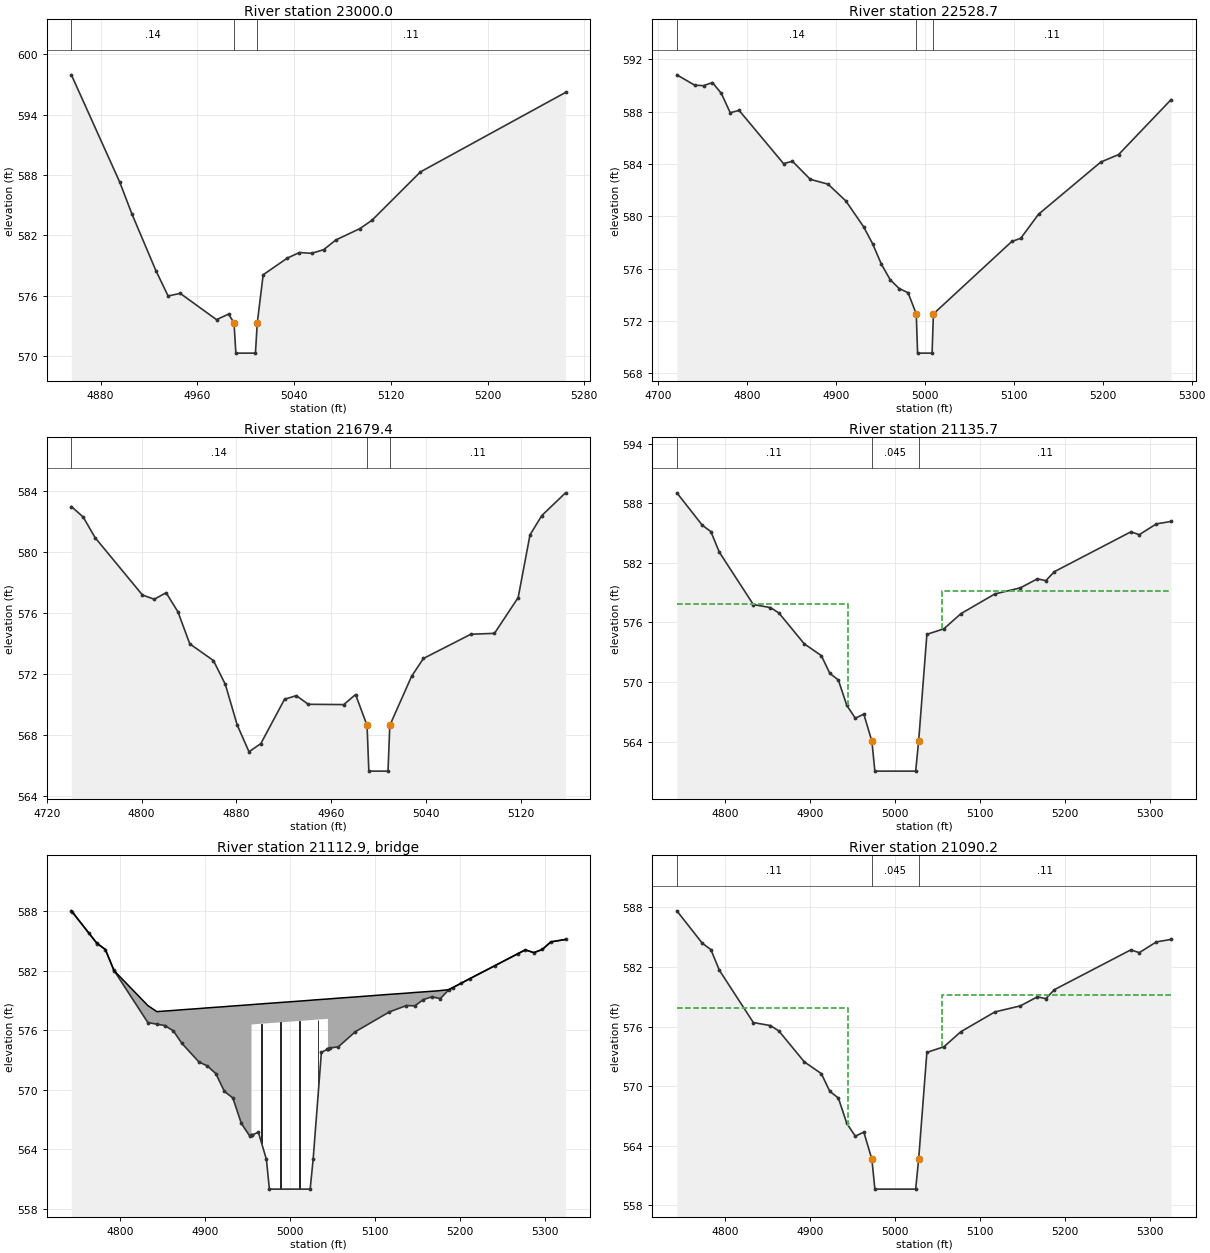
Type RM Length L Ch R = 1 ,23000.0,471.3,471.3,471.3
XS GIS Cut Line= 3
  1948943.011153 842929.50684973 1948939.1988169 842790.99197147
 1948934.9131239 842520.99331444
BEGIN DESCRIPTION:
Sevenmile Creek 46.0
END DESCRIPTION:
#Sta/Elev= 22
  4855.9  597.95  4895.9  587.28  4905.9  584.14  4925.9  578.46  4935.9  575.97
  4945.9  576.23  4975.9  573.62  4985.9  574.17  4990.4  573.29  4991.9  570.29
  5008.1  570.29  5009.6  573.29  5014.5  578.08  5034.5  579.74  5044.5  580.29
  5054.5  580.21  5064.5  580.57  5074.5  581.53  5094.5  582.67  5104.5   583.5
  5144.5   588.3  5264.5   596.2
#Mann= 3 , 1 , 0
 4855.90    0.14       0  4990.4   0.045       0  5009.6    0.11       0
Bank Sta=4990.40,5009.60
Exp/Cntr=0.3,0.1

Type RM Length L Ch R = 1 ,22528.7,849.3,849.3,849.3
XS GIS Cut Line= 3
 1949490.4027254 842837.40359640 1949305.6681238 842631.39884478
 1949126.1771395 842417.71910146
BEGIN DESCRIPTION:
Sevenmile Creek 45.0
END DESCRIPTION:
#Sta/Elev= 28
  4721.1  590.81  4741.1  590.02  4751.1  589.98  4761.1  590.22  4771.1  589.39
  4781.1  587.91  4791.1  588.09  4841.1  584.02  4851.1   584.2  4871.1  582.82
  4891.1  582.45  4911.1  581.17  4931.1  579.19  4941.1  577.91  4951.1  576.33
  4961.1  575.13  4971.1  574.47  4981.1  574.15  4990.3  572.53  4991.8  569.53
  5008.1  569.53  5009.6  572.53  5097.8  578.07  5107.8  578.31  5127.8  580.15
  5197.8  584.14  5217.8  584.71  5276.8  588.91
#Mann= 3 , 1 , 0
 4721.10    0.14       0  4990.3   0.045       0  5009.6    0.11       0
Bank Sta=4990.30,5009.60
Exp/Cntr=0.3,0.1

Type RM Length L Ch R = 1 ,21679.4,543.75,543.75,543.75
XS GIS Cut Line= 3
 1949634.7349286 842776.70107024 1949771.4899643 842558.74773205
 1949801.7082956 842401.61240934
BEGIN DESCRIPTION:
Sevenmile Creek 43.0
END DESCRIPTION:
#Sta/Elev= 30
  4740.7  583.01  4750.7  582.32  4760.7  580.97  4800.7   577.2  4810.7  576.92
  4820.7  577.35  4830.7  576.09  4840.7  573.99  4860.7  572.89  4870.7  571.33
  4880.7  568.67  4890.7   566.9  4900.7  567.44  4920.7  570.35  4930.7  570.59
  4940.7  570.02  4970.7     570  4980.7  570.66  4990.4  568.63  4991.9  565.63
  5008.1  565.63  5009.6  568.63    5028  571.86    5038  573.03    5078  574.62
    5098  574.68    5118  577.03    5128  581.15    5138  582.42    5158  583.91
#Mann= 3 , 1 , 0
 4740.70    0.14       0  4990.4   0.045       0  5009.6    0.11       0
Bank Sta=4990.40,5009.60
Exp/Cntr=0.5,0.3

Type RM Length L Ch R = 1 ,21135.7,45.5,45.5,45.5
XS GIS Cut Line= 3
 1950208.9864722 843143.80080753 1950112.7367389 842904.15861439
 1950010.6916133 842598.02323782
BEGIN DESCRIPTION:
Upstream Section of Bridge/Culvert/Weir
END DESCRIPTION:
#Sta/Elev= 30
    4743  589.05    4773  585.78    4783  585.15    4793  583.07    4833   577.8
    4853   577.5    4863  576.96    4893  573.84    4913  572.66    4923  570.87
    4933  570.21    4943  567.64    4953  566.36    4963  566.77  4972.5  564.03
    4976  561.03    5024  561.03  5027.5  564.03  5037.2   574.8  5057.2  575.36
  5077.2  576.88  5117.2  578.87  5147.2  579.48  5167.2  580.39  5177.2  580.21
  5187.2  581.11  5277.2  585.12  5287.2  584.84  5307.2  585.92  5324.5  586.17
#Mann= 3 , 1 , 0
 4743.00    0.11       0  4972.5   0.045       0  5027.5    0.11       0
#XS Ineff= 2 , 0
       0 4944.85  577.88 5055.05       0  579.21
Bank Sta=4972.50,5027.50
Exp/Cntr=0.5,0.3

Type RM Length L Ch R = 3 ,21112.9,,,
BEGIN DESCRIPTION:
Mt Willing Road-TOR
Structure ID: Mt Willing Road (SC)-Bridge
Approximate Survey Structure
END DESCRIPTION:
Bridge Culvert--1,0,-1,-1, 0
Deck Dist Width WeirC Skew NumUp NumDn MinLoCord MaxHiCord MaxSubmerge Is_Ogee
10,25.5,2.6,,52,52,,,0.95,0,1,1,,
    4743  4743.6  4763.6    4773  4773.6    4783    4793  4793.6    4833  4843.6
    4853    4863    4873    4893    4903    4913    4923    4933    4943    4953
 4954.91    4955  4955.8    4963  4972.5    4976    5024  5027.5  5037.2  5044.3
 5044.89    5045  5047.2  5057.2  5077.2  5117.2  5137.2  5147.2  5157.2  5167.2
  5177.2  5187.2  5191.8  5201.8  5211.8  5241.8  5268.9  5277.2  5287.2  5297.2
  5307.2  5324.5
  588.02  587.96  585.78  584.76  584.72  584.13  582.05  581.97  578.48  577.87
  577.93  577.99  578.06  578.18  578.25  578.31  578.37  578.44   578.5  578.56
  578.58  578.58  578.58  578.63  578.69  578.71  579.01  579.04   579.1  579.14
  579.15  579.15  579.16  579.23  579.35  579.61  579.73   579.8  579.86  579.92
  579.99  580.09  580.29  580.74  581.19  582.52  583.73  584.09  583.81  584.13
  584.89  585.14
  588.02  587.95  585.77  584.75  584.71  584.12  582.04  581.96  576.77  576.61
  576.47  575.93  574.68  572.81   572.4  571.63  569.84  569.18  566.61  565.33
  565.41  576.58  576.58  576.63  576.69  576.71  577.01  577.04   577.1  577.14
  577.15  574.11  574.21  574.33  575.85  577.84  578.48  578.45  579.08  579.36
  579.18  580.08  580.28  580.73  581.18  582.51  583.72  584.09  583.81  584.13
  584.89  585.14
    4743  4743.6  4763.6    4773  4773.6    4783    4793  4793.6    4833  4843.6
    4853    4863    4873    4893    4903    4913    4923    4933    4943    4953
 4954.91    4955  4955.8    4963  4972.5    4976    5024  5027.5  5037.2  5044.3
 5044.89    5045  5047.2  5057.2  5077.2  5117.2  5137.2  5147.2  5157.2  5167.2
  5177.2  5187.2  5191.8  5201.8  5211.8  5241.8  5268.9  5277.2  5287.2  5297.2
  5307.2  5324.5
  588.02  587.96  585.78  584.76  584.72  584.13  582.05  581.97  578.48  577.87
  577.93  577.99  578.06  578.18  578.25  578.31  578.37  578.44   578.5  578.56
  578.58  578.58  578.58  578.63  578.69  578.71  579.01  579.04   579.1  579.14
  579.15  579.15  579.16  579.23  579.35  579.61  579.73   579.8  579.86  579.92
  579.99  580.09  580.29  580.74  581.19  582.52  583.73  584.09  583.81  584.13
  584.89  585.14
  587.77   587.7  585.52   584.5  584.46  583.87  581.79  581.71  576.52  576.36
  576.22  575.68  574.43  572.56  572.15  571.38  569.59  568.93  566.36  565.08
  565.16  576.33  576.33  576.38  576.44  576.46  576.76  576.79  576.85  576.89
   576.9  573.86  573.96  574.08   575.6  577.59  578.23   578.2  578.83  579.11
  578.93  579.83  580.03  580.48  580.93  582.26  583.47  583.84  583.56  583.88
  584.64  584.89
Pier Skew, UpSta & Num, DnSta & Num=,4966.9, 2 ,4966.9, 2 , 0 , 0 , 0 ,,
       1       1
  563.47  577.66
       1       1
  563.22  577.41
Pier Skew, UpSta & Num, DnSta & Num=,4989.0, 2 ,4989.0, 2 , 0 , 0 , 0 ,,
       1       1
     559  577.79
       1       1
  558.75  577.54
Pier Skew, UpSta & Num, DnSta & Num=,5011.1, 2 ,5011.1, 2 , 0 , 0 , 0 ,,
       1       1
     559  577.93
       1       1
  558.75  577.68
Pier Skew, UpSta & Num, DnSta & Num=,5033.2, 2 ,5033.2, 2 , 0 , 0 , 0 ,,
       1       1
  567.77  578.08
       1       1
  567.52  577.83
Abutment Skew #Up #Dn=, 2 , 2
 4954.80 4955.80
  576.58  565.44
 4954.80 4955.80
  576.33  565.19
BR Coef= 1 , 1 , 0 ,1.25, 0 ,,,0.8,0,2,0,
Wspro=,,,, 1 ,,,, 0 ,,,, 0 ,,,,-1 ,-1 ,-1 , 0 , 0 , 0 , 0 , 0
BC Design=,, 0 ,, 0 ,,,,,,
BR U #Sta/Elev= 52
    4743  588.02  4743.6  587.95  4763.6  585.77    4773  584.75  4773.6  584.71
    4783  584.12    4793  582.04  4793.6  581.96    4833  576.77  4843.6  576.61
    4853  576.47    4863  575.93    4873  574.68    4893  572.81    4903   572.4
    4913  571.63    4923  569.84    4933  569.18    4943  566.61    4953  565.33
 4954.91  565.41    4955  565.41  4955.8  565.44    4963  565.74  4972.5     563
    4976     560    5024     560  5027.5     563  5037.2  573.77  5044.3  574.08
 5044.89  574.11    5045  574.11  5047.2  574.21  5057.2  574.33  5077.2  575.85
  5117.2  577.84  5137.2  578.48  5147.2  578.45  5157.2  579.08  5167.2  579.36
  5177.2  579.18  5187.2  580.08  5191.8  580.28  5201.8  580.73  5211.8  581.18
  5241.8  582.51  5268.9  583.72  5277.2  584.09  5287.2  583.81  5297.2  584.13
  5307.2  584.89  5324.5  585.14
BR U #Mann= 3
 4743.00    0.11  4972.5   0.045  5027.5    0.11
BR U Banks=4972.50,5027.50
BR D #Sta/Elev= 52
    4743  587.77  4743.6   587.7  4763.6  585.52    4773   584.5  4773.6  584.46
    4783  583.87    4793  581.79  4793.6  581.71    4833  576.52  4843.6  576.36
    4853  576.22    4863  575.68    4873  574.43    4893  572.56    4903  572.15
    4913  571.38    4923  569.59    4933  568.93    4943  566.36    4953  565.08
 4954.91  565.16    4955  565.16  4955.8  565.19    4963  565.49  4972.5  562.75
    4976  559.75    5024  559.75  5027.5  562.75  5037.2  573.52  5044.3  573.83
 5044.89  573.86    5045  573.86  5047.2  573.96  5057.2  574.08  5077.2   575.6
  5117.2  577.59  5137.2  578.23  5147.2   578.2  5157.2  578.83  5167.2  579.11
  5177.2  578.93  5187.2  579.83  5191.8  580.03  5201.8  580.48  5211.8  580.93
  5241.8  582.26  5268.9  583.47  5277.2  583.84  5287.2  583.56  5297.2  583.88
  5307.2  584.64  5324.5  584.89
BR D #Mann= 3
 4743.00    0.11  4972.5   0.045  5027.5    0.11
BR D Banks=4972.50,5027.50

Type RM Length L Ch R = 1 ,21090.2,389.15,389.15,389.15
XS GIS Cut Line= 3
 1950254.3122707 843147.77849316 1950158.0625374 842908.13630002
 1950056.0174119 842602.00092346
BEGIN DESCRIPTION:
Downstream Section of Bridge/Culvert/Weir
END DESCRIPTION:
#Sta/Elev= 30
    4743  587.65    4773  584.38    4783  583.75    4793  581.67    4833   576.4
    4853   576.1    4863  575.56    4893  572.44    4913  571.26    4923  569.47
    4933  568.81    4943  566.24    4953  564.96    4963  565.37  4972.5  562.63
    4976  559.63    5024  559.63  5027.5  562.63  5037.2   573.4  5057.2  573.96
  5077.2  575.48  5117.2  577.47  5147.2  578.08  5167.2  578.99  5177.2  578.81
  5187.2  579.71  5277.2  583.72  5287.2  583.44  5307.2  584.52  5324.5  584.77
#Mann= 3 , 1 , 0
 4743.00    0.11       0  4972.5   0.045       0  5027.5    0.11       0
#XS Ineff= 2 , 0
       0 4944.85  577.88 5055.05       0  579.21
Bank Sta=4972.50,5027.50
Exp/Cntr=0.5,0.3

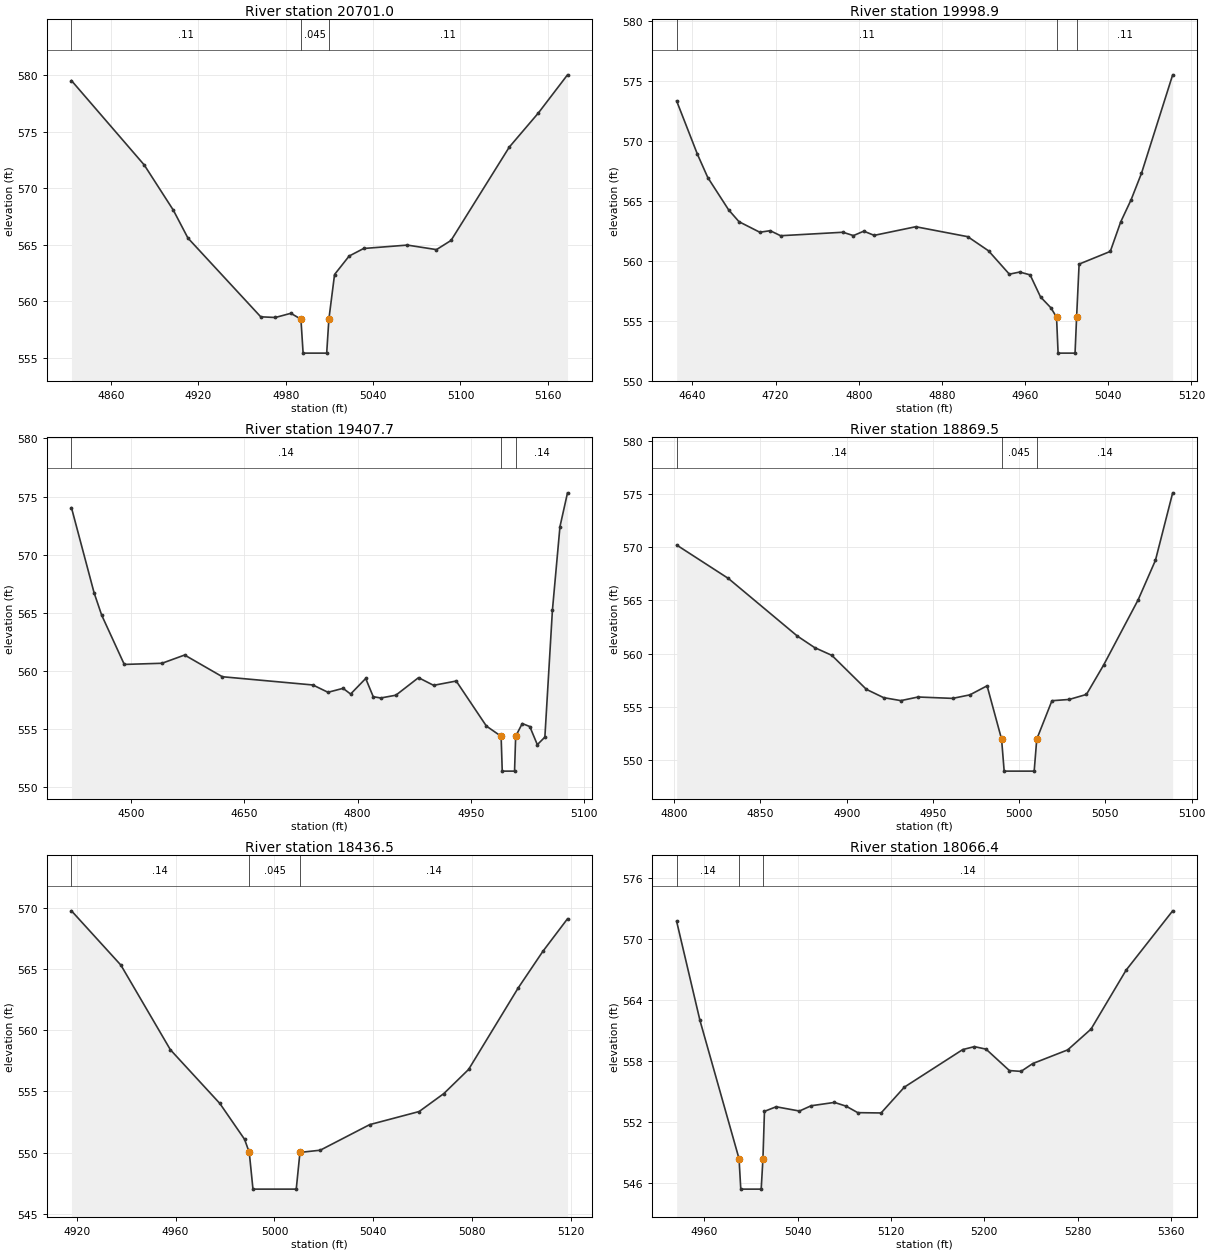
Type RM Length L Ch R = 1 ,20701.0,702.1,702.1,702.1
XS GIS Cut Line= 3
 1950620.9380182 843090.95244130 1950553.5578248 842956.19205463
 1950459.4183393 842791.11505693
BEGIN DESCRIPTION:
Sevenmile Creek 41.0
END DESCRIPTION:
#Sta/Elev= 20
  4832.8   579.5  4882.8  572.04  4902.8  568.04  4912.8  565.58  4962.8  558.62
  4972.8  558.56  4983.5  558.93  4990.4  558.41  4991.9  555.41  5008.1  555.41
  5009.6  558.41  5013.5  562.36  5023.5  563.99  5033.5  564.66  5063.5  564.96
  5083.5  564.56  5093.5  565.37  5133.5  573.62  5153.5  576.64  5173.5  580.01
#Mann= 3 , 1 , 0
 4832.80    0.11       0  4990.4   0.045       0  5009.6    0.11       0
Bank Sta=4990.40,5009.60
Exp/Cntr=0.3,0.1

Type RM Length L Ch R = 1 ,19998.9,591.2,591.2,591.2
XS GIS Cut Line= 3
 1950999.0860566 842995.55639702 1950905.0250064 842630.36517266
 1950856.3892196 842543.00088893
BEGIN DESCRIPTION:
Sevenmile Creek 40.0
END DESCRIPTION:
#Sta/Elev= 30
  4624.9  573.36  4644.9  568.91  4654.9  566.96  4674.9  564.27  4684.9  563.28
  4704.9   562.4  4714.9  562.53  4724.9  562.11  4784.9   562.4  4794.9  562.12
  4804.9  562.49  4814.9  562.14  4854.9  562.86  4904.9  562.03  4924.9  560.85
  4944.9   558.9  4954.9  559.08  4964.9  558.84  4974.9     557  4984.9  556.09
  4990.3  555.31  4991.8  552.31  5008.1  552.31  5009.6  555.31    5012  559.74
    5042   560.8    5052  563.26    5062  565.11    5072  567.32    5102  575.54
#Mann= 3 , 1 , 0
 4624.90    0.11       0  4990.3   0.045       0  5009.6    0.11       0
Bank Sta=4990.30,5009.60
Exp/Cntr=0.3,0.1

Type RM Length L Ch R = 1 ,19407.7,538.2,538.2,538.2
XS GIS Cut Line= 3
 1951310.4334127 843005.70043344 1951362.5075860 842430.51751947
 1951370.9273633 842350.99740039
BEGIN DESCRIPTION:
Sevenmile Creek 39.0
END DESCRIPTION:
#Sta/Elev= 30
  4420.8  574.04  4450.8  566.71  4460.8  564.79  4490.8  560.54  4540.8  560.64
  4570.8  561.35  4620.8  559.48  4740.8  558.77  4760.8  558.14  4780.8  558.48
  4790.8  557.99  4810.8  559.33  4820.8  557.76  4830.8  557.65  4850.8  557.89
  4880.8   559.4  4900.8  558.74  4930.8  559.11  4970.8  555.23  4990.3  554.35
  4991.8  551.35  5008.1  551.35  5009.6  554.35  5018.3  555.45  5028.3  555.19
  5038.3  553.63  5048.3  554.28  5058.3  565.21  5068.3  572.41  5078.3  575.32
#Mann= 3 , 1 , 0
 4420.80    0.14       0  4990.3   0.045       0  5009.6    0.14       0
Bank Sta=4990.30,5009.60
Exp/Cntr=0.3,0.1

Type RM Length L Ch R = 1 ,18869.5,433,433,433
XS GIS Cut Line= 3
 1951828.7230625 842797.43978816 1951853.6994083 842601.47153605
 1951862.4853764 842511.85466126
BEGIN DESCRIPTION:
Sevenmile Creek 38.0
END DESCRIPTION:
#Sta/Elev= 23
  4801.4  570.19  4831.4  567.05  4871.4  561.64  4881.4  560.56  4891.4  559.83
  4911.4  556.64  4921.4  555.86  4931.4  555.58  4941.4  555.92  4961.4  555.79
  4971.4  556.12  4981.4  556.97  4989.8  551.96  4991.3  548.96  5008.7  548.96
  5010.2  551.96    5019  555.57    5029  555.69    5039  556.16    5049  558.93
    5069  565.05    5079  568.75    5089  575.09
#Mann= 3 , 1 , 0
 4801.40    0.14       0  4989.8   0.045       0  5010.2    0.14       0
Bank Sta=4989.80,5010.20
Exp/Cntr=0.3,0.1

Type RM Length L Ch R = 1 ,18436.5,370.1,370.1,370.1
XS GIS Cut Line= 3
 1951967.8387665 842889.54983386 1952039.1002432  842851.8830533
 1952144.9507172 842795.36095555
BEGIN DESCRIPTION:
Sevenmile Creek 37.0
END DESCRIPTION:
#Sta/Elev= 17
  4917.9  569.76  4937.9  565.32  4957.9  558.41  4977.9  554.02  4987.9  551.09
  4989.8  550.02  4991.3  547.02  5008.8  547.02  5010.3  550.02  5018.5   550.2
  5038.5  552.29  5058.5  553.36  5068.5  554.83  5078.5   556.8  5098.5  563.44
  5108.5  566.44  5118.5  569.11
#Mann= 3 , 1 , 0
 4917.90    0.14       0  4989.8   0.045       0  5010.3    0.14       0
Bank Sta=4989.80,5010.30
Exp/Cntr=0.3,0.1

Type RM Length L Ch R = 1 ,18066.4,460.1,460.1,460.1
XS GIS Cut Line= 3
 1952028.1167912 843231.02481255 1952084.8485012 843198.60669257
 1952408.0314062 843040.10297482
BEGIN DESCRIPTION:
Sevenmile Creek 36.0
END DESCRIPTION:
#Sta/Elev= 25
  4936.2  571.76  4956.2  561.99  4989.7  548.36  4991.2  545.36  5008.7  545.36
  5010.2  548.36  5011.5  553.03  5021.5  553.48  5041.5  553.06  5051.5  553.58
  5071.5  553.91  5081.5  553.54  5091.5   552.9  5111.5  552.87  5131.5  555.42
  5181.5  559.12  5191.5  559.41  5201.5  559.16  5221.5  557.05  5231.5  556.97
  5241.5  557.74  5271.5  559.09  5291.5  561.14  5321.5  566.94  5361.5   572.8
#Mann= 3 , 1 , 0
 4936.20    0.14       0  4989.7   0.045       0  5010.2    0.14       0
Bank Sta=4989.70,5010.20
Exp/Cntr=0.3,0.1

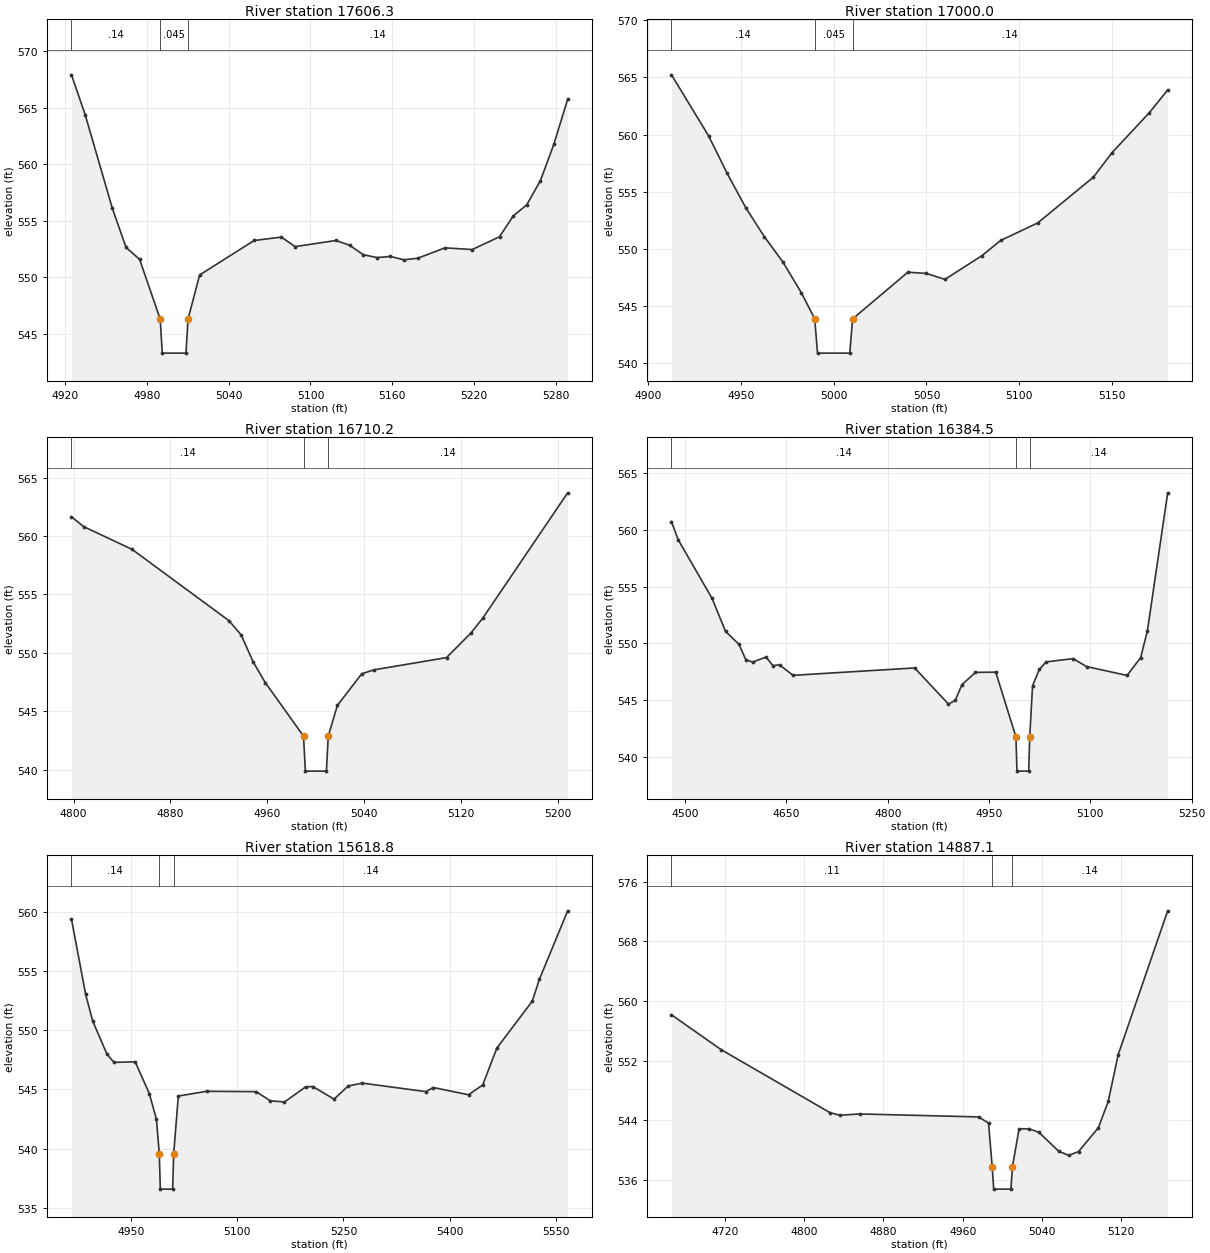
Type RM Length L Ch R = 1 ,17606.3,606.3,606.3,606.3
XS GIS Cut Line= 3
 1952378.5799454 843557.72080186 1952424.3487313 843499.58207388
 1952555.6329004 843240.99204374
BEGIN DESCRIPTION:
Sevenmile Creek 35.0
END DESCRIPTION:
#Sta/Elev= 28
  4924.7  567.91  4934.7   564.4  4954.7   556.1  4964.7  552.65  4974.7  551.59
  4989.8   546.3  4991.3   543.3  5008.7   543.3  5010.2   546.3  5018.7  550.21
  5058.7  553.26  5078.7  553.56  5088.7  552.72  5118.7  553.26  5128.7  552.84
  5138.7  552.01  5148.7  551.75  5158.7  551.85  5168.7  551.55  5178.7  551.69
  5198.7  552.61  5218.7  552.46  5238.7  553.59  5248.7  555.42  5258.7  556.42
  5268.7  558.55  5278.7  561.82  5288.7  565.76
#Mann= 3 , 1 , 0
 4924.70    0.14       0  4989.8   0.045       0  5010.2    0.14       0
Bank Sta=4989.80,5010.20
Exp/Cntr=0.3,0.1

Type RM Length L Ch R = 1 ,17000.0,289.8,289.8,289.8
XS GIS Cut Line= 3
 1952962.7916968 843357.64074422 1952895.9824257 843301.28961018
 1952759.9730414 843183.38668690
BEGIN DESCRIPTION:
Sevenmile Creek 34.0
END DESCRIPTION:
#Sta/Elev= 21
  4912.6  565.23  4932.6  559.89  4942.6   556.6  4952.6   553.6  4962.6  551.06
  4972.6  548.84  4982.6  546.14  4989.8  543.85  4991.3  540.85  5008.7  540.85
  5010.2  543.85    5040  547.94    5050  547.83    5060  547.31    5080   549.4
    5090  550.72    5110  552.26    5140  556.27    5150  558.41    5170  561.89
    5180   563.9
#Mann= 3 , 1 , 0
 4912.60    0.14       0  4989.8   0.045       0  5010.2    0.14       0
Bank Sta=4989.80,5010.20
Exp/Cntr=0.3,0.1

Type RM Length L Ch R = 1 ,16710.2,325.7,325.7,325.7
XS GIS Cut Line= 3
 1953095.2792476 843196.52120889 1952978.1434329 843022.83706989
 1952803.0414962 842926.18080083
BEGIN DESCRIPTION:
Sevenmile Creek 33.0
END DESCRIPTION:
#Sta/Elev= 18
  4798.3  561.65  4808.3  560.81  4848.3  558.86  4928.3  552.75  4938.3  551.54
  4948.3  549.21  4958.3  547.44  4989.8  542.87  4991.3  539.87  5008.7  539.87
  5010.2  542.87  5017.8  545.51  5037.8   548.2  5047.8  548.54  5107.8  549.59
  5127.8  551.68  5137.8  552.98  5207.8   563.7
#Mann= 3 , 1 , 0
 4798.30    0.14       0  4989.8   0.045       0  5010.2    0.14       0
Bank Sta=4989.80,5010.20
Exp/Cntr=0.3,0.1

Type RM Length L Ch R = 1 ,16384.5,765.7,765.7,765.7
XS GIS Cut Line= 3
 1953365.7925353 843125.95130598 1953050.3775244 842719.45388553
 1952928.7371943 842536.16023746
BEGIN DESCRIPTION:
Sevenmile Creek 32.0
END DESCRIPTION:
#Sta/Elev= 30
  4479.9  560.72  4489.9  559.11  4539.9  553.97  4559.9  551.06  4579.9  549.91
  4589.9  548.57  4599.9  548.35  4619.9   548.8  4629.9  548.05  4639.9  548.11
  4659.9  547.19  4839.9  547.84  4889.9  544.66  4899.9  544.98  4909.9  546.37
  4929.9  547.45  4959.9  547.47  4989.8  541.76  4991.3  538.76  5008.7  538.76
  5010.2  541.76  5014.4  546.28  5024.4  547.71  5034.4  548.37  5074.4  548.66
  5094.4  547.96  5154.4  547.18  5174.4  548.75  5184.4  551.11  5214.4  563.25
#Mann= 3 , 1 , 0
 4479.90    0.14       0  4989.8   0.045       0  5010.2    0.14       0
Bank Sta=4989.80,5010.20
Exp/Cntr=0.3,0.1

Type RM Length L Ch R = 1 ,15618.8,731.7,731.7,731.7
XS GIS Cut Line= 3
 1953685.4859995 842926.06533934 1953584.9098016  842842.2518411
 1953124.0457911 842506.87060573
BEGIN DESCRIPTION:
Sevenmile Creek 31.0
END DESCRIPTION:
#Sta/Elev= 30
  4865.8  559.37  4885.8  553.02  4895.8  550.76  4915.8  547.99  4925.8  547.28
  4955.8  547.33  4975.8  544.64  4985.8  542.48  4989.8  539.59  4991.3  536.59
  5008.7  536.59  5010.2  539.59  5016.7  544.44  5056.7  544.84  5126.7  544.81
  5146.7  544.04  5166.7  543.94  5196.7  545.22  5206.7  545.24  5236.7  544.18
  5256.7  545.29  5276.7  545.53  5366.7  544.81  5376.7  545.16  5426.7  544.55
  5446.7  545.37  5466.7  548.49  5516.7  552.44  5526.7  554.28  5566.7  560.06
#Mann= 3 , 1 , 0
 4865.80    0.14       0  4989.8   0.045       0  5010.2    0.14       0
Bank Sta=4989.80,5010.20
Exp/Cntr=0.3,0.1

Type RM Length L Ch R = 1 ,14887.1,346.8,346.8,346.8
XS GIS Cut Line= 3
 1953639.8455857 842385.19838102 1953320.0514661 842300.49615474
 1953154.1204786 842263.62260197
BEGIN DESCRIPTION:
Sevenmile Creek 30.0
END DESCRIPTION:
#Sta/Elev= 21
  4666.1  558.15  4716.1  553.49  4826.1  545.03  4836.1  544.69  4856.1  544.86
  4976.1  544.46  4986.1  543.63  4989.8  537.78  4991.3  534.78  5008.7  534.78
  5010.2  537.78  5016.9  542.84  5026.9  542.87  5036.9   542.4  5056.9  539.86
  5066.9  539.31  5076.9  539.81  5096.9     543  5106.9  546.53  5116.9  552.79
  5166.9  572.09
#Mann= 3 , 1 , 0
 4666.10    0.11       0  4989.8    0.05       0  5010.2    0.14       0
Bank Sta=4989.80,5010.20
Exp/Cntr=0.3,0.1

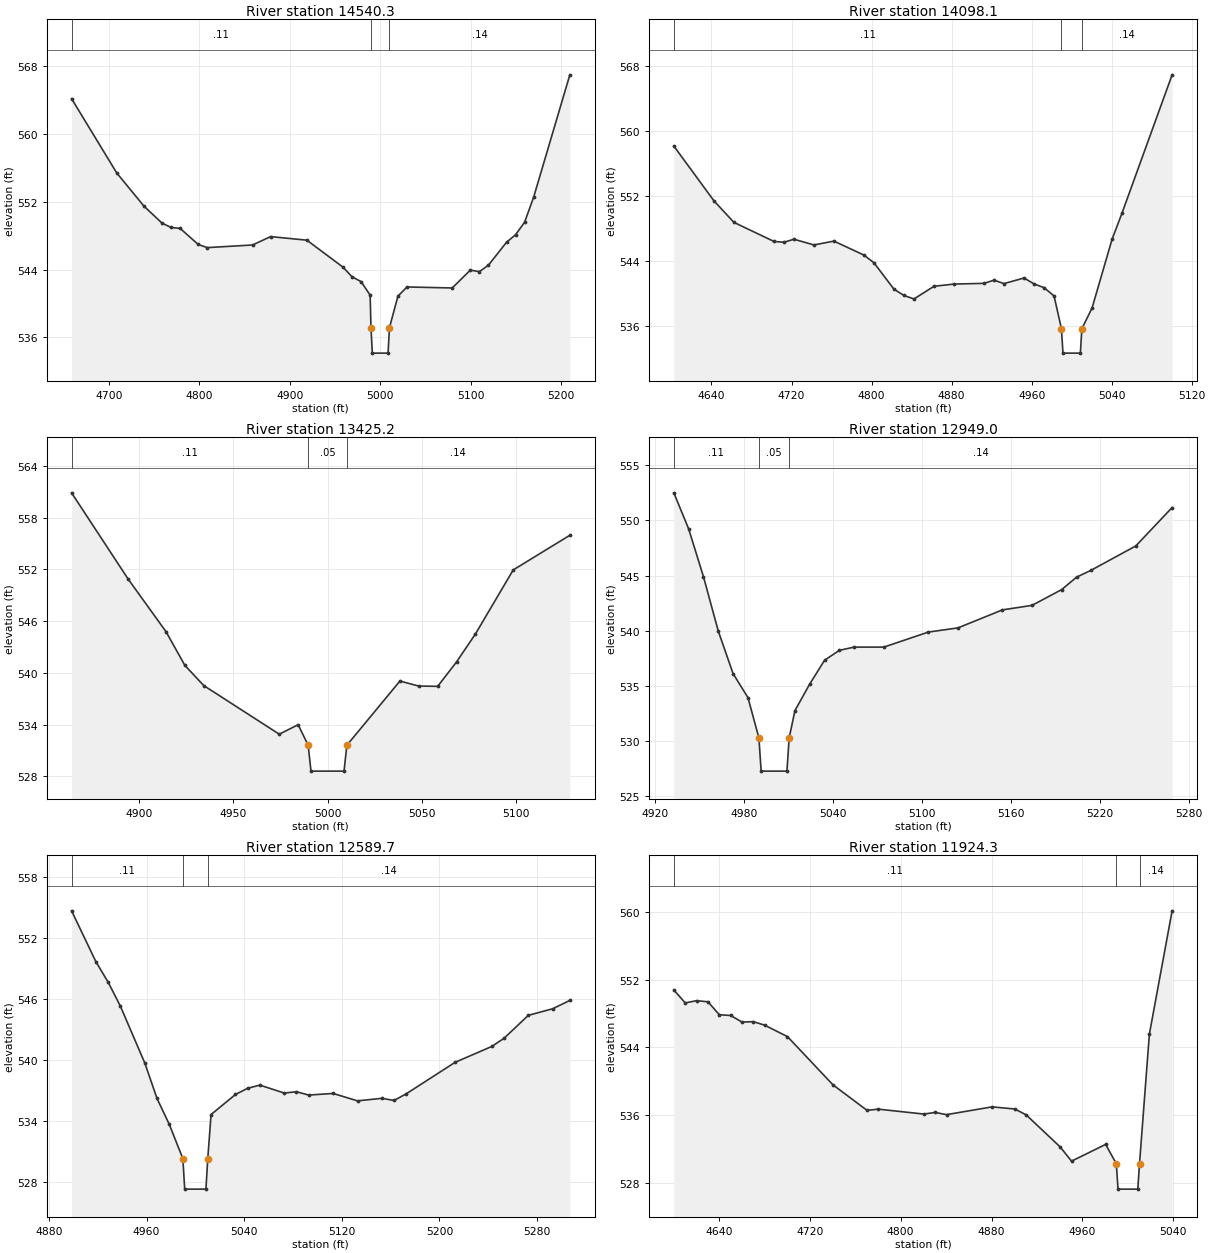
Type RM Length L Ch R = 1 ,14540.3,442.2,442.2,442.2
XS GIS Cut Line= 3
 1953755.2721548 842233.27070163 1953488.5976796 842021.19100088
 1953330.9661127 841882.47522198
BEGIN DESCRIPTION:
Sevenmile Creek 29.0
END DESCRIPTION:
#Sta/Elev= 30
  4658.9  564.19  4708.9   555.4  4738.9  551.49  4758.9  549.48  4768.9  548.97
  4778.9  548.86  4798.9  546.96  4808.9  546.59  4858.9   546.9  4878.9  547.89
  4918.9  547.47  4958.9  544.28  4968.9  543.14  4978.9  542.57  4988.9  540.97
  4989.8  537.12  4991.3  534.12  5008.7  534.12  5010.2  537.12  5019.6  540.85
  5029.6  541.94  5079.6  541.82  5099.6  543.93  5109.6  543.75  5119.6  544.51
  5139.6  547.22  5149.6  548.11  5159.6  549.59  5169.6  552.55  5209.6  567.01
#Mann= 3 , 1 , 0
 4658.90    0.11       0  4989.8    0.05       0  5010.2    0.14       0
Bank Sta=4989.80,5010.20
Exp/Cntr=0.3,0.1

Type RM Length L Ch R = 1 ,14098.1,672.9,672.9,672.9
XS GIS Cut Line= 3
 1953837.4101068 842118.90237829 1953753.4560151 841729.84683178
 1953722.4191546 841634.79644621
BEGIN DESCRIPTION:
Sevenmile Creek 28.0
END DESCRIPTION:
#Sta/Elev= 30
  4602.4  558.12  4642.4  551.39  4662.4  548.73  4702.4  546.38  4712.4  546.28
  4722.4  546.65  4742.4  545.95  4762.4  546.42  4792.4   544.7  4802.4  543.75
  4822.4   540.5  4832.4  539.73  4842.4   539.3  4862.4  540.86  4882.4  541.13
  4912.4  541.22  4922.4  541.61  4932.4  541.19  4952.4  541.88  4962.4  541.15
  4972.4  540.69  4982.4  539.67  4989.8  535.63  4991.3  532.63  5008.7  532.63
  5010.2  535.63  5020.4  538.19  5040.4  546.65  5050.4  549.89  5100.4  566.89
#Mann= 3 , 1 , 0
 4602.40    0.11       0  4989.8    0.05       0  5010.2    0.14       0
Bank Sta=4989.80,5010.20
Exp/Cntr=0.3,0.1

Type RM Length L Ch R = 1 ,13425.2,476.2,476.2,476.2
XS GIS Cut Line= 3
 1954400.6885993 841875.74280953 1954331.3287473 841761.14827143
 1954262.0898513 841651.18061309
BEGIN DESCRIPTION:
Sevenmile Creek 27.0
END DESCRIPTION:
#Sta/Elev= 18
  4864.4  560.88  4894.4  550.87  4914.4  544.79  4924.4  540.88  4934.4  538.54
  4974.4   532.9  4984.4     534  4989.7  531.62  4991.2  528.62  5008.7  528.62
  5010.2  531.62  5038.3  539.06  5048.3  538.48  5058.3  538.45  5068.3  541.28
  5078.3  544.52  5098.3  551.94  5128.3  555.96
#Mann= 3 , 1 , 0
 4864.40    0.11       0  4989.7    0.05       0  5010.2    0.14       0
Bank Sta=4989.70,5010.20
Exp/Cntr=0.3,0.1

Type RM Length L Ch R = 1 ,12949.0,359.3,359.3,359.3
XS GIS Cut Line= 3
 1954639.4200676 841515.67228067 1954581.7402645 841493.88213283
 1954307.2507168 841496.28993588
BEGIN DESCRIPTION:
Sevenmile Creek 26.0
END DESCRIPTION:
#Sta/Elev= 25
  4932.4  552.49  4942.4  549.22  4952.4  544.89  4962.4  539.96  4972.4  536.11
  4982.4  533.95  4989.8  530.29  4991.3  527.29  5008.7  527.29  5010.2  530.29
  5014.1  532.77  5024.1  535.18  5034.1  537.33  5044.1  538.23  5054.1  538.52
  5074.1  538.52  5104.1  539.88  5124.1  540.26  5154.1  541.89  5174.1   542.3
  5194.1  543.73  5204.1  544.85  5214.1  545.49  5244.1  547.68  5268.6  551.16
#Mann= 3 , 1 , 0
 4932.40    0.11       0  4989.8    0.05       0  5010.2    0.14       0
Bank Sta=4989.80,5010.20
Exp/Cntr=0.3,0.1

Type RM Length L Ch R = 1 ,12589.7,665.4,665.4,665.4
XS GIS Cut Line= 3
 1954721.7385782 841198.65108233 1954644.3431438 841144.75069051
 1954333.7365503 841099.00243255
BEGIN DESCRIPTION:
Sevenmile Creek 25.0
END DESCRIPTION:
#Sta/Elev= 29
  4898.6   554.7  4918.6  549.67  4928.6  547.66  4938.6   545.3  4958.6   539.7
  4968.6  536.21  4978.6  533.67  4989.8  530.27  4991.3  527.27  5008.7  527.27
  5010.2  530.27  5012.9  534.62  5032.9   536.6  5042.9  537.21  5052.9  537.52
  5072.9  536.74  5082.9  536.87  5092.9  536.54  5112.9   536.7  5132.9  535.97
  5152.9  536.22  5162.9  536.01  5172.9  536.67  5212.9  539.77  5242.9  541.33
  5252.9  542.13  5272.9   544.4  5292.9  545.05  5306.9  545.87
#Mann= 3 , 1 , 0
 4898.60    0.11       0  4989.8    0.05       0  5010.2    0.14       0
Bank Sta=4989.80,5010.20
Exp/Cntr=0.3,0.1

Type RM Length L Ch R = 1 ,11924.3,514.2,514.2,514.2
XS GIS Cut Line= 3
 1954795.1501826 841007.17116068 1954759.9176903  840610.2184133
 1954740.5616497 840575.22864772
BEGIN DESCRIPTION:
Sevenmile Creek 24.0
END DESCRIPTION:
#Sta/Elev= 28
  4600.4  550.78  4610.4  549.25  4620.4  549.51  4630.4  549.38  4640.4  547.85
  4650.4  547.76  4660.4  546.98  4670.4  547.03  4680.4  546.61  4700.4  545.26
  4740.4  539.56  4770.4  536.54  4780.4  536.68  4820.4   536.1  4830.4  536.29
  4840.4  536.03  4880.4  536.95  4900.4   536.7  4910.4  536.01  4940.4  532.21
  4950.4  530.53  4980.4  532.51  4989.8  530.22  4991.3  527.22  5008.7  527.22
  5010.2  530.22  5018.9  545.56  5038.9  560.14
#Mann= 3 , 1 , 0
 4600.40    0.11       0  4989.8    0.05       0  5010.2    0.14       0
Bank Sta=4989.80,5010.20
Exp/Cntr=0.3,0.1

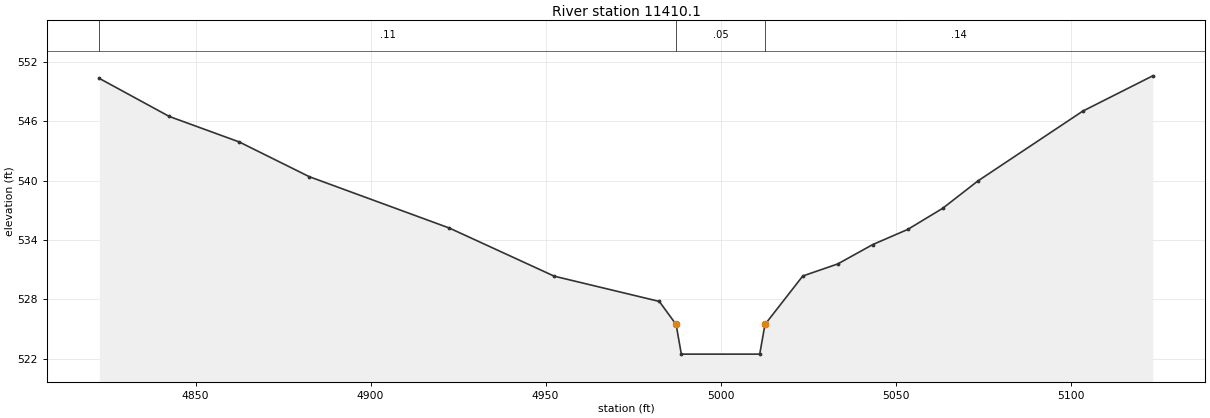
Type RM Length L Ch R = 1 ,11410.1,444.1,444.1,444.1
XS GIS Cut Line= 3
         1954825          841075 1954976.6199648 840976.20447697
 1955081.1711069 840917.22690960
BEGIN DESCRIPTION:
Sevenmile Creek 23.0
END DESCRIPTION:
#Sta/Elev= 19
  4822.5  550.33  4842.5  546.48  4862.5   543.9  4882.5  540.39  4922.5   535.2
  4952.5  530.33  4982.5  527.78  4987.3  525.45  4988.8  522.45  5011.2  522.45
  5012.7  525.45  5023.5  530.35  5033.5  531.57  5043.5  533.53  5053.5  535.06
  5063.5   537.2  5073.5  539.95  5103.5  547.02  5123.5  550.59
#Mann= 3 , 1 , 0
 4822.50    0.11       0  4987.3    0.05       0  5012.7    0.14       0
Bank Sta=4987.30,5012.70
Exp/Cntr=0.3,0.1