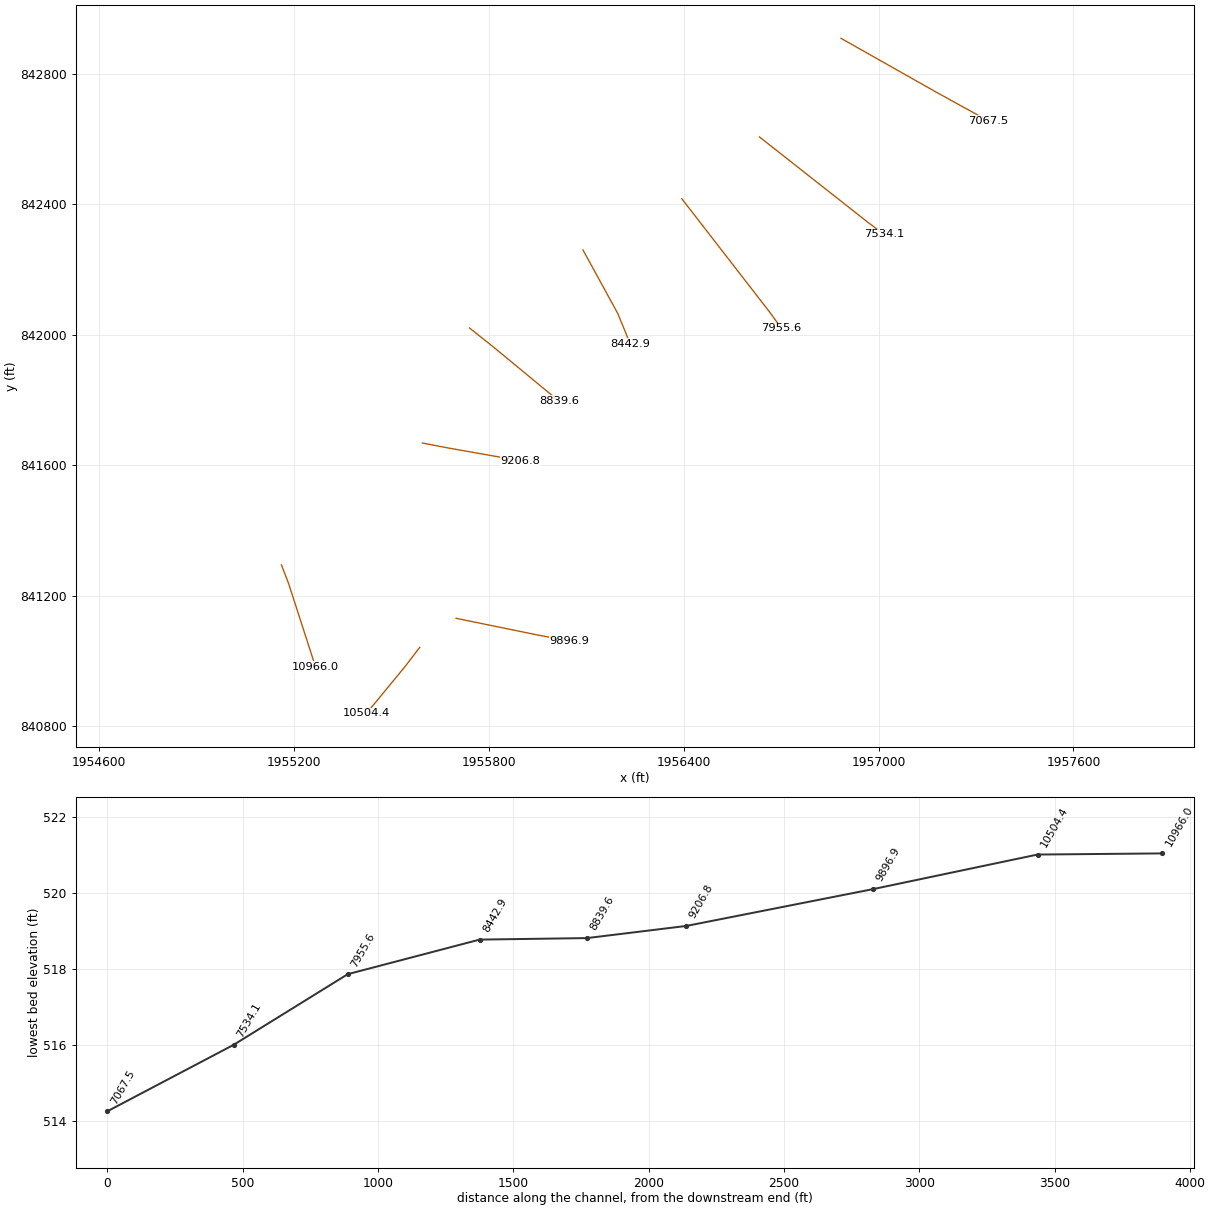
HEC-RAS study Sevenmile_Creek_FINAL.prj: Sevenmile Creek

--- Sevenmile_Creek_FINAL.g01 (geometry) --- (continued)

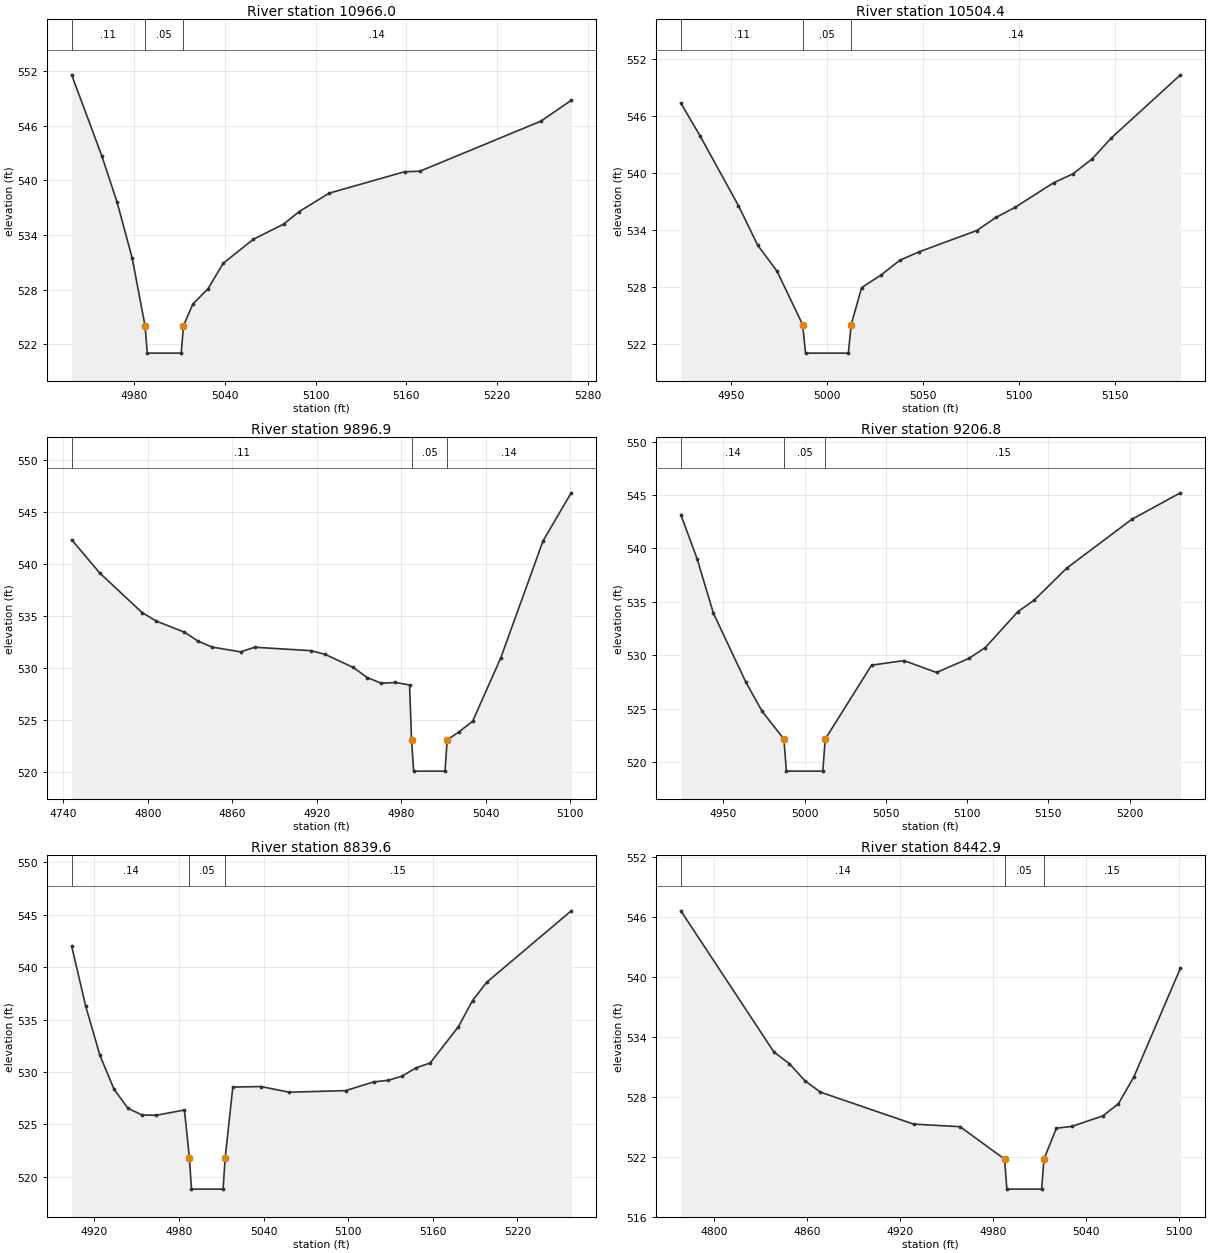
Type RM Length L Ch R = 1 ,10966.0,461.6,461.6,461.6
XS GIS Cut Line= 3
 1955162.0100255 841294.66426374 1955183.6910271 841238.65500948
 1955267.1568905 840981.83696828
BEGIN DESCRIPTION:
Sevenmile Creek 22.0
END DESCRIPTION:
#Sta/Elev= 19
  4938.8  551.59  4958.8  542.66  4968.8  537.63  4978.8  531.49  4987.3  524.05
  4988.8  521.05  5011.2  521.05  5012.7  524.05  5018.9  526.44  5028.9  528.11
  5038.9   530.9  5058.9  533.55  5078.9  535.21  5088.9  536.55  5108.9   538.6
  5158.9  540.96  5168.9  541.01  5248.9  546.51  5268.9  548.79
#Mann= 3 , 1 , 0
 4938.80    0.11       0  4987.3    0.05       0  5012.7    0.14       0
Bank Sta=4987.30,5012.70
Exp/Cntr=0.3,0.1

Type RM Length L Ch R = 1 ,10504.4,607.5,607.5,607.5
XS GIS Cut Line= 3
 1955587.6019320 841041.91686058 1955542.4536817 840983.13894976
 1955423.7971473 840839.82651219
BEGIN DESCRIPTION:
Sevenmile Creek 21.0
END DESCRIPTION:
#Sta/Elev= 21
  4923.9  547.34  4933.9  543.89  4953.9  536.54  4963.9  532.38  4973.9  529.67
  4987.3  524.02  4988.8  521.02  5011.1  521.02  5012.6  524.02    5018  527.91
    5028  529.23    5038  530.81    5048  531.69    5078  533.93    5088  535.31
    5098  536.38    5118  538.96    5128  539.89    5138  541.46    5148  543.67
    5184  550.32
#Mann= 3 , 1 , 0
 4923.90    0.11       0  4987.3    0.05       0  5012.6    0.14       0
Bank Sta=4987.30,5012.60
Exp/Cntr=0.3,0.1

Type RM Length L Ch R = 1 ,9896.9,690.1,690.1,690.1
XS GIS Cut Line= 3
 1955699.6350648 841131.07436918 1955949.2760851 841080.22156875
 1956047.5419978 841061.79671010
BEGIN DESCRIPTION:
Sevenmile Creek 20.0
END DESCRIPTION:
#Sta/Elev= 25
  4745.9  542.32  4765.9  539.12  4795.9  535.33  4805.9  534.52  4825.9  533.45
  4835.9  532.57  4845.9  532.01  4865.9  531.56  4875.9     532  4915.9  531.67
  4925.9  531.32  4945.9  530.06  4955.9  529.09  4965.9  528.54  4975.9  528.62
  4985.9  528.38  4987.3  523.11  4988.8  520.11  5011.1  520.11  5012.6  523.11
  5020.7  523.85  5030.7   524.9  5050.7  530.99  5080.7  542.21  5100.7  546.82
#Mann= 3 , 1 , 0
 4745.90    0.11       0  4987.3    0.05       0  5012.6    0.14       0
Bank Sta=4987.30,5012.60
Exp/Cntr=0.3,0.1

Type RM Length L Ch R = 1 ,9206.8,367.2,367.2,367.2
XS GIS Cut Line= 3
 1955595.9685839 841668.16717509 1955671.8971737 841653.47131901
 1955898.3935610 841613.69634367
BEGIN DESCRIPTION:
Sevenmile Creek 19.0
END DESCRIPTION:
#Sta/Elev= 19
  4923.9  543.15  4933.9  539.03  4943.9  533.94  4963.9  527.47  4973.9  524.74
  4987.3  522.14  4988.8  519.14  5011.2  519.14  5012.7  522.14  5041.2  529.07
  5061.2  529.49  5081.2  528.38  5101.2  529.71  5111.2  530.72  5131.2  534.08
  5141.2  535.15  5161.2  538.15  5201.2  542.72  5231.2  545.21
#Mann= 3 , 1 , 0
 4923.90    0.14       0  4987.3    0.05       0  5012.7    0.15       0
Bank Sta=4987.30,5012.70
Exp/Cntr=0.3,0.1

Type RM Length L Ch R = 1 ,8839.6,396.7,396.7,396.7
XS GIS Cut Line= 3
 1955741.2419015 842020.22787966 1955815.2096112 841961.67010948
 1956016.0894147 841796.70921127
BEGIN DESCRIPTION:
Sevenmile Creek 18.0
END DESCRIPTION:
#Sta/Elev= 25
  4903.8  542.02  4913.8  536.27  4923.8  531.61  4933.8  528.37  4943.8  526.52
  4953.8   525.9  4963.8  525.87  4983.8  526.37  4987.3  521.82  4988.8  518.82
  5011.2  518.82  5012.7  521.82  5018.1  528.56  5038.1  528.61  5058.1  528.07
  5098.1  528.22  5118.1  529.06  5128.1   529.2  5138.1   529.6  5148.1   530.4
  5158.1  530.86  5178.1  534.32  5188.1  536.81  5198.1  538.55  5258.1  545.38
#Mann= 3 , 1 , 0
 4903.80    0.14       0  4987.3    0.05       0  5012.7    0.15       0
Bank Sta=4987.30,5012.70
Exp/Cntr=0.3,0.1

Type RM Length L Ch R = 1 ,8442.9,487.3,487.3,487.3
XS GIS Cut Line= 3
 1956090.2953332 842259.49031342 1956197.3761114 842064.91670428
 1956235.5017925 841972.46192764
BEGIN DESCRIPTION:
Sevenmile Creek 17.0
END DESCRIPTION:
#Sta/Elev= 17
  4778.6  546.59  4838.6  532.48  4848.6  531.31  4858.6  529.61  4868.6  528.47
  4928.6  525.28  4958.6  525.02  4987.3  521.78  4988.8  518.78  5011.2  518.78
  5012.7  521.78  5020.7  524.87  5030.7  525.05  5050.7   526.1  5060.7  527.31
  5070.7     530  5100.7  540.87
#Mann= 3 , 1 , 0
 4778.60    0.14       0  4987.3    0.05       0  5012.7    0.15       0
Bank Sta=4987.30,5012.70
Exp/Cntr=0.3,0.1

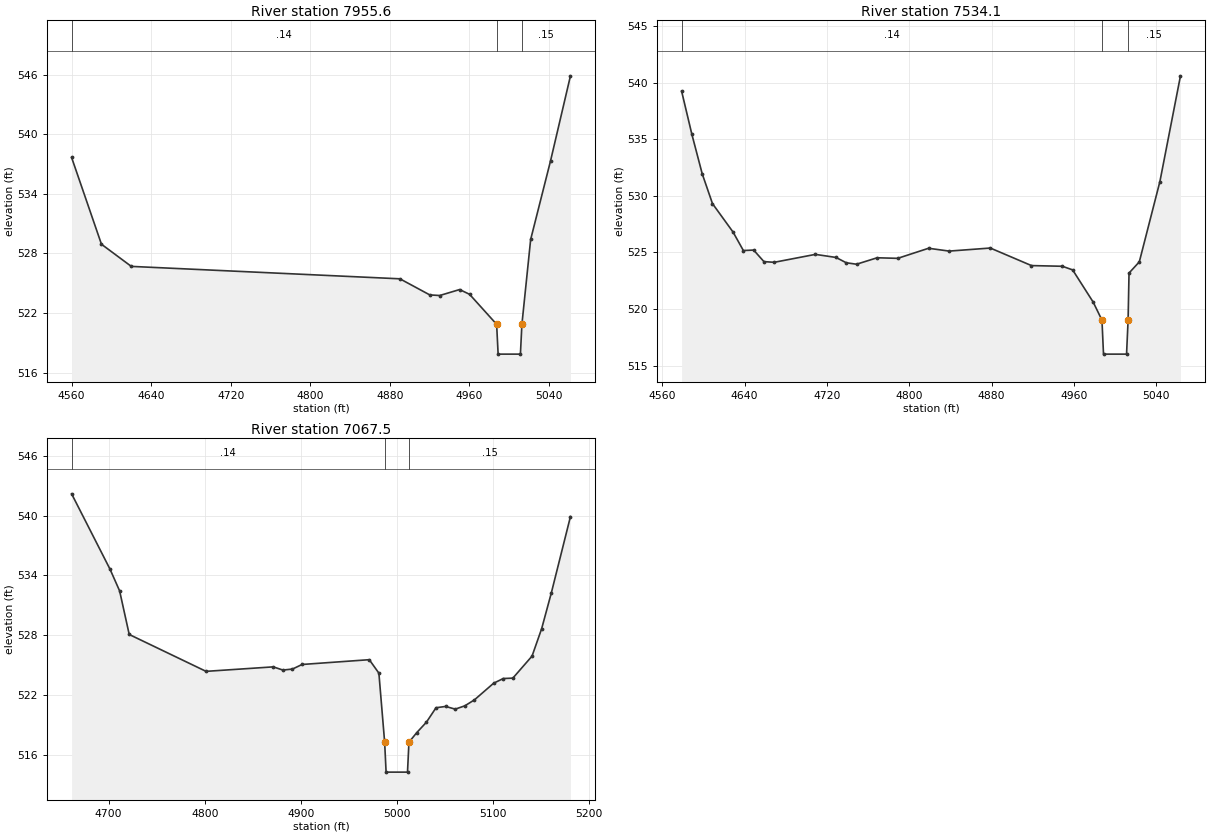
Type RM Length L Ch R = 1 ,7955.6,421.5,421.5,421.5
XS GIS Cut Line= 3
 1956394.6233373 842416.26332541 1956665.8382729 842067.99869219
 1956701.0996058 842019.51435940
BEGIN DESCRIPTION:
Sevenmile Creek 16.0
END DESCRIPTION:
#Sta/Elev= 15
  4560.1  537.66  4590.1  528.93  4620.1   526.7  4890.1  525.45  4920.1  523.83
  4930.1  523.77  4950.1  524.37  4960.1  523.89  4987.3  520.87  4988.8  517.87
  5011.2  517.87  5012.7  520.87  5021.5  529.41  5041.5  537.33  5061.5  545.88
#Mann= 3 , 1 , 0
 4560.10    0.14       0  4987.3    0.05       0  5012.7    0.15       0
Bank Sta=4987.30,5012.70
Exp/Cntr=0.3,0.1

Type RM Length L Ch R = 1 ,7534.1,466.6,466.6,466.6
XS GIS Cut Line= 3
 1956633.4773999 842605.80558154 1956967.8730875 842343.83660965
 1957015.9943265 842307.98156889
BEGIN DESCRIPTION:
Sevenmile Creek 15.0
END DESCRIPTION:
#Sta/Elev= 30
  4578.8  539.23  4588.8  535.41  4598.8  531.94  4608.8   529.3  4628.8  526.79
  4638.8  525.16  4648.8   525.2  4658.8  524.18  4668.8  524.12  4708.8  524.82
  4728.8  524.55  4738.8  524.08  4748.8  523.95  4768.8  524.52  4788.8  524.47
  4818.8  525.36  4838.8  525.11  4878.8  525.38  4918.8  523.83  4948.8  523.77
  4958.8  523.45  4978.8   520.6  4987.3  519.01  4988.8  516.01  5011.2  516.01
  5012.7  519.01  5013.6  523.17  5023.6  524.16  5043.6  531.25  5063.6  540.59
#Mann= 3 , 1 , 0
 4578.80    0.14       0  4987.3    0.05       0  5012.7    0.15       0
Bank Sta=4987.30,5012.70
Exp/Cntr=0.3,0.1

Type RM Length L Ch R = 1 ,7067.5,0,0,0
XS GIS Cut Line= 3
 1956884.6594141  842907.8403962 1957180.5302530 842741.41304935
 1957338.4450008 842654.87219882
BEGIN DESCRIPTION:
Sevenmile Creek 14.0
END DESCRIPTION:
#Sta/Elev= 29
  4661.4  542.18  4701.4  534.62  4711.4  532.44  4721.4  528.07  4801.4  524.37
  4871.4  524.82  4881.4   524.5  4891.4   524.6  4901.4  525.06  4971.4  525.54
  4981.4  524.19  4987.4  517.26  4988.9  514.26  5011.2  514.26  5012.7  517.26
  5020.9  518.23  5030.9  519.27  5040.9  520.72  5050.9  520.85  5060.9  520.58
  5070.9  520.91  5080.9  521.51  5100.9  523.18  5110.9  523.65  5120.9  523.69
  5140.9   525.9  5150.9  528.65  5160.9  532.21  5180.9   539.9
#Mann= 3 , 1 , 0
 4661.40    0.14       0  4987.4    0.05       0  5012.7    0.15       0
Bank Sta=4987.40,5012.70
Exp/Cntr=0.3,0.1

Chan Stop Cuts=-1