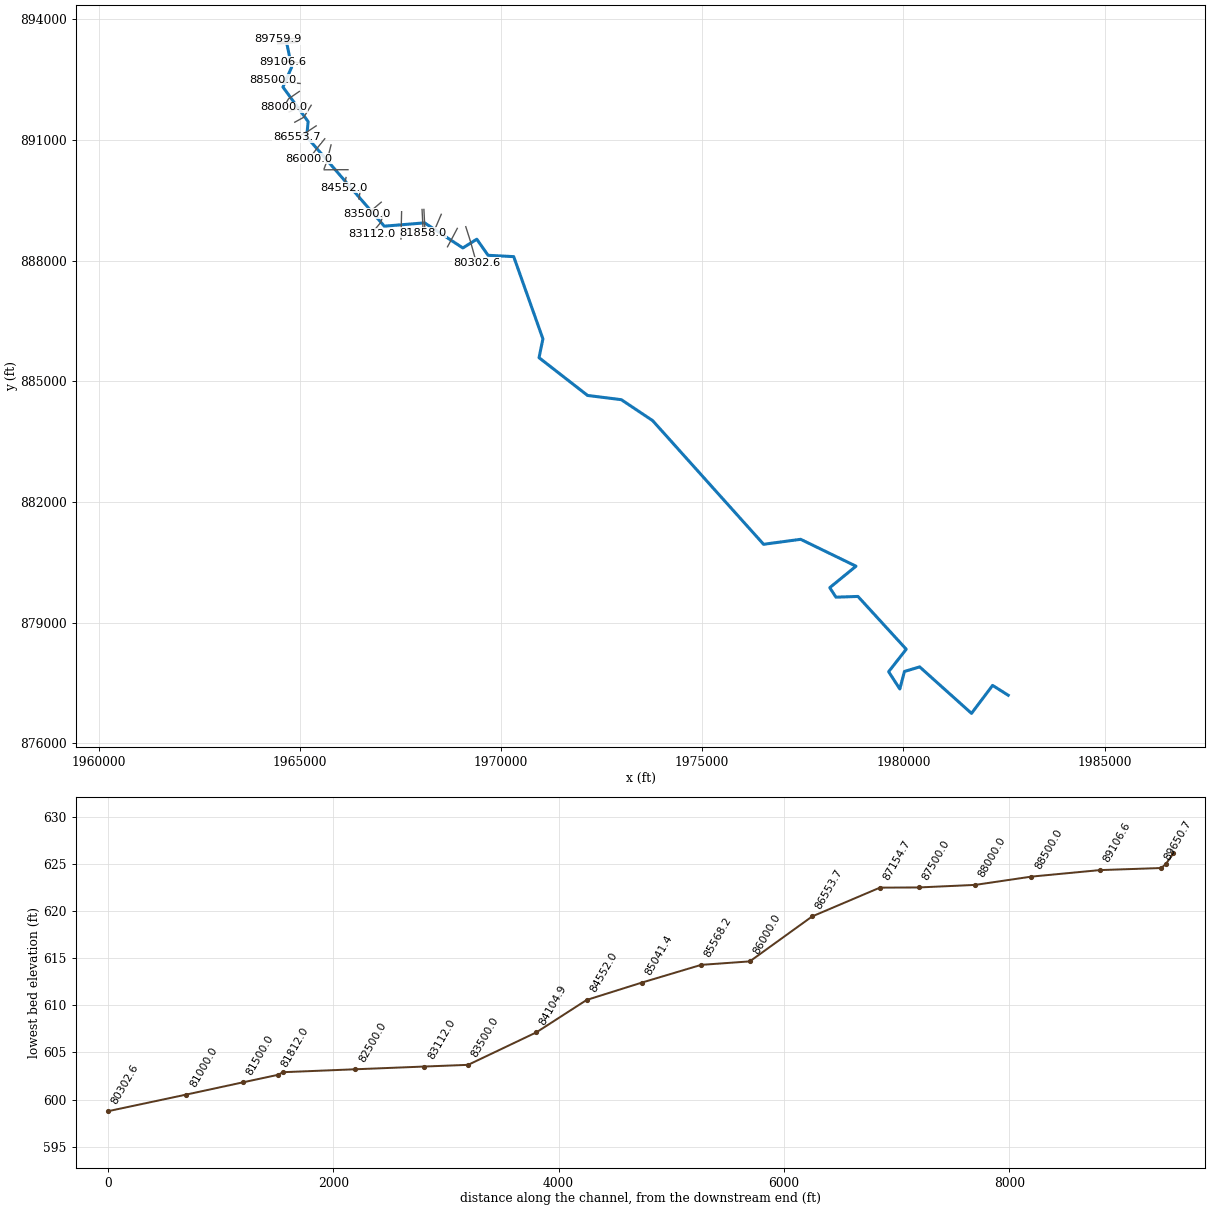
--- S_Fork_Little_River_FINAL.prj (project) ---

Proj Title=South Fork Little River
Current Plan=p01
Default Exp/Contr=0.3,0.1
English Units
Geom File=g01
Flow File=f01
Plan File=p01
Y Axis Title=Elevation
X Axis Title(PF)=Main Channel Distance
X Axis Title(XS)=Station
BEGIN DESCRIPTION:
####(Watershed Name)####
SOUTH FORK LITTLE RIVER
HCFCD Unit X###-##-##
(Flood Hazard, Floodway) Model
10, 2, 1, 0.2% Event
Filename:  N:\NC_flood\60138\Orange\URS\Limited_Detail\ENG\South Fork Little River\South Fork Little River.prj
Prepared by:  ________     Date: ________
Reviewed by:  ________     Date: ________
STATUS (Draft RAS, SVSQ, FINAL)
END DESCRIPTION:
DSS Export Rating Curves= 0
DSS Export Rating Curve Sorted= 0
DSS Export Volume Flow Curves= 0
DXF OffsetX= 0
DXF OffsetY= 0
DXF ScaleX= 1
DXF ScaleY= 10

--- S_Fork_Little_River_FINAL.p01 (plan) ---

Plan Title=100 Year Single
Version=Version 3.0.1  Mar 2001
Short Identifier=100 Year Sin
Geom File=g01
Flow File=f01
Subcritical Flow
K Sum by GR= 0
Std Step Tol= 0.01
Critical Tol= 0.01
Num of Std Step Trials= 20
Max Error Tol= 0.3
Flow Tol Ratio= 0.001
Split Flow NTrial= 30
Split Flow Tol= 0.02
Split Flow Ratio= 0.02
Log Output Level= 0
Friction Slope Method= 1
Unsteady Friction Slope Method= 2
Parabolic Critical Depth
Global Vel Dist= 0 , 0 , 0
Global Log Level= 0
CheckData=True
Encroach Param=-1 ,0,0, 2
Encroach River=South Fork Littl
Encroach Reach=Reach - 1
Encroach Node=89759.9
       1 4979.69  5041.1
Encroach Node=89691.2
       1    4969    5023
Encroach Node=89670.9
       1    4969    5023
Encroach Node=89650.7
       1    4969    5023
Encroach Node=89106.6
       1 4878.95 5023.78
Encroach Node=88500.0
       1 4853.37 5048.69
Encroach Node=88000.0
       1 4899.27 5054.49
Encroach Node=87500.0
       1 4855.28 5015.17
Encroach Node=87154.7
       1 4957.88 5068.26
Encroach Node=86553.7
       1    4995 5058.48
Encroach Node=86000.0
       1    4970    5025
Encroach Node=85568.2
       1 4961.95 5028.14
Encroach Node=85041.4
       1    4950    5045
Encroach Node=84552.0
       1 4990.41 5015.81
Encroach Node=84104.9
       1 4984.18 5026.93
Encroach Node=83500.0
       1 4942.05 5011.01
Encroach Node=83112.0
       1 4970.78 5184.47
Encroach Node=82500.0
       1  4817.3 5031.83
Encroach Node=81858.0
       1    4972    5027
Encroach Node=81835.0
       1    4972    5027
Encroach Node=81812.0
       1    4972    5027
Encroach Node=81500.0
       1 4815.04    5008
Encroach Node=81000.0
       1 4914.81  5087.1
Encroach Node=80302.6
       1 4899.16 5038.43
Encroach Node=79449.3
       1  4838.6 5168.12
Encroach Node=79079.0
       1 4842.11 5152.97
Encroach Node=78500.0
       1 4982.26 5257.03
Encroach Node=78000.0
       1 4960.58 5131.62
Encroach Node=77500.0
       1 4935.12 5069.96
Encroach Node=77000.0
       1    4987  5262.9
Encroach Node=76473.6
       1    4969    5030
Encroach Node=76441.8
       1    4969    5030
Encroach Node=76410.1
       1    4969    5030
Encroach Node=76117.4
       1  4981.3 5390.92
Encroach Node=75500.0
       1  4770.2 5082.75
Encroach Node=75097.4
       1 4657.85 5083.51
Encroach Node=74398.8
       1 4598.78    5016
Encroach Node=74000.0
       1 4706.16    5030
Encroach Node=73433.4
       1 4766.74    5015
Encroach Node=72924.9
       1  4799.4 5173.38
Encroach Node=72408.0
       1    4820    5050
Encroach Node=71752.2
       1    4875    5050
Encroach Node=71731.9
       1    4875    5050
Encroach Node=71711.7
       1    4875    5050
Encroach Node=71319.0
       1 4936.43 5037.18
Encroach Node=70855.4
       1    4975 5067.49
Encroach Node=70500.0
       1    4981 5090.56
Encroach Node=70000.0
       1 4981.57 5088.94
Encroach Node=69369.1
       1    4970  5135.4
Encroach Node=68557.5
       1 4677.01    5030
Encroach Node=68000.0
       1  4735.5    5030
Encroach Node=67427.3
       1 4495.84    5039
Encroach Node=66668.0
       1 4748.67 5031.06
Encroach Node=66000.0
       1 4930.71    5029
Encroach Node=65393.3
       1    4966 5017.44
Encroach Node=65000.0
       1 4876.87 5031.22
Encroach Node=64371.8
       1 4912.06    5027
Encroach Node=63954.8
       1 4836.28    5027
Encroach Node=63396.4
       1 4927.25 5019.32
Encroach Node=62959.0
       1 4982.93 5023.75
Encroach Node=62446.8
       1    4965    5040
Encroach Node=62000.0
       1    4980    5030
Encroach Node=61500.0
       1 4985.78 5072.42
Encroach Node=60934.2
       1    4976    5250
Encroach Node=60500.0
       1 4942.75 5024.47
Encroach Node=60000.0
       1 4957.66 5036.28
Encroach Node=59500.0
       1 4911.25 5025.63
Encroach Node=59032.5
       1  4981.5 5087.27
Encroach Node=58500.0
       1 4954.41 5039.15
Encroach Node=58000.0
       1    4968 5036.48
Encroach Node=57379.6
       1    4976    5031
Encroach Node=56697.0
       1    4969    5030
Encroach Node=56678.7
       1    4969    5030
Encroach Node=56660.5
       1    4969    5030
Encroach Node=55965.6
       1    4983 5061.18
Encroach Node=55298.6
       1    4967 5062.02
Computation Interval=1HOUR
Output Interval=1HOUR
Run HTab= 0
Run UNet= 0
Run PostProcess= 0
UNET Theta= 1
UNET ZTol= 0.02
UNET ZSATol= 0.1
UNET MxIter= 20
UNET MaxInSteps= 20
UNET DtIC= 0
UNET DtMin= 0
UNET MaxCRTS= 20
UNET WFStab= 2
UNET SFStab= 1
UNET WFX= 1
UNET SFX= 1
UNET Convert EG Bridges=-1
UNET Use Existing IB Tables=-1
Instantaneous Interval=1HOUR
DSS File=dss
Write IC File= 0
Write Velocity= 0
Write Detailed= 0

--- S_Fork_Little_River_FINAL.f01 (steady flow) ---

Flow Title= 100 Year Single
Version=Version 3.0.1  Mar 2001
Number of Profiles= 2
Profile Names=100-Year,100 yr fw
River Rch & RM=South Fork Littl,Reach - 1       ,89759.9
    1075    1075
River Rch & RM=South Fork Littl,Reach - 1       ,89106.6
    1410    1410
River Rch & RM=South Fork Littl,Reach - 1       ,85041.4
    1688    1688
River Rch & RM=South Fork Littl,Reach - 1       ,80302.6
    2296    2296
River Rch & RM=South Fork Littl,Reach - 1       ,72924.9
    2487    2487
River Rch & RM=South Fork Littl,Reach - 1       ,71319.0
    4012    4012
River Rch & RM=South Fork Littl,Reach - 1       ,60934.2
    4159    4159
River Rch & RM=South Fork Littl,Reach - 1       ,56697.0
    4282    4282
Boundary for River Rch & Prof#=South Fork Littl,Reach - 1       , 1
Up Type= 0
Dn Type= 1
Dn Known WS=551.81
Boundary for River Rch & Prof#=South Fork Littl,Reach - 1       , 2
Up Type= 0
Dn Type= 1
Dn Known WS=552.51
DSS Import GetInterval= 0
DSS Import GetPeak= 0
DSS Import FillOption= 0

--- S_Fork_Little_River_FINAL.g01 (geometry) ---

Geom Title=Geom 01 by CodeH2 for Windows

River Reach=South Fork Littl,Reach - 1
Reach XY= 30
       1964653.5 893504.77750112      1964796.67       892810.03
      1964579.82       892312.06      1965205.81       891453.02
      1965169.24        891074.7      1967098.43       888853.94
      1968100.65        888936.5      1969050.61        888312.6
      1969397.57       888529.97      1969678.69       888129.71
      1970315.14       888097.31      1971040.94       886053.69
      1970944.79        885585.5       1972150.8       884647.03
      1972989.98       884541.48      1973768.03       884021.56
      1976525.37       880947.62      1977447.61       881071.07
      1978822.99       880402.99       1978170.8       879869.26
      1978323.93       879632.91       1978870.7       879651.21
       1980071.6       878339.63      1979633.85       877780.37
      1979911.81       877350.94      1980026.79        877786.4
      1980405.54       877900.02      1981693.31       876744.82
      1982217.89       877439.84 1982606.0015812 877195.64945346

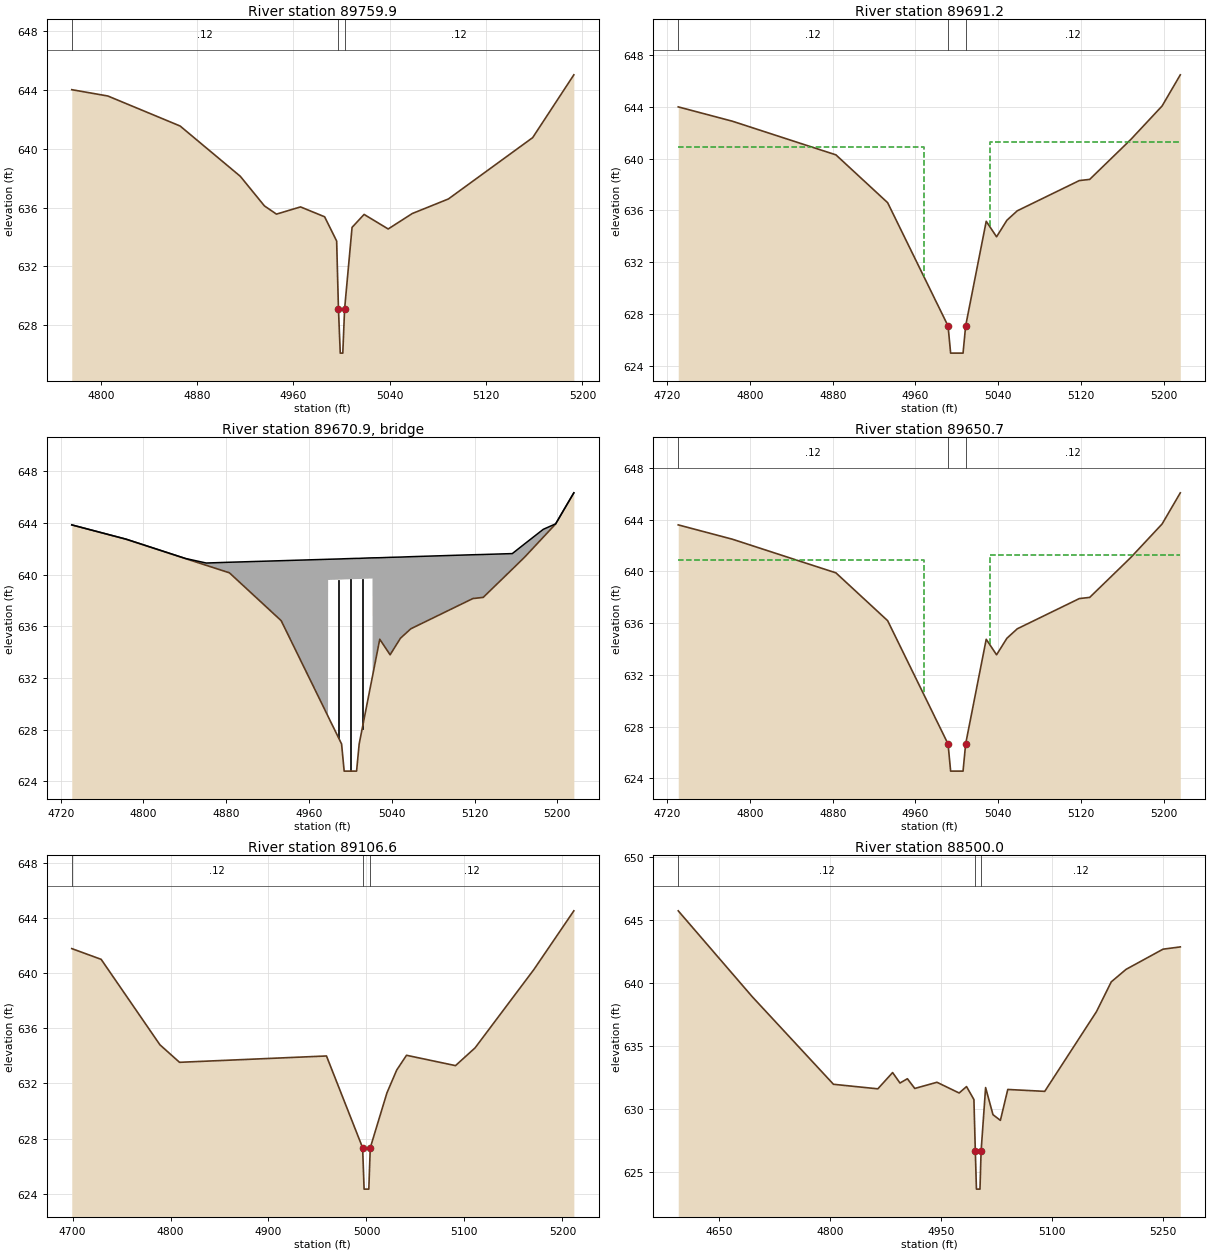
Type RM Length L Ch R = 1 ,89759.9,68.75,68.75,68.75
XS GIS Cut Line= 3
 1964876.8244981 893522.95885348 1964654.7712075 893504.81118675
 1964460.5618473 893504.87602444
BEGIN DESCRIPTION:
South Fork Little River 179.0
END DESCRIPTION:
#Sta/Elev= 20
  4775.9  644.01  4805.9  643.58  4865.9  641.54  4915.9  638.12  4935.9  636.11
  4945.9  635.55  4965.9  636.04  4985.9  635.37  4995.9  633.72  4997.4   629.1
  4998.9   626.1    5001   626.1  5002.5   629.1  5008.7  634.65  5018.7  635.53
  5038.7  634.54  5058.7  635.59  5088.7  636.58  5158.7  640.75  5192.9  645.02
#Mann= 3 , 1 , 0
 4775.90    0.12       0  4997.4    0.04       0  5002.5    0.12       0
Bank Sta=4997.40,5002.50
Exp/Cntr=0.5,0.3

Type RM Length L Ch R = 1 ,89691.2,40.5,40.5,40.5
XS GIS Cut Line= 3
 1964933.6363307 893463.00766759 1964668.9347501 893438.54679546
 1964449.8980395 893425.13638460
BEGIN DESCRIPTION:
Upstream Section of Bridge/Culvert/Weir
END DESCRIPTION:
#Sta/Elev= 28
  4730.7  644.01  4783.1   642.9  4840.7   641.4  4860.7  640.88  4883.1   640.3
  4933.1   636.6 4978.41   629.2  4978.5  629.18    4983  628.45  4991.5  627.06
    4994  624.96    5006  624.96  5008.5  627.06    5017  630.52 5021.39  632.31
  5021.5  632.35  5028.4  635.16  5038.4  633.96  5048.4  635.24  5058.4  635.97
  5118.4  638.31  5128.4   638.4  5156.5  640.58  5168.4  641.51  5186.5  643.06
  5198.4  644.08  5206.5  645.19    5216  646.49
#Mann= 3 , 1 , 0
 4730.70    0.12       0  4991.5    0.04       0  5008.5    0.12       0
#XS Ineff= 2 , 0
       0  4968.3   640.9  5031.6       0   641.3
Bank Sta=4991.50,5008.50
Exp/Cntr=0.5,0.3

Type RM Length L Ch R = 3 ,89670.9,,,
BEGIN DESCRIPTION:
Hawkins Road-TOR
Structure ID: Hawkins Road (SFLR)-Bridge
Approximate Survey Structure
END DESCRIPTION:
Bridge Culvert--1,0,-1,-1, 0
Deck Dist Width WeirC Skew NumUp NumDn MinLoCord MaxHiCord MaxSubmerge Is_Ogee
10,20.5,2.6,,28,28,,,0.95,0,1,1,,
  4730.7  4783.1  4840.7  4860.7  4883.1  4933.1 4978.41  4978.5    4983  4991.5
    4994    5006  5008.5    5017 5021.39  5021.5  5028.4  5038.4  5048.4  5058.4
  5118.4  5128.4  5156.5  5168.4  5186.5  5198.4  5206.5    5216
  643.85  642.75  641.25   640.9  640.96  641.08  641.19  641.19   641.2  641.22
  641.23  641.26  641.26  641.29   641.3   641.3  641.31  641.34  641.36  641.39
  641.54  641.56  641.63  642.38  643.51  643.93  645.04  646.33
  643.85  642.74  641.24  640.72  640.14  636.44  629.04  639.59   639.6  639.62
  639.63  639.66  639.66  639.69   639.7  632.19     635   633.8  635.08  635.81
  638.15  638.24  640.42  641.35   642.9  643.92  645.03  646.33
  4730.7  4783.1  4840.7  4860.7  4883.1  4933.1 4978.41  4978.5    4983  4991.5
    4994    5006  5008.5    5017 5021.39  5021.5  5028.4  5038.4  5048.4  5058.4
  5118.4  5128.4  5156.5  5168.4  5186.5  5198.4  5206.5    5216
  643.85  642.75  641.25   640.9  640.96  641.08  641.19  641.19   641.2  641.22
  641.23  641.26  641.26  641.29   641.3   641.3  641.31  641.34  641.36  641.39
  641.54  641.56  641.63  642.38  643.51  643.93  645.04  646.33
   643.6  642.49  640.99  640.47  639.89  636.19  628.79  639.34  639.35  639.37
  639.38  639.41  639.41  639.44  639.45  631.94  634.75  633.55  634.83  635.56
   637.9  637.99  640.17   641.1  642.65  643.67  644.78  646.08
Pier Skew, UpSta & Num, DnSta & Num=,4988.6, 2 ,4988.6, 2 , 0 , 0 , 0 ,,
       1       1
  626.29  640.61
       1       1
  626.04  640.36
Pier Skew, UpSta & Num, DnSta & Num=,5000.0, 2 ,5000.0, 2 , 0 , 0 , 0 ,,
       1       1
   623.8  640.65
       1       1
  623.55   640.4
Pier Skew, UpSta & Num, DnSta & Num=,5011.3, 2 ,5011.3, 2 , 0 , 0 , 0 ,,
       1       1
  626.84  640.67
       1       1
  626.59  640.42
Abutment Skew #Up #Dn=, 2 , 2
 4978.30 4983.00
  639.59  628.29
 4978.30 4983.00
  639.34  628.04
Abutment Skew #Up #Dn=, 2 , 2
 5017.00 5021.59
  630.36  639.70
 5017.00 5021.59
  630.11  639.45
BR Coef= 1 , 1 , 0 ,1.25, 0 ,,,0.8,0,2,0,
Wspro=,,,, 1 ,,,, 0 ,,,, 0 ,,,,-1 ,-1 ,-1 , 0 , 0 , 0 , 0 , 0
BC Design=,, 0 ,, 0 ,,,,,,
BR U #Sta/Elev= 28
  4730.7  643.85  4783.1  642.74  4840.7  641.24  4860.7  640.72  4883.1  640.14
  4933.1  636.44 4978.41  629.04  4978.5  629.02    4983  628.29  4991.5   626.9
    4994   624.8    5006   624.8  5008.5   626.9    5017  630.36 5021.39  632.15
  5021.5  632.19  5028.4     635  5038.4   633.8  5048.4  635.08  5058.4  635.81
  5118.4  638.15  5128.4  638.24  5156.5  640.42  5168.4  641.35  5186.5   642.9
  5198.4  643.92  5206.5  645.03    5216  646.33
BR U #Mann= 3
 4730.70    0.12  4991.5    0.04  5008.5    0.12
BR U Banks=4991.50,5008.50
BR D #Sta/Elev= 28
  4730.7   643.6  4783.1  642.49  4840.7  640.99  4860.7  640.47  4883.1  639.89
  4933.1  636.19 4978.41  628.79  4978.5  628.77    4983  628.04  4991.5  626.65
    4994  624.55    5006  624.55  5008.5  626.65    5017  630.11 5021.39   631.9
  5021.5  631.94  5028.4  634.75  5038.4  633.55  5048.4  634.83  5058.4  635.56
  5118.4   637.9  5128.4  637.99  5156.5  640.17  5168.4   641.1  5186.5  642.65
  5198.4  643.67  5206.5  644.78    5216  646.08
BR D #Mann= 3
 4730.70    0.12  4991.5    0.04  5008.5    0.12
BR D Banks=4991.50,5008.50

Type RM Length L Ch R = 1 ,89650.7,544.05,544.05,544.05
XS GIS Cut Line= 3
 1964931.5173227 893422.56314008 1964666.8157421 893398.10226795
 1964447.7790315 893384.69185709
BEGIN DESCRIPTION:
Downstream Section of Bridge/Culvert/Weir
END DESCRIPTION:
#Sta/Elev= 28
  4730.7   643.6  4783.1  642.49  4840.7  640.99  4860.7  640.47  4883.1  639.89
  4933.1  636.19 4978.41  628.79  4978.5  628.77    4983  628.04  4991.5  626.65
    4994  624.55    5006  624.55  5008.5  626.65    5017  630.11 5021.39   631.9
  5021.5  631.94  5028.4  634.75  5038.4  633.55  5048.4  634.83  5058.4  635.56
  5118.4   637.9  5128.4  637.99  5156.5  640.17  5168.4   641.1  5186.5  642.65
  5198.4  643.67  5206.5  644.78    5216  646.08
#Mann= 3 , 1 , 0
 4730.70    0.12       0  4991.5    0.04       0  5008.5    0.12       0
#XS Ineff= 2 , 0
       0  4968.3   640.9  5031.6       0   641.3
Bank Sta=4991.50,5008.50
Exp/Cntr=0.5,0.3

Type RM Length L Ch R = 1 ,89106.6,606.6,606.6,606.6
XS GIS Cut Line= 3
 1965094.0459034 892897.23152182 1964795.7717349  892942.6210692
 1964585.0345507 892939.37895867
BEGIN DESCRIPTION:
South Fork Little River 178.0
END DESCRIPTION:
#Sta/Elev= 16
  4699.2  641.78  4729.2     641  4789.2   634.8  4809.2  633.53  4959.2  633.99
  4996.1  627.33  4997.6  624.33  5002.4  624.33  5003.9  627.33  5020.9  631.31
  5030.9  632.97  5040.9  634.04  5090.9  633.29  5110.9  634.58  5170.9  640.26
  5211.7  644.52
#Mann= 3 , 1 , 0
 4699.20    0.12       0  4996.1    0.04       0  5003.9    0.12       0
Bank Sta=4996.10,5003.90
Exp/Cntr=0.3,0.1

Type RM Length L Ch R = 1 ,88500.0,500,500,500
XS GIS Cut Line= 3
 1965006.5089192 892401.18861123 1964602.7109930 892441.24358113
 1964335.3920401 892498.45192703
BEGIN DESCRIPTION:
South Fork Little River 177.0
END DESCRIPTION:
#Sta/Elev= 26
  4594.2   645.7  4694.2   638.9  4804.2  631.95  4864.2  631.59  4884.2  632.88
  4894.2  632.05  4904.2  632.39  4914.2  631.62  4944.2  632.11  4974.2  631.26
  4984.2  631.77  4994.2  630.74  4996.1  626.64  4997.6  623.64  5002.4  623.64
  5003.9  626.64    5010  631.69    5020  629.54    5030  629.09    5040  631.54
    5090  631.39    5160  637.71    5180  640.07    5200  641.06    5250  642.66
  5273.4  642.84
#Mann= 3 , 1 , 0
 4594.20    0.12       0  4996.1    0.04       0  5003.9    0.12       0
Bank Sta=4996.10,5003.90
Exp/Cntr=0.3,0.1

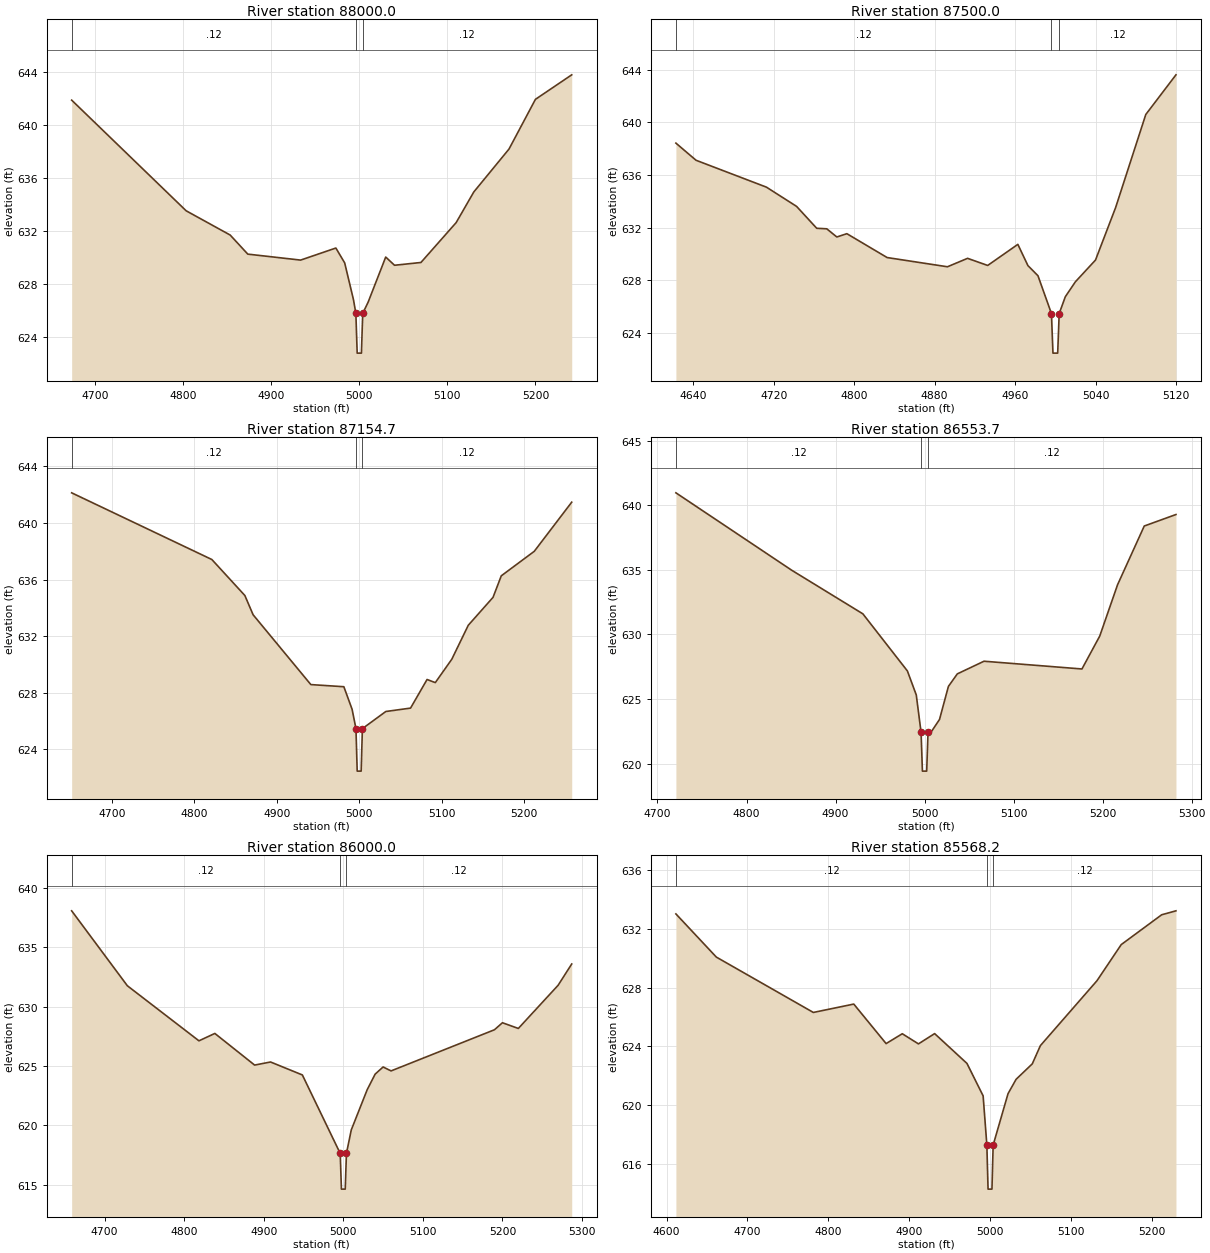
Type RM Length L Ch R = 1 ,88000.0,500,500,500
XS GIS Cut Line= 3
 1964987.0562560  892203.4198691 1964717.7695636 892018.61435205
 1964594.7608823 891811.12449536
BEGIN DESCRIPTION:
South Fork Little River 176.0
END DESCRIPTION:
#Sta/Elev= 21
  4673.4  641.85  4803.4   633.5  4853.4  631.67  4873.4  630.23  4933.4  629.78
  4973.4  630.69  4983.4  629.57  4993.4  626.79  4996.1  625.76  4997.6  622.76
  5002.4  622.76  5003.9  625.76    5010   626.6    5030  630.01    5040  629.39
    5070   629.6    5110  632.61    5130  634.92    5170  638.16    5200  641.91
  5241.2  643.76
#Mann= 3 , 1 , 0
 4673.40    0.12       0  4996.1    0.04       0  5003.9    0.12       0
Bank Sta=4996.10,5003.90
Exp/Cntr=0.3,0.1

Type RM Length L Ch R = 1 ,87500.0,345.3,345.3,345.3
XS GIS Cut Line= 3
 1965181.5828876 891905.14570064 1964841.8217495 891741.20564028
 1964732.3175844 891692.12113352
BEGIN DESCRIPTION:
South Fork Little River 175.0
END DESCRIPTION:
#Sta/Elev= 25
  4622.8  638.42  4642.8  637.12  4712.8  635.08  4742.8  633.62  4762.8  631.96
  4772.8  631.92  4782.8   631.3  4792.8  631.55  4832.8  629.74  4892.8  629.04
  4912.8  629.68  4932.8  629.14  4962.8  630.74  4972.8  629.13  4982.8  628.36
  4996.2  625.49  4997.7  622.49  5002.4  622.49  5003.9  625.49    5010  626.77
    5020   627.9    5040  629.55    5060  633.53    5090  640.59    5120   643.6
#Mann= 3 , 1 , 0
 4622.80    0.12       0  4996.2    0.04       0  5003.9    0.12       0
Bank Sta=4996.20,5003.90
Exp/Cntr=0.3,0.1

Type RM Length L Ch R = 1 ,87154.7,601,601,601
XS GIS Cut Line= 3
 1965282.0883139 891859.75615326 1965097.2880139  891561.4819848
 1964873.5823876 891438.28178479
BEGIN DESCRIPTION:
South Fork Little River 174.0
END DESCRIPTION:
#Sta/Elev= 21
  4651.4  642.12  4821.4  637.41  4861.4  634.87  4871.4  633.51  4941.4  628.58
  4981.4  628.43  4991.4  626.84  4996.1  625.47  4997.6  622.47  5002.4  622.47
  5003.9  625.47  5032.3  626.68  5062.3  626.92  5082.3  628.94  5092.3  628.72
  5112.3  630.37  5132.3  632.77  5162.3  634.74  5172.3  636.26  5212.3  637.99
  5257.7  641.46
#Mann= 3 , 1 , 0
 4651.40    0.12       0  4996.1    0.04       0  5003.9    0.12       0
Bank Sta=4996.10,5003.90
Exp/Cntr=0.3,0.1

Type RM Length L Ch R = 1 ,86553.7,553.7,553.7,553.7
XS GIS Cut Line= 3
 1965405.2885139 891347.50269004 1965175.0986666 891195.12349528
 1964918.9719349 891068.68118474
BEGIN DESCRIPTION:
South Fork Little River 173.0
END DESCRIPTION:
#Sta/Elev= 19
  4720.7  640.97  4850.7  634.98  4930.7   631.6  4980.7  627.18  4990.7  625.32
  4996.1  622.42  4997.6  619.42  5002.4  619.42  5003.9  622.42  5006.8  622.39
  5016.8  623.42  5026.8  625.98  5036.8  626.95  5066.8  627.93  5176.8  627.33
  5196.8  629.88  5216.8  633.85  5246.8   638.4  5282.4  639.29
#Mann= 3 , 1 , 0
 4720.70    0.12       0  4996.1    0.04       0  5003.9    0.12       0
Bank Sta=4996.10,5003.90
Exp/Cntr=0.3,0.1

Type RM Length L Ch R = 1 ,86000.0,431.8,431.8,431.8
XS GIS Cut Line= 3
 1965619.2678087 891026.53374789 1965403.7268926 890761.68258501
 1965233.4566560  890530.4908373
BEGIN DESCRIPTION:
South Fork Little River 172.0
END DESCRIPTION:
#Sta/Elev= 21
  4658.5  638.05  4728.5  631.75  4818.5  627.12  4838.5  627.74  4888.5  625.08
  4908.5  625.34  4948.5  624.25  4996.1  617.65  4997.6  614.65  5002.4  614.65
  5003.9  617.65    5010  619.63    5030  623.01    5040  624.32    5050  624.92
    5060  624.59    5190  628.05    5200  628.64    5220  628.16    5270  631.79
  5287.1  633.58
#Mann= 3 , 1 , 0
 4658.50    0.12       0  4996.1    0.04       0  5003.9    0.12       0
Bank Sta=4996.10,5003.90
Exp/Cntr=0.3,0.1

Type RM Length L Ch R = 1 ,85568.2,526.8,526.8,526.8
XS GIS Cut Line= 3
 1965774.8891140 890874.15455313 1965680.8679087  890494.8276215
 1965603.0572561 890280.84832674
BEGIN DESCRIPTION:
South Fork Little River 171.0
END DESCRIPTION:
#Sta/Elev= 22
  4611.5  633.02  4661.5  630.08  4781.5  626.31  4831.5  626.88  4871.5  624.19
  4891.5  624.86  4911.5  624.17  4931.5  624.87  4971.5  622.84  4991.5  620.63
  4996.1  617.28  4997.6  614.28  5002.4  614.28  5003.9  617.28  5022.3  620.78
  5032.3  621.76  5052.3  622.81  5062.3  624.05  5132.3  628.47  5162.3  630.93
  5212.3  632.96    5230  633.23
#Mann= 3 , 1 , 0
 4611.50    0.12       0  4996.1    0.04       0  5003.9    0.12       0
Bank Sta=4996.10,5003.90
Exp/Cntr=0.3,0.1

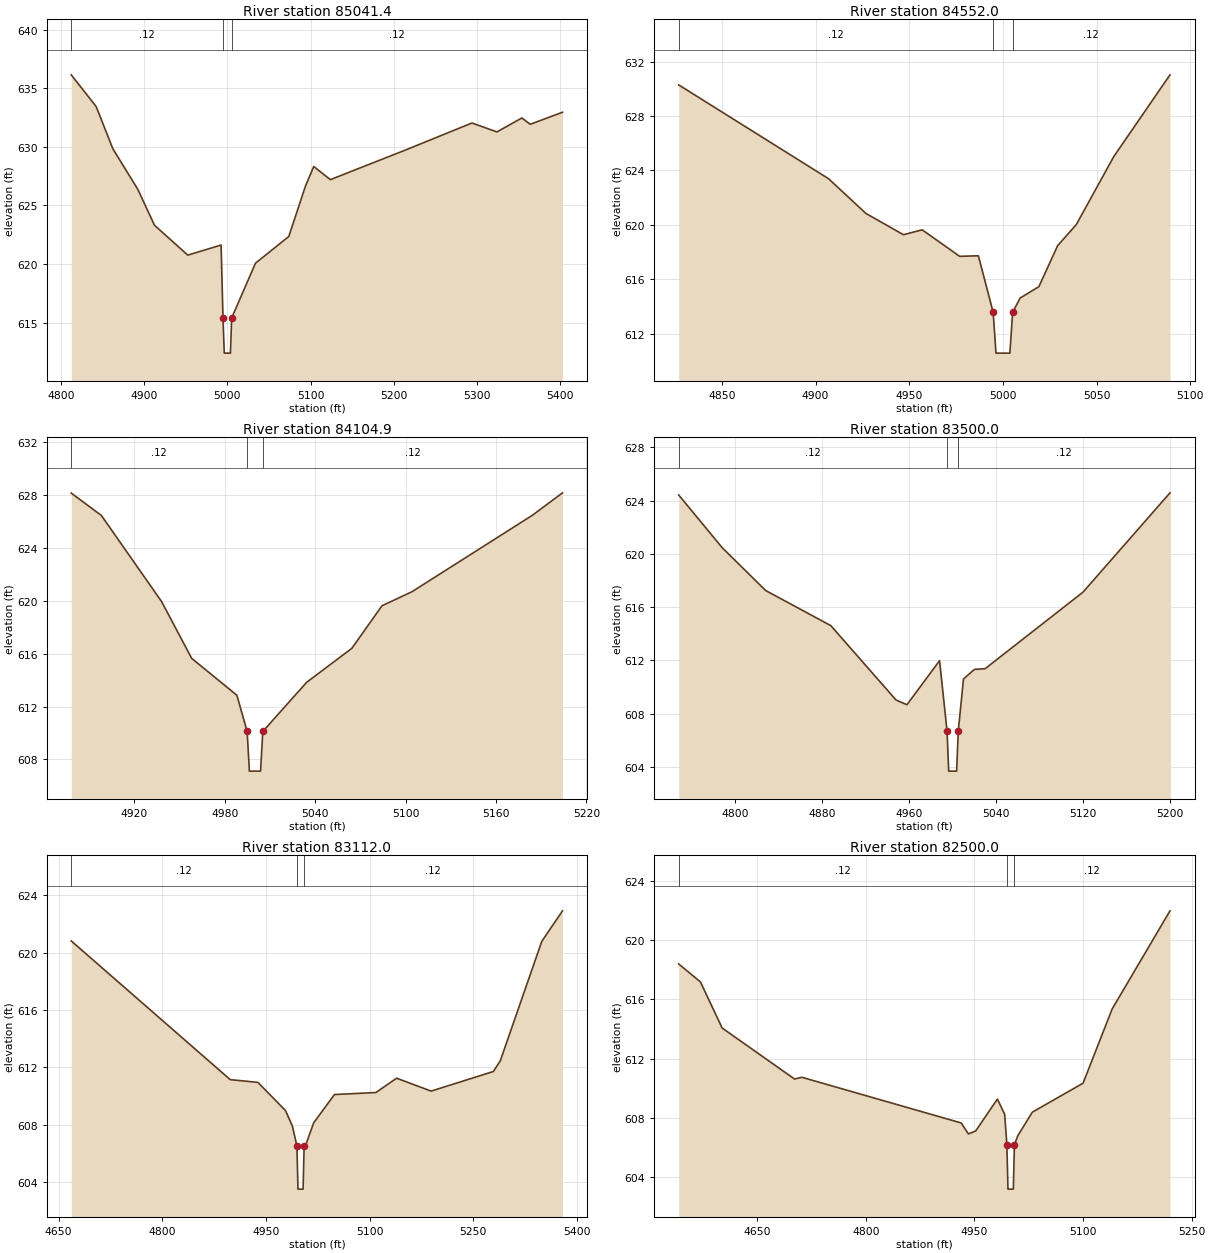
Type RM Length L Ch R = 1 ,85041.4,489.4,489.4,489.4
XS GIS Cut Line= 3
 1966196.3634825 890258.15355305 1966005.0789614 890258.15355305
 1965606.2993666 890254.91144253
BEGIN DESCRIPTION:
South Fork Little River 170.0
END DESCRIPTION:
#Sta/Elev= 22
  4812.5  636.14  4842.5  633.43  4862.5  629.83  4892.5  626.37  4912.5  623.31
  4952.5  620.76  4992.5  621.62  4994.8   615.4  4996.3   612.4  5003.7   612.4
  5005.2   615.4  5033.8  620.07  5073.8  622.35  5093.8  626.64  5103.8  628.32
  5123.8   627.2  5213.8  629.72  5293.8  632.03  5323.8  631.27  5353.8  632.46
  5363.8  631.92  5402.6  632.95
#Mann= 3 , 1 , 0
 4812.50    0.12       0  4994.8    0.04       0  5005.2    0.12       0
Bank Sta=4994.80,5005.20
Exp/Cntr=0.3,0.1

Type RM Length L Ch R = 1 ,84552.0,447.1,447.1,447.1
XS GIS Cut Line= 3
 1966147.7318246 890063.62692145 1966112.0686088 889895.03717406
 1966084.3300262 889809.40937581
BEGIN DESCRIPTION:
South Fork Little River 169.0
END DESCRIPTION:
#Sta/Elev= 17
  4826.9  630.29  4906.9  623.39  4926.9  620.83  4946.9  619.27  4956.9  619.63
  4976.9  617.68  4986.9  617.72  4994.8  613.56  4996.3  610.56  5003.7  610.56
  5005.2  613.56  5009.2  614.61  5019.2  615.45  5029.2  618.46  5039.2  620.02
  5059.2  625.02  5089.2  631.03
#Mann= 3 , 1 , 0
 4826.90    0.12       0  4994.8    0.04       0  5005.2    0.12       0
Bank Sta=4994.80,5005.20
Exp/Cntr=0.3,0.1

Type RM Length L Ch R = 1 ,84104.9,604.9,604.9,604.9
XS GIS Cut Line= 3
 1966515.7487440 889851.53030436 1966497.8797615 889726.44742667
 1966468.7007667 889528.67868453
BEGIN DESCRIPTION:
South Fork Little River 168.0
END DESCRIPTION:
#Sta/Elev= 15
    4878  628.16    4898  626.47    4938  619.95    4958  615.65    4988  612.86
  4994.8  610.12  4996.3  607.12  5003.7  607.12  5005.2  610.12  5034.3  613.84
  5064.3  616.41  5084.3  619.63  5104.3   620.7  5184.3  626.49  5204.2  628.18
#Mann= 3 , 1 , 0
 4878.00    0.12       0  4994.8    0.04       0  5005.2    0.12       0
Bank Sta=4994.80,5005.20
Exp/Cntr=0.3,0.1

Type RM Length L Ch R = 1 ,83500.0,388,388,388
XS GIS Cut Line= 3
 1967022.9056467 889450.87597367 1966830.8466183 889287.73028571
 1966676.1771321 889160.93124719
BEGIN DESCRIPTION:
South Fork Little River 167.0
END DESCRIPTION:
#Sta/Elev= 16
    4748  624.43    4788  620.47    4828  617.25    4888  614.61    4948  609.02
    4958  608.67    4988  611.98  4994.9  606.68  4996.4  603.68  5003.7  603.68
  5005.2  606.68    5010   610.6    5020  611.32    5030  611.38    5120  617.13
    5200  624.59
#Mann= 3 , 1 , 0
 4748.00    0.12       0  4994.9    0.04       0  5005.2    0.12       0
Bank Sta=4994.90,5005.20
Exp/Cntr=0.3,0.1

Type RM Length L Ch R = 1 ,83112.0,612,612,612
XS GIS Cut Line= 3
 1967107.3965405 889279.03617398 1967013.3753352 888951.58301077
 1966778.1533784 888665.95634889
BEGIN DESCRIPTION:
South Fork Little River 166.0
END DESCRIPTION:
#Sta/Elev= 20
  4668.3  620.82  4898.3  611.14  4938.3  610.95  4978.3  608.98  4988.3  607.89
  4994.8   606.5  4996.3   603.5  5003.7   603.5  5005.2   606.5  5008.3  606.68
    5009  606.78    5019  608.12    5049   610.1    5109  610.24    5139  611.24
    5189  610.34    5279  611.71    5289  612.46    5349  620.79    5379  622.92
#Mann= 3 , 1 , 0
 4668.30    0.12       0  4994.8    0.04       0  5005.2    0.12       0
Bank Sta=4994.80,5005.20
Exp/Cntr=0.3,0.1

Type RM Length L Ch R = 1 ,82500.0,642,642,642
XS GIS Cut Line= 3
 1967528.8709090 889214.19396344 1967517.3400099 888756.03922424
 1967512.9721039 888536.08122412
BEGIN DESCRIPTION:
South Fork Little River 165.0
END DESCRIPTION:
#Sta/Elev= 19
  4541.7  618.39  4571.7  617.18  4601.7  614.07  4701.7  610.63  4711.7  610.75
  4931.7  607.67  4941.7  606.93  4951.7  607.13  4981.7  609.28  4991.7  608.26
  4994.8  606.21  4996.3  603.21  5003.7  603.21  5005.2  606.21    5010  606.82
    5030   608.4    5100  610.35    5140  615.34    5220  621.97
#Mann= 3 , 1 , 0
 4541.70    0.12       0  4994.8    0.04       0  5005.2    0.12       0
Bank Sta=4994.80,5005.20
Exp/Cntr=0.5,0.3

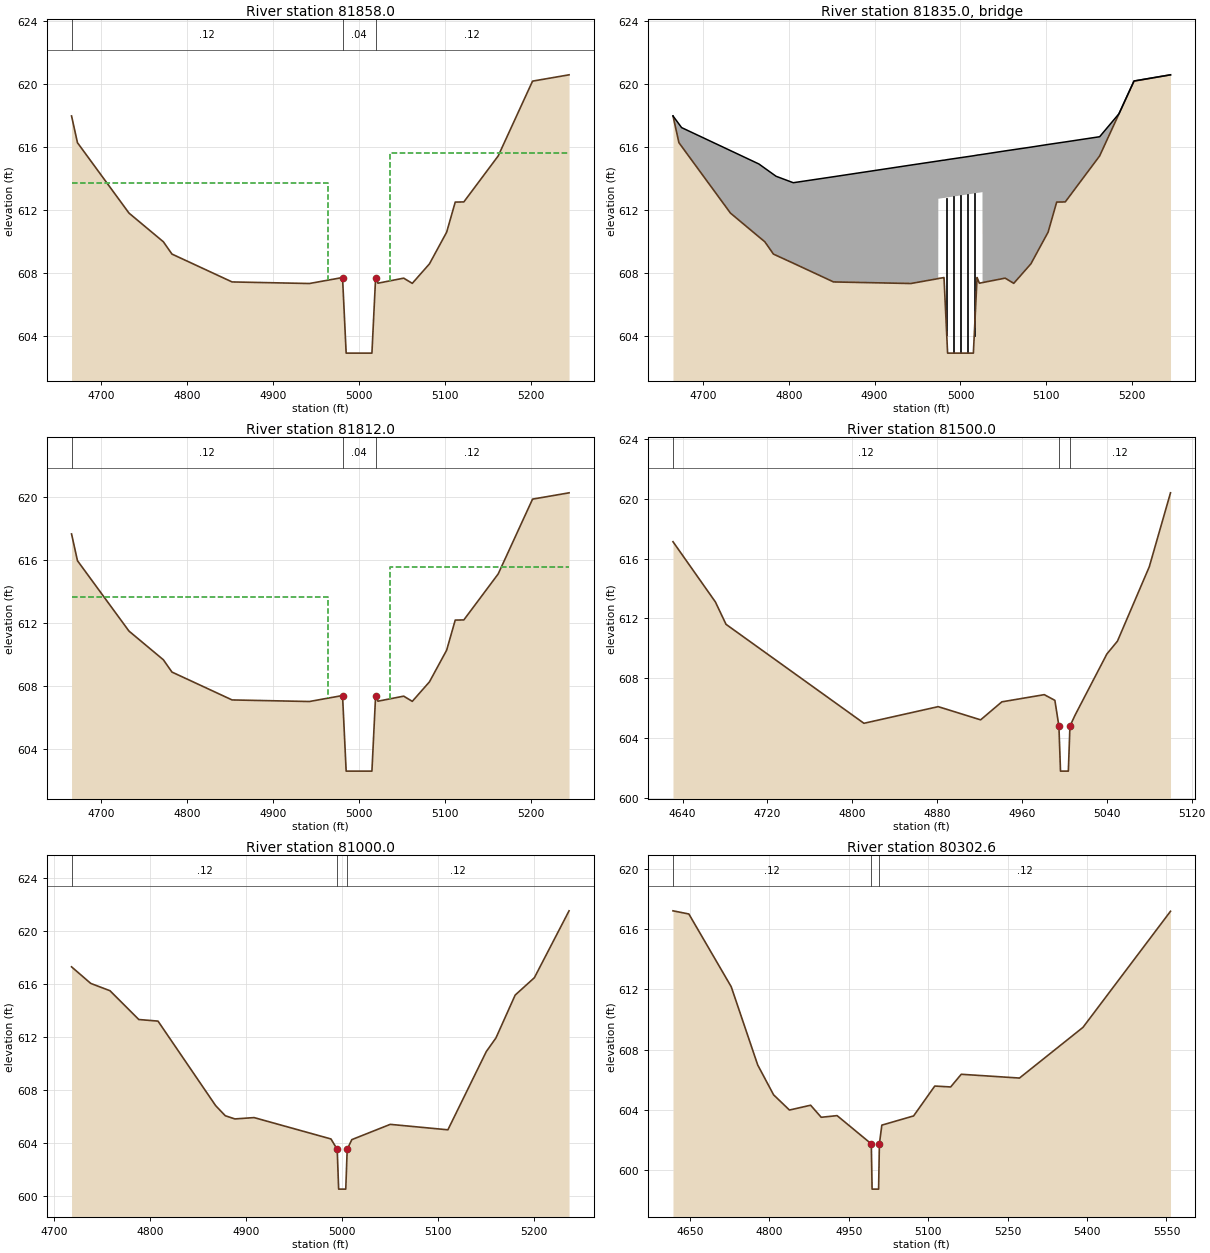
Type RM Length L Ch R = 1 ,81858.0,46,46,46
XS GIS Cut Line= 3
 1968037.0123726 889269.33926993 1968054.3234915 888930.53594351
 1968064.3964288 888690.80003570
BEGIN DESCRIPTION:
Upstream Section of Bridge/Culvert/Weir
END DESCRIPTION:
#Sta/Elev= 21
  4665.3  617.96  4672.2  616.26  4732.2  611.79  4772.2  609.97  4782.2  609.19
  4852.2  607.42  4942.2  607.32  4980.8   607.7    4985   602.9    5015   602.9
  5019.3   607.7    5022  607.34    5052  607.66    5062  607.33    5082  608.57
    5102  610.58    5112  612.49    5122   612.5    5162  615.42    5202  620.17
  5244.5  620.57
#Mann= 3 , 1 , 0
 4665.30    0.12       0  4980.8    0.04       0  5019.3    0.12       0
#XS Ineff= 2 , 0
       0    4964   613.7  5035.8       0   615.6
Bank Sta=4980.80,5019.30
Exp/Cntr=0.5,0.3

Type RM Length L Ch R = 3 ,81835.0,,,
BEGIN DESCRIPTION:
Wilkinson Road-TOR
Structure ID: Wilkinson Road (SFLR)-Bridge
Approximate Survey Structure
END DESCRIPTION:
Bridge Culvert--1,0,-1,-1, 0
Deck Dist Width WeirC Skew NumUp NumDn MinLoCord MaxHiCord MaxSubmerge Is_Ogee
10,26,2.6,,32,32,,,0.95,0,1,1,,
  4665.3  4672.2  4675.3  4732.2  4765.3  4772.2  4782.2  4785.3  4805.3  4852.2
  4942.2 4974.11  4974.2    4980  4980.8    4985    5015  5019.3    5020    5022
 5025.59  5025.7    5052    5062    5082    5102    5112    5122    5162  5184.5
    5202  5244.5
  617.96  617.45  617.22  615.76  614.91  614.64  614.25  614.13  613.72   614.1
  614.84   615.1   615.1  615.15  615.15  615.19  615.43  615.47  615.48  615.49
  615.52  615.52  615.74  615.82  615.98  616.15  616.23  616.31  616.64   618.1
  620.18  620.57
  617.96  616.26  616.03  611.79  610.28  609.97  609.19  609.11  608.61  607.42
  607.32  607.63   612.7  612.75  612.75  612.79  613.03  613.07  613.08  613.09
  613.12  607.38  607.66  607.33  608.57  610.58  612.49   612.5  615.42  618.09
  620.17  620.57
  4665.3  4672.2  4675.3  4732.2  4765.3  4772.2  4782.2  4785.3  4805.3  4852.2
  4942.2 4974.11  4974.2    4980  4980.8    4985    5015  5019.3    5020    5022
 5025.59  5025.7    5052    5062    5082    5102    5112    5122    5162  5184.5
    5202  5244.5
  617.96  617.45  617.22  615.76  614.91  614.64  614.25  614.13  613.72   614.1
  614.84   615.1   615.1  615.15  615.15  615.19  615.43  615.47  615.48  615.49
  615.52  615.52  615.74  615.82  615.98  616.15  616.23  616.31  616.64   618.1
  620.18  620.57
  617.71  616.01  615.78  611.54  610.03  609.72  608.94  608.86  608.36  607.17
  607.07  607.38  612.45   612.5   612.5  612.54  612.78  612.82  612.83  612.84
  612.87  607.13  607.41  607.08  608.32  610.33  612.24  612.25  615.17  617.84
  619.92  620.32
Pier Skew, UpSta & Num, DnSta & Num=,4984.0, 2 ,4984.0, 2 , 0 , 0 , 0 ,,
       1       1
  602.47  613.79
       1       1
  602.22  613.54
Pier Skew, UpSta & Num, DnSta & Num=,4992.0, 2 ,4992.0, 2 , 0 , 0 , 0 ,,
       1       1
   601.9  613.85
       1       1
  601.65   613.6
Pier Skew, UpSta & Num, DnSta & Num=,5000.0, 2 ,5000.0, 2 , 0 , 0 , 0 ,,
       1       1
   601.9  613.91
       1       1
  601.65  613.66
Pier Skew, UpSta & Num, DnSta & Num=,5008.0, 2 ,5008.0, 2 , 0 , 0 , 0 ,,
       1       1
   601.9  613.98
       1       1
  601.65  613.73
Pier Skew, UpSta & Num, DnSta & Num=,5016.0, 2 ,5016.0, 2 , 0 , 0 , 0 ,,
       1       1
  602.46  614.04
       1       1
  602.21  613.79
Abutment Skew #Up #Dn=, 2 , 2
 4974.00 4980.00
  612.70  607.69
 4974.00 4980.00
  612.45  607.44
Abutment Skew #Up #Dn=, 2 , 2
 5020.00 5025.79
  607.61  613.12
 5020.00 5025.79
  607.36  612.87
BR Coef= 1 , 1 , 0 ,1.25, 0 ,,,0.8,0,2,0,
Wspro=,,,, 1 ,,,, 0 ,,,, 0 ,,,,-1 ,-1 ,-1 , 0 , 0 , 0 , 0 , 0
BC Design=,, 0 ,, 0 ,,,,,,
BR U #Sta/Elev= 32
  4665.3  617.96  4672.2  616.26  4675.3  616.03  4732.2  611.79  4765.3  610.28
  4772.2  609.97  4782.2  609.19  4785.3  609.11  4805.3  608.61  4852.2  607.42
  4942.2  607.32 4974.11  607.63  4974.2  607.64    4980  607.69  4980.8   607.7
    4985   602.9    5015   602.9  5019.3   607.7    5020  607.61    5022  607.34
 5025.59  607.38  5025.7  607.38    5052  607.66    5062  607.33    5082  608.57
    5102  610.58    5112  612.49    5122   612.5    5162  615.42  5184.5  618.09
    5202  620.17  5244.5  620.57
BR U #Mann= 3
 4665.30    0.12  4980.8    0.04  5019.3    0.12
BR U Banks=4980.80,5019.30
BR D #Sta/Elev= 32
  4665.3  617.71  4672.2  616.01  4675.3  615.78  4732.2  611.54  4765.3  610.03
  4772.2  609.72  4782.2  608.94  4785.3  608.86  4805.3  608.36  4852.2  607.17
  4942.2  607.07 4974.11  607.38  4974.2  607.39    4980  607.44  4980.8  607.45
    4985  602.65    5015  602.65  5019.3  607.45    5020  607.36    5022  607.09
 5025.59  607.13  5025.7  607.13    5052  607.41    5062  607.08    5082  608.32
    5102  610.33    5112  612.24    5122  612.25    5162  615.17  5184.5  617.84
    5202  619.92  5244.5  620.32
BR D #Mann= 3
 4665.30    0.12  4980.8    0.04  5019.3    0.12
BR D Banks=4980.80,5019.30

Type RM Length L Ch R = 1 ,81812.0,312,312,312
XS GIS Cut Line= 3
 1968082.9910707 889270.73902734 1968100.3021896 888931.93570092
 1968110.3751269 888692.19979311
BEGIN DESCRIPTION:
Downstream Section of Bridge/Culvert/Weir
END DESCRIPTION:
#Sta/Elev= 21
  4665.3  617.68  4672.2  615.98  4732.2  611.51  4772.2  609.69  4782.2  608.91
  4852.2  607.14  4942.2  607.04  4980.8  607.42    4985  602.62    5015  602.62
  5019.3  607.42    5022  607.06    5052  607.38    5062  607.05    5082  608.29
    5102   610.3    5112  612.21    5122  612.22    5162  615.14    5202  619.89
  5244.5  620.29
#Mann= 3 , 1 , 0
 4665.30    0.12       0  4980.8    0.04       0  5019.3    0.12       0
#XS Ineff= 2 , 0
       0    4964   613.7  5035.8       0   615.6
Bank Sta=4980.80,5019.30
Exp/Cntr=0.5,0.3

Type RM Length L Ch R = 1 ,81500.0,500,500,500
XS GIS Cut Line= 3
 1968514.4725091 889149.35175291 1968369.9296361 888809.86639011
 1968330.1334716 888718.12402223
BEGIN DESCRIPTION:
South Fork Little River 163.0
END DESCRIPTION:
#Sta/Elev= 18
    4631  617.12    4671   613.1    4681  611.61    4811  605.01    4881  606.12
    4921  605.24    4941  606.44    4981  606.92    4991  606.54  4994.8  604.82
  4996.3  601.82  5003.7  601.82  5005.2  604.82    5010  605.55    5040  609.63
    5050  610.49    5080  615.45    5100  620.38
#Mann= 3 , 1 , 0
 4631.00    0.12       0  4994.8    0.04       0  5005.2    0.12       0
Bank Sta=4994.80,5005.20
Exp/Cntr=0.3,0.1

Type RM Length L Ch R = 1 ,81000.0,697.4,697.4,697.4
XS GIS Cut Line= 3
 1968913.2521039 888799.20381602 1968781.9650777  888549.9559714
 1968670.0938144 888342.06623175
BEGIN DESCRIPTION:
South Fork Little River 162.0
END DESCRIPTION:
#Sta/Elev= 22
  4718.3  617.28  4738.3  616.03  4758.3  615.48  4788.3  613.31  4808.3  613.19
  4868.3  606.82  4878.3  606.06  4888.3  605.82  4908.3  605.92  4988.3  604.31
  4994.8  603.53  4996.3  600.53  5003.7  600.53  5005.2  603.53    5010  604.26
    5050  605.41    5110     605    5150   610.9    5160  611.92    5180  615.15
    5200  616.46  5236.1   621.5
#Mann= 3 , 1 , 0
 4718.30    0.12       0  4994.8    0.04       0  5005.2    0.12       0
Bank Sta=4994.80,5005.20
Exp/Cntr=0.3,0.1

Type RM Length L Ch R = 1 ,80302.6,853.3,853.3,853.3
XS GIS Cut Line= 3
 1969123.9892881 888841.35125287 1969240.7052671 888474.99276334
 1969389.8423513 887940.04452643
BEGIN DESCRIPTION:
South Fork Little River 161.0
END DESCRIPTION:
#Sta/Elev= 21
  4617.8   617.2  4647.8  616.99  4727.8  612.17  4777.8  606.99  4807.8  605.01
  4837.8     604  4877.8  604.32  4897.8  603.52  4927.8  603.63  4992.4  601.76
  4993.9  598.76  5006.2  598.76  5007.7  601.76  5012.3     603  5072.3  603.61
  5112.3  605.59  5142.3  605.53  5162.3  606.37  5272.3  606.12  5392.3  609.48
  5557.6  617.17
#Mann= 3 , 1 , 0
 4617.80    0.12       0  4992.4    0.04       0  5007.7    0.12       0
Bank Sta=4992.40,5007.70
Exp/Cntr=0.3,0.1