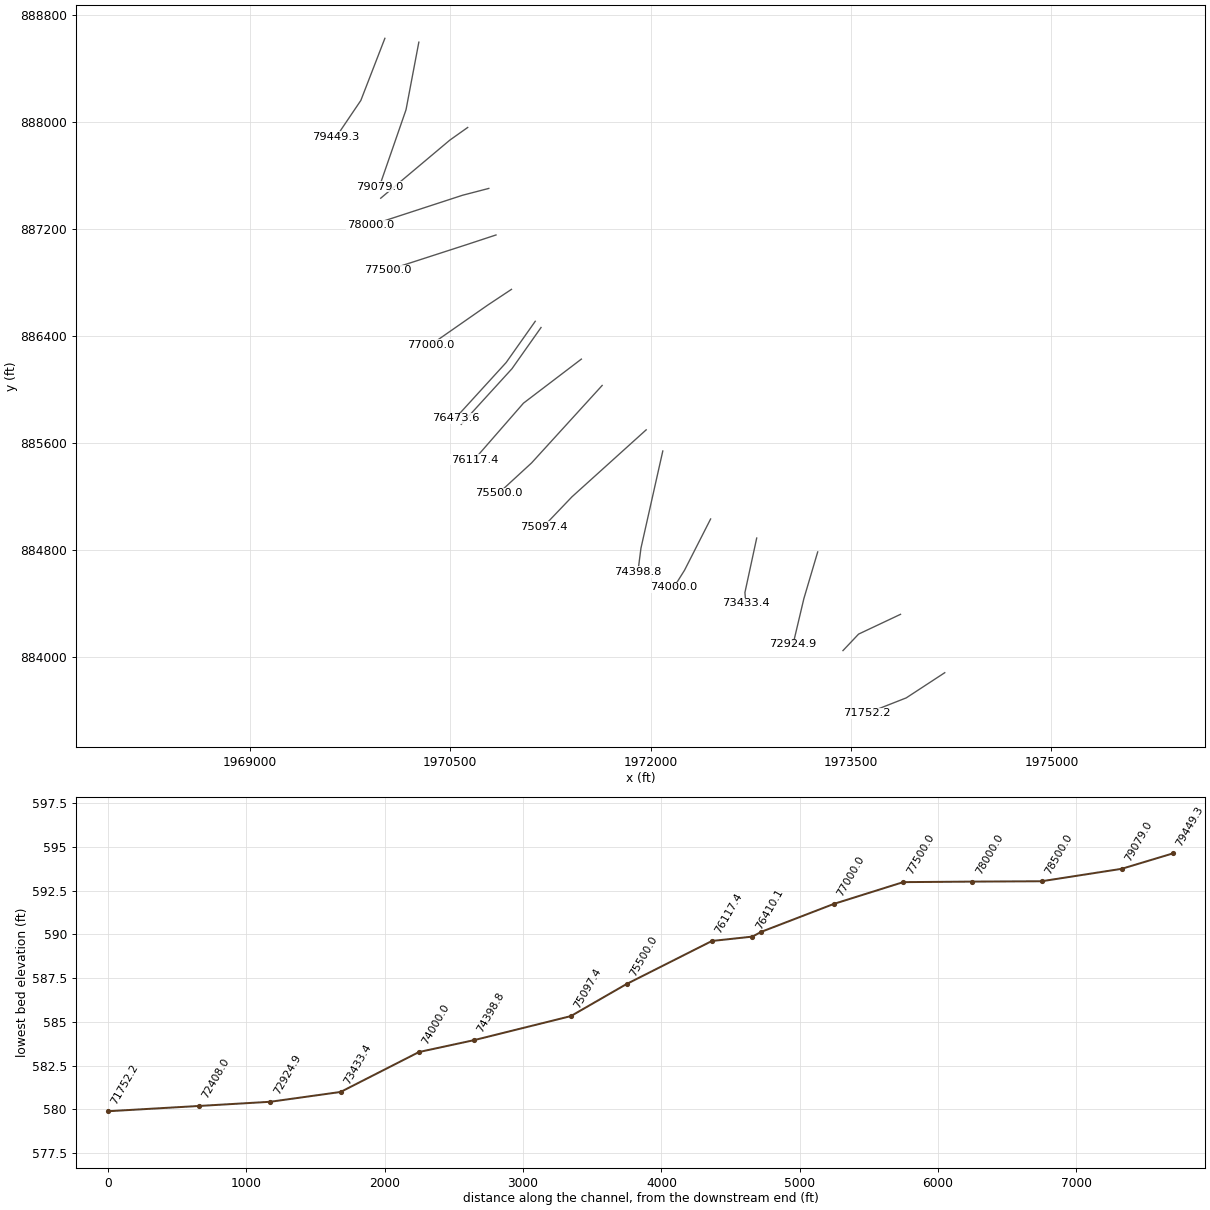
HEC-RAS study S_Fork_Little_River_FINAL.prj: South Fork Little River

--- S_Fork_Little_River_FINAL.g01 (geometry) --- (continued)

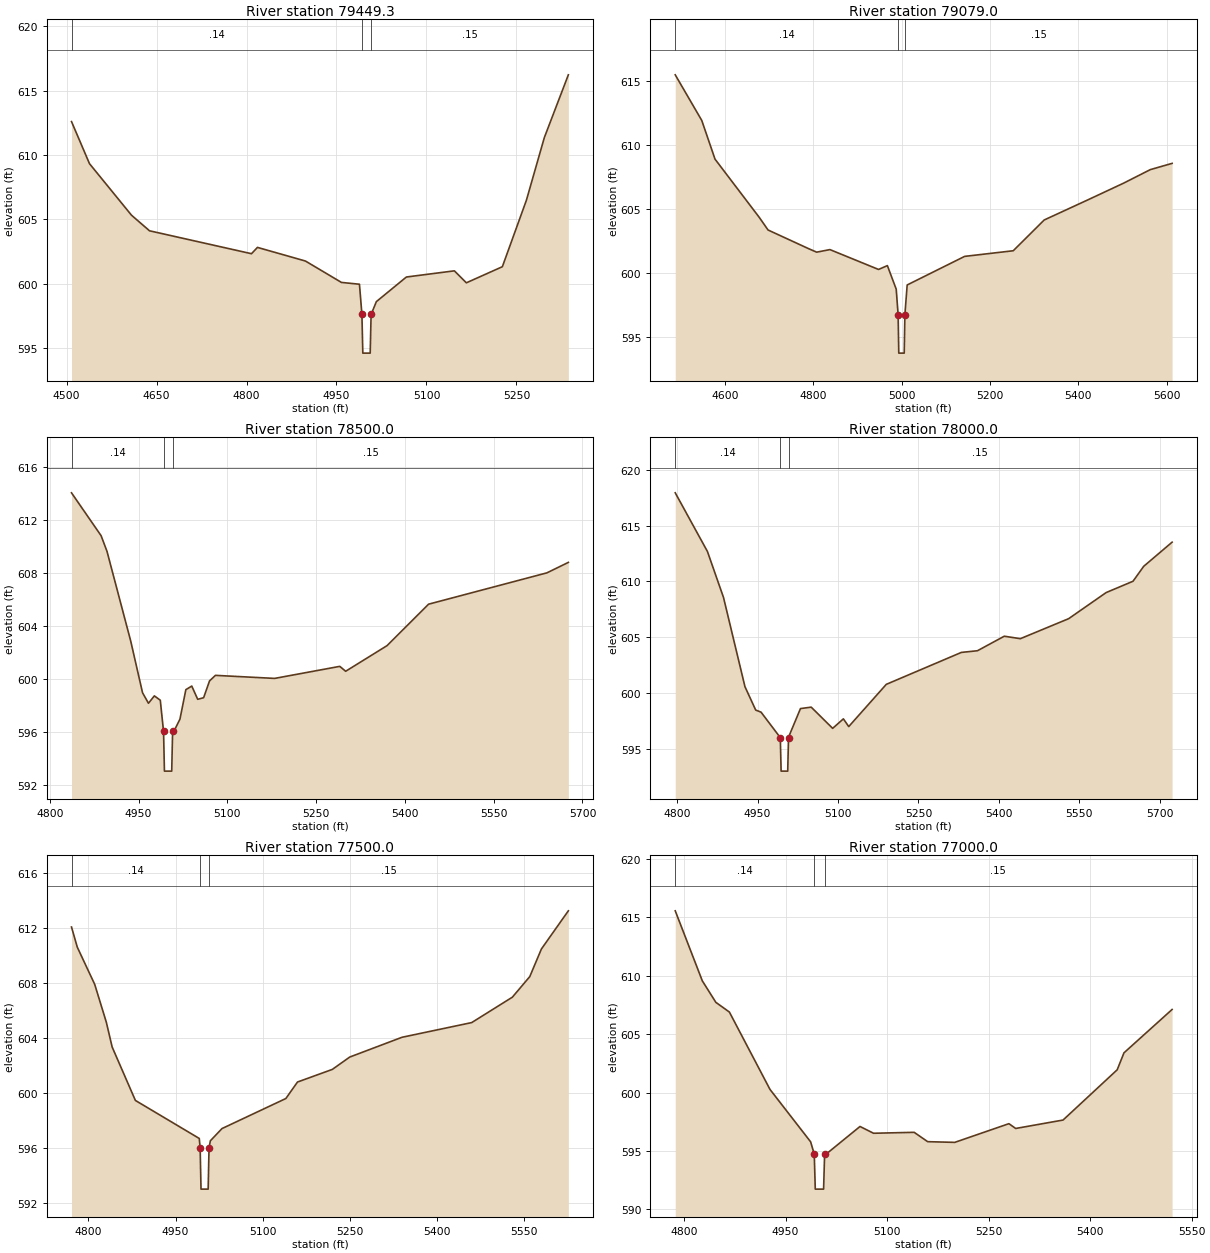
Type RM Length L Ch R = 1 ,79449.3,370.3,370.3,370.3
XS GIS Cut Line= 3
 1970010.7065172 888625.10248073  1969830.769383 888160.50804225
 1969645.8478064 887887.15974320
BEGIN DESCRIPTION:
South Fork Little River 159.0
END DESCRIPTION:
#Sta/Elev= 21
  4508.3   612.6  4538.3  609.33  4608.3  605.33  4638.3  604.12  4808.3  602.34
  4818.3  602.83  4898.3  601.77  4958.3  600.11  4988.3  599.97  4992.4  597.62
  4993.9  594.62  5006.2  594.62  5007.7  597.62  5016.5  598.62  5066.5  600.53
  5146.5  601.01  5166.5  600.08  5226.5  601.33  5266.5  606.48  5296.5  611.36
  5336.5  616.23
#Mann= 3 , 1 , 0
 4508.30    0.14       0  4992.4   0.045       0  5007.7    0.15       0
Bank Sta=4992.40,5007.70
Exp/Cntr=0.3,0.1

Type RM Length L Ch R = 1 ,79079.0,579,579,579
XS GIS Cut Line= 3
 1970264.8879825  888596.5719081 1970168.9215109 888090.80266592
 1969969.2075024 887515.00383637
BEGIN DESCRIPTION:
South Fork Little River 158.0
END DESCRIPTION:
#Sta/Elev= 23
    4488  615.46    4548   611.9    4578  608.88    4678  604.34    4698  603.35
    4788  601.92    4808  601.62    4838  601.82    4948  600.27    4968  600.57
    4988  598.73  4992.3  596.74  4993.8  593.74  5006.1  593.74  5007.6  596.74
  5012.8  599.06  5142.8  601.29  5252.8  601.73  5322.8  604.13  5422.8  605.72
  5502.8  607.01  5562.8  608.06  5612.2  608.55
#Mann= 3 , 1 , 0
 4488.00    0.14       0  4992.3   0.045       0  5007.6    0.15       0
Bank Sta=4992.30,5007.60
Exp/Cntr=0.3,0.1

Type RM Length L Ch R = 1 ,78500.0,500,500,500
XS GIS Cut Line= 3
 1970630.5980499 887958.52455643 1970497.4294963 887864.26603231
 1969979.5822561 887429.41211847
BEGIN DESCRIPTION:
South Fork Little River 157.0
END DESCRIPTION:
#Sta/Elev= 27
  4836.8  614.07  4886.8  610.83  4896.8  609.64  4936.8  602.87  4956.8  598.96
  4966.8  598.16  4976.8  598.72  4986.8  598.39  4992.3  596.03  4993.8  593.03
  5006.1  593.03  5007.6  596.03    5010  596.06    5020  596.96    5030  599.19
    5040  599.46    5050  598.46    5060  598.58    5070  599.85    5080  600.27
    5180  600.04    5290  600.95    5300  600.58    5370  602.52    5440  605.65
    5640  608.02  5676.2  608.81
#Mann= 3 , 1 , 0
 4836.80    0.14       0  4992.3   0.045       0  5007.6    0.15       0
Bank Sta=4992.30,5007.60
Exp/Cntr=0.3,0.1

Type RM Length L Ch R = 1 ,78000.0,500,500,500
XS GIS Cut Line= 3
 1970788.5028501 887502.56447884 1970591.5583274 887451.32183653
 1969904.3652919  887227.1044216
BEGIN DESCRIPTION:
South Fork Little River 156.0
END DESCRIPTION:
#Sta/Elev= 26
  4796.5  617.93  4856.5  612.68  4886.5  608.56  4926.5  600.57  4946.5  598.48
  4956.5  598.29  4992.4  596.01  4993.9  593.01  5006.2  593.01  5007.7  596.01
    5010  596.31    5030  598.61    5050  598.74    5090  596.84    5110  597.69
    5120     597    5190  600.78    5330  603.64    5360  603.79    5410  605.09
    5440  604.87    5530  606.66    5600     609    5650  610.01    5670  611.35
  5722.9  613.51
#Mann= 3 , 1 , 0
 4796.50    0.14       0  4992.4   0.045       0  5007.7    0.15       0
Bank Sta=4992.40,5007.70
Exp/Cntr=0.3,0.1

Type RM Length L Ch R = 1 ,77500.0,500,500,500
XS GIS Cut Line= 3
 1970842.4748164 887154.40646446 1970624.8639840 887082.75788726
 1970028.8623361 886889.92492682
BEGIN DESCRIPTION:
South Fork Little River 155.0
END DESCRIPTION:
#Sta/Elev= 23
  4770.9  612.07  4780.9   610.6  4810.9  607.89  4830.9  605.13  4840.9  603.33
  4880.9  599.44  4990.9  596.67  4992.4  595.98  4993.9  592.98  5006.2  592.98
  5007.7  595.98    5010   596.5    5030  597.39    5140  599.58    5160  600.78
    5220   601.7    5250   602.6    5340  604.04    5460  605.11    5530  606.96
    5560  608.46    5580  610.47  5626.4  613.25
#Mann= 3 , 1 , 0
 4770.90    0.14       0  4992.4   0.045       0  5007.7    0.15       0
Bank Sta=4992.40,5007.70
Exp/Cntr=0.3,0.1

Type RM Length L Ch R = 1 ,77000.0,526.45,526.45,526.45
XS GIS Cut Line= 3
 1970958.2699023 886747.64125846 1970780.7151224  886629.9731112
 1970353.0733888 886332.28191622
BEGIN DESCRIPTION:
South Fork Little River 154.0
END DESCRIPTION:
#Sta/Elev= 22
    4787  615.55    4827  609.56    4847  607.72    4867  606.89    4927  600.27
    4987  595.79  4992.4  594.74  4993.9  591.74  5006.2  591.74  5007.7  594.74
    5010  594.74    5060   597.1    5080  596.52    5140   596.6    5160   595.8
    5200  595.74    5280  597.34    5290  596.93    5360  597.65    5440  601.95
    5450   603.4  5521.1  607.11
#Mann= 3 , 1 , 0
 4787.00    0.14       0  4992.4   0.045       0  5007.7    0.15       0
Bank Sta=4992.40,5007.70
Exp/Cntr=0.5,0.3

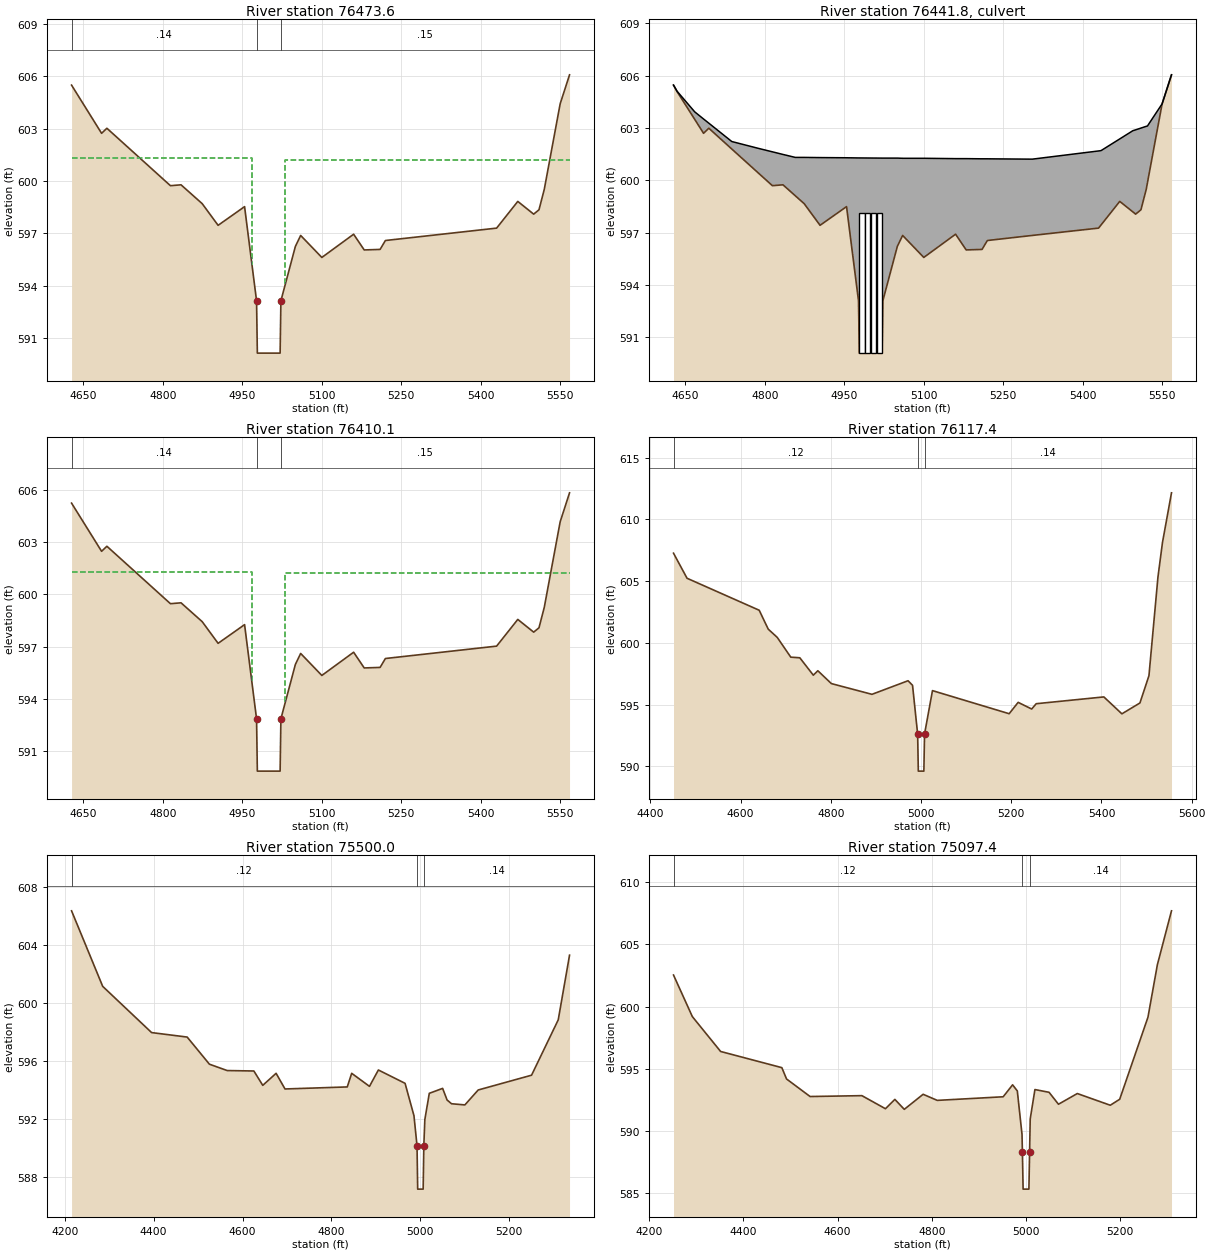
Type RM Length L Ch R = 1 ,76473.6,63.5,63.5,63.5
XS GIS Cut Line= 3
 1971136.1832219 886508.68109082 1970918.6118617 886200.45499717
 1970538.9825896 885784.67055630
BEGIN DESCRIPTION:
Upstream Section of Bridge/Culvert/Weir
END DESCRIPTION:
#Sta/Elev= 26
  4627.7  605.49  4684.4  602.73  4694.4  603.02  4814.4  599.73  4834.4  599.78
  4874.4   598.7  4904.4  597.46  4954.4  598.53    4977  593.14  4978.5  590.14
  5021.5  590.14    5023  593.14  5050.3  596.25  5060.3  596.88  5100.3  595.62
  5160.3  596.95  5180.3  596.05  5210.3  596.08  5220.3  596.59  5430.3   597.3
  5470.3  598.83  5500.3   598.1  5510.3  598.35  5520.3  599.52  5550.3  604.42
    5568  606.08
#Mann= 3 , 1 , 0
 4627.70    0.14       0    4977   0.045       0    5023    0.15       0
#XS Ineff= 2 , 0
       0  4968.5   601.3  5031.5       0   601.2
Bank Sta=4977.00,5023.00
Exp/Cntr=0.5,0.3

Type RM Length L Ch R = 2 ,76441.8,,,
BEGIN DESCRIPTION:
Walnut Grove Ch Road (SFLR)-TOR
Structure ID: Walnut Grove Ch Road (SFLR)-Culvert
Approximate Survey Structure
END DESCRIPTION:
Bridge Culvert--1,0,-1,-1, 0
Deck Dist Width WeirC Skew NumUp NumDn MinLoCord MaxHiCord MaxSubmerge Is_Ogee
10,43.5,3,,35,35,,,0.95,0,1,1,,
  4627.7  4634.4  4667.7  4684.4  4694.4  4737.7  4787.7  4814.4  4834.4  4857.7
  4874.4  4904.4  4954.4    4977  4978.5  5021.5    5023  5050.3  5060.3  5100.3
  5160.3  5180.3  5210.3  5220.3    5305  5430.3    5435  5470.3    5495  5500.3
  5510.3  5520.3  5522.6  5550.3    5568
  605.45   605.1  603.92  603.51  603.27  602.22  601.83  601.63  601.48  601.31
  601.31   601.3  601.29  601.28  601.28  601.27  601.27  601.27  601.26  601.26
  601.24  601.24  601.23  601.23  601.21  601.68   601.7  602.37  602.84  602.89
  602.99  603.09  603.11  604.38  606.04
  605.45  605.08  603.49  602.69  602.98  601.79  600.42  599.69  599.74  599.11
  598.66  597.42  598.49   593.1   590.1   590.1   593.1  596.21  596.84  595.58
  596.91  596.01  596.04  596.55  596.84  597.26  597.44  598.79  598.19  598.06
  598.31  599.48  599.86  604.38  606.04
  4627.7  4634.4  4667.7  4684.4  4694.4  4737.7  4787.7  4814.4  4834.4  4857.7
  4874.4  4904.4  4954.4    4977  4978.5  5021.5    5023  5050.3  5060.3  5100.3
  5160.3  5180.3  5210.3  5220.3    5305  5430.3    5435  5470.3    5495  5500.3
  5510.3  5520.3  5522.6  5550.3    5568
  605.34   605.1  603.92  603.51  603.27  602.22  601.83  601.63  601.48  601.31
  601.31   601.3  601.29  601.28  601.28  601.27  601.27  601.27  601.26  601.26
  601.24  601.24  601.23  601.23  601.21  601.68   601.7  602.37  602.84  602.89
  602.99  603.09  603.11  604.27  605.93
  605.23  604.86  603.27  602.47  602.76  601.57   600.2  599.47  599.52  598.89
  598.44   597.2  598.27  592.88  589.88  589.88  592.88  595.99  596.62  595.36
  596.69  595.79  595.82  596.33  596.62  597.04  597.22  598.57  597.97  597.84
  598.09  599.26  599.64  604.16  605.82
BR Coef= 1 , 0 , 0 ,1.25, 0 ,,,0.8,-1,2,0,
Wspro=,,,, 1 ,,,, 0 ,,,, 0 ,,,,-1 ,-1 ,-1 , 0 , 0 , 0 , 0 , 0
Culvert=2,8.0,10.0,43.5,0.015,0.4,1.0,8,1,590.10,4983.50,589.88,4983.50,Culvert #1  ,0,10
Culvert=2,8.0,10.0,43.5,0.015,0.4,1.0,8,1,590.10,4994.50,589.88,4994.50,Culvert #2  ,0,10
Culvert=2,8.0,10.0,43.5,0.015,0.4,1.0,8,1,590.10,5005.50,589.88,5005.50,Culvert #3  ,0,10
Culvert=2,8.0,10.0,43.5,0.015,0.4,1.0,8,1,590.10,5016.50,589.88,5016.50,Culvert #4  ,0,10
BC Design=,, 0 ,, 0 ,,,,,,
BR U #Sta/Elev= 35
  4627.7  605.45  4634.4  605.08  4667.7  603.49  4684.4  602.69  4694.4  602.98
  4737.7  601.79  4787.7  600.42  4814.4  599.69  4834.4  599.74  4857.7  599.11
  4874.4  598.66  4904.4  597.42  4954.4  598.49    4977   593.1  4978.5   590.1
  5021.5   590.1    5023   593.1  5050.3  596.21  5060.3  596.84  5100.3  595.58
  5160.3  596.91  5180.3  596.01  5210.3  596.04  5220.3  596.55    5305  596.84
  5430.3  597.26    5435  597.44  5470.3  598.79    5495  598.19  5500.3  598.06
  5510.3  598.31  5520.3  599.48  5522.6  599.86  5550.3  604.38    5568  606.04
BR U #Mann= 3
 4627.70    0.14    4977   0.045    5023    0.15
BR U Banks=4977.00,5023.00
BR D #Sta/Elev= 35
  4627.7  605.23  4634.4  604.86  4667.7  603.27  4684.4  602.47  4694.4  602.76
  4737.7  601.57  4787.7   600.2  4814.4  599.47  4834.4  599.52  4857.7  598.89
  4874.4  598.44  4904.4   597.2  4954.4  598.27    4977  592.88  4978.5  589.88
  5021.5  589.88    5023  592.88  5050.3  595.99  5060.3  596.62  5100.3  595.36
  5160.3  596.69  5180.3  595.79  5210.3  595.82  5220.3  596.33    5305  596.62
  5430.3  597.04    5435  597.22  5470.3  598.57    5495  597.97  5500.3  597.84
  5510.3  598.09  5520.3  599.26  5522.6  599.64  5550.3  604.16    5568  605.82
BR D #Mann= 3
 4627.70    0.14    4977   0.045    5023    0.15
BR D Banks=4977.00,5023.00

Type RM Length L Ch R = 1 ,76410.1,292.65,292.65,292.65
XS GIS Cut Line= 3
 1971179.5030453 886462.25218923 1970961.9316850 886154.02609558
  1970582.302413 885738.24165471
BEGIN DESCRIPTION:
Downstream Section of Bridge/Culvert/Weir
END DESCRIPTION:
#Sta/Elev= 26
  4627.7  605.22  4684.4  602.46  4694.4  602.75  4814.4  599.46  4834.4  599.51
  4874.4  598.43  4904.4  597.19  4954.4  598.26    4977  592.87  4978.5  589.87
  5021.5  589.87    5023  592.87  5050.3  595.98  5060.3  596.61  5100.3  595.35
  5160.3  596.68  5180.3  595.78  5210.3  595.81  5220.3  596.32  5430.3  597.03
  5470.3  598.56  5500.3  597.83  5510.3  598.08  5520.3  599.25  5550.3  604.15
    5568  605.81
#Mann= 3 , 1 , 0
 4627.70    0.14       0    4977   0.045       0    5023    0.15       0
#XS Ineff= 2 , 0
       0  4968.5   601.3  5031.5       0   601.2
Bank Sta=4977.00,5023.00
Exp/Cntr=0.5,0.3

Type RM Length L Ch R = 1 ,76117.4,617.4,617.4,617.4
XS GIS Cut Line= 3
 1971481.3278521 886225.94069094 1971048.1818857 885896.54226142
 1970679.8859453 885474.58730984
BEGIN DESCRIPTION:
South Fork Little River 152.0
END DESCRIPTION:
#Sta/Elev= 29
  4451.1  607.27  4481.1  605.24  4641.1  602.65  4661.1  601.12  4681.1  600.45
  4711.1  598.85  4731.1   598.8  4761.1  597.39  4771.1  597.75  4801.1  596.71
  4891.1  595.84  4971.1  596.94  4981.1  596.57  4992.4  592.62  4993.9  589.62
  5006.2  589.62  5007.7  592.62  5025.3  596.14  5195.3  594.27  5215.3  595.19
  5245.3  594.65  5255.3  595.08  5405.3  595.63  5445.3  594.26  5485.3  595.14
  5505.3  597.35  5525.3  605.35  5535.3  608.14  5555.3  612.16
#Mann= 3 , 1 , 0
 4451.10    0.12       0  4992.4   0.045       0  5007.7    0.14       0
Bank Sta=4992.40,5007.70
Exp/Cntr=0.3,0.1

Type RM Length L Ch R = 1 ,75500.0,402.6,402.6,402.6
XS GIS Cut Line= 3
 1971636.9491574 886028.82037092 1971108.4100420 885449.08167737
 1970861.4363194 885222.18327186
BEGIN DESCRIPTION:
South Fork Little River 151.0
END DESCRIPTION:
#Sta/Elev= 30
  4215.5  606.36  4285.5  601.15  4395.5  597.96  4475.5  597.65  4525.5  595.78
  4565.5  595.34  4625.5  595.31  4645.5  594.32  4675.5  595.15  4695.5  594.07
  4835.5  594.21  4845.5  595.15  4885.5  594.25  4905.5  595.38  4965.5  594.46
  4985.5  592.23  4992.4  590.16  4993.9  587.16  5006.2  587.16  5007.7  590.16
    5010  591.96    5020  593.77    5050  594.11    5060  593.31    5070  593.05
    5100  592.97    5130     594    5250  595.02    5310  598.84  5335.4   603.3
#Mann= 3 , 1 , 0
 4215.50    0.12       0  4992.4   0.045       0  5007.7    0.14       0
Bank Sta=4992.40,5007.70
Exp/Cntr=0.3,0.1

Type RM Length L Ch R = 1 ,75097.4,698.6,698.6,698.6
XS GIS Cut Line= 3
 1971966.3475869 885696.82825298 1971411.2982647 885196.24638765
 1971197.0258993 884972.23436922
BEGIN DESCRIPTION:
South Fork Little River 150.0
END DESCRIPTION:
#Sta/Elev= 30
  4251.6  602.53  4291.6  599.19  4351.6  596.39  4481.6  595.09  4491.6  594.18
  4541.6  592.77  4651.6  592.84  4701.6  591.79  4721.6  592.54  4741.6  591.74
  4781.6  592.95  4811.6  592.46  4951.6  592.75  4971.6  593.71  4981.6  593.22
  4991.6  589.72  4992.4  588.33  4993.9  585.33  5006.2  585.33  5007.7  588.33
    5009  590.97    5019  593.33    5049  593.11    5069  592.15    5109  593.01
    5179  592.07    5199  592.55    5259  599.14    5279  603.36    5309  607.69
#Mann= 3 , 1 , 0
 4251.60    0.12       0  4992.4   0.045       0  5007.7    0.14       0
Bank Sta=4992.40,5007.70
Exp/Cntr=0.3,0.1

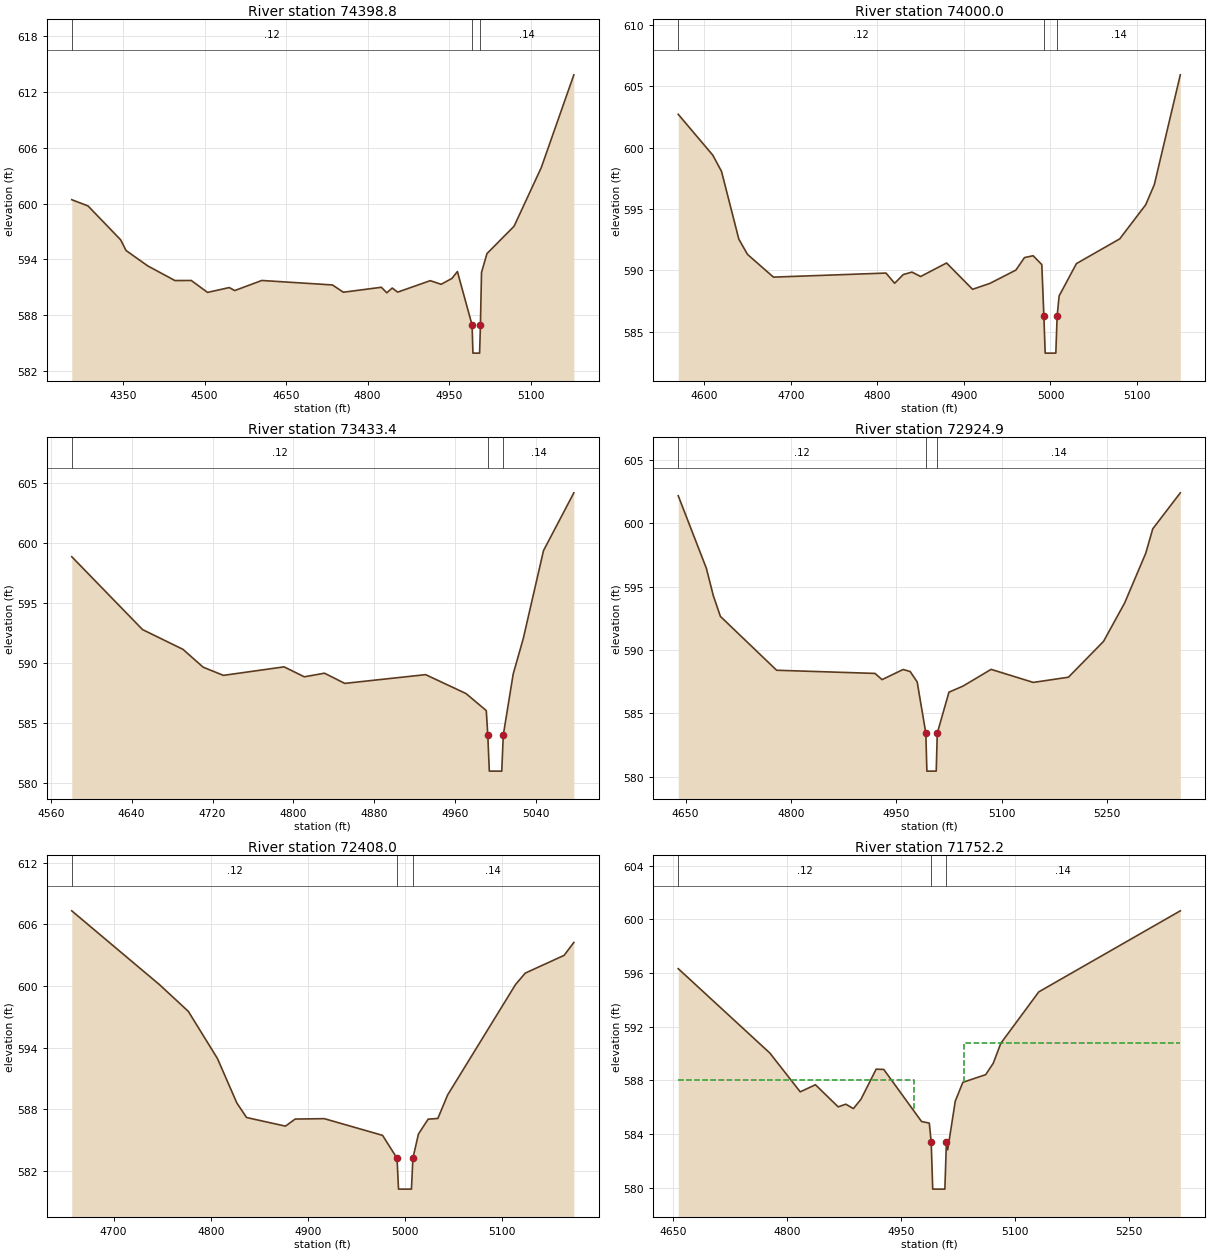
Type RM Length L Ch R = 1 ,74398.8,398.8,398.8,398.8
XS GIS Cut Line= 3
 1972090.8446311 885538.61325927 1971927.4422606 884812.38050128
 1971904.3329009 884633.80817650
BEGIN DESCRIPTION:
South Fork Little River 149.0
END DESCRIPTION:
#Sta/Elev= 30
  4255.3  600.41  4285.3  599.74  4345.3  596.11  4355.3  594.96  4395.3  593.31
  4445.3  591.74  4475.3  591.75  4505.3  590.47  4545.3  590.99  4555.3  590.67
  4605.3  591.75  4735.3  591.27  4755.3  590.49  4825.3  591.02  4835.3  590.43
  4845.3  590.94  4855.3   590.5  4915.3  591.73  4935.3  591.34  4955.3  591.97
  4965.3  592.71  4992.4  586.96  4993.9  583.96  5006.2  583.96  5007.7  586.96
  5009.7  592.61  5019.7  594.63  5069.7  597.57  5119.7  603.85  5179.7   613.8
#Mann= 3 , 1 , 0
 4255.30    0.12       0  4992.4   0.045       0  5007.7    0.14       0
Bank Sta=4992.40,5007.70
Exp/Cntr=0.3,0.1

Type RM Length L Ch R = 1 ,74000.0,566.6,566.6,566.6
XS GIS Cut Line= 3
 1972448.7736333 885030.25032868 1972253.6581634 884647.02899666
 1972174.0014179 884519.92877979
BEGIN DESCRIPTION:
South Fork Little River 148.0
END DESCRIPTION:
#Sta/Elev= 28
    4570   602.7    4610  599.37    4620  598.06    4640  592.55    4650  591.31
    4680  589.46    4810  589.79    4820  588.96    4830  589.67    4840  589.87
    4850  589.51    4880  590.61    4910  588.47    4930  588.95    4960  590.03
    4970  591.05    4980   591.2    4990  590.48  4992.4  586.28  4993.9  583.28
  5006.2  583.28  5007.7  586.28    5010  587.93    5030  590.56    5080  592.57
    5110  595.34    5120  596.99    5150  605.91
#Mann= 3 , 1 , 0
 4570.00    0.12       0  4992.4   0.045       0  5007.7    0.14       0
Bank Sta=4992.40,5007.70
Exp/Cntr=0.3,0.1

Type RM Length L Ch R = 1 ,73433.4,508.5,508.5,508.5
XS GIS Cut Line= 3
 1972793.7341933  884887.5974655 1972705.5487870 884480.38838334
 1972711.6171937 884400.71208831
BEGIN DESCRIPTION:
South Fork Little River 147.0
END DESCRIPTION:
#Sta/Elev= 20
  4580.8  598.89  4650.8  592.81  4690.8  591.16  4710.8  589.67  4730.8  588.99
  4790.8   589.7  4810.8  588.87  4830.8  589.17  4850.8  588.32  4930.8  589.05
  4970.8  587.47  4990.8  586.05  4992.3     584  4993.8     581  5006.1     581
  5007.6     584  5017.4   589.1  5027.4  592.07  5047.4   599.4  5077.4  604.22
#Mann= 3 , 1 , 0
 4580.80    0.12       0  4992.3   0.045       0  5007.6    0.14       0
Bank Sta=4992.30,5007.60
Exp/Cntr=0.3,0.1

Type RM Length L Ch R = 1 ,72924.9,516.9,516.9,516.9
XS GIS Cut Line= 3
 1973250.2233555 884783.84992865 1973146.4758187 884433.70199176
 1973066.0714776 884093.92880855
BEGIN DESCRIPTION:
South Fork Little River 146.0
END DESCRIPTION:
#Sta/Elev= 24
  4639.6  602.17  4679.6  596.45  4689.6  594.27  4699.6  592.65  4779.6   588.4
  4919.6  588.15  4929.6  587.66  4959.6  588.46  4969.6   588.3  4979.6  587.48
  4991.9  583.44  4993.4  580.44  5006.7  580.44  5008.2  583.44  5024.8  586.67
  5044.8  587.15  5084.8  588.47  5144.8  587.44  5194.8  587.85  5244.8  590.68
  5274.8  593.71  5304.8  597.63  5314.8  599.56    5354   602.4
#Mann= 3 , 1 , 0
 4639.60    0.12       0  4991.9   0.045       0  5008.2    0.14       0
Bank Sta=4991.90,5008.20
Exp/Cntr=0.3,0.1

Type RM Length L Ch R = 1 ,72408.0,655.85,655.85,655.85
XS GIS Cut Line= 3
 1973870.1148882 884316.98601279 1973556.2785892 884169.14577278
 1973439.3834219 884045.74714317
BEGIN DESCRIPTION:
South Fork Little River 145.0
END DESCRIPTION:
#Sta/Elev= 23
  4656.9  607.33  4726.9  601.75  4746.9  600.16  4776.9  597.53  4806.9  592.93
  4826.9  588.59  4836.9  587.18  4876.9  586.34  4886.9  587.03  4916.9  587.07
  4976.9  585.44  4991.8   583.2  4993.3   580.2  5006.6   580.2  5008.1   583.2
  5013.8  585.57  5023.8  587.02  5033.8  587.09  5043.8  589.37  5113.8  600.15
  5123.8  601.26  5163.8  602.99  5173.8  604.25
#Mann= 3 , 1 , 0
 4656.90    0.12       0  4991.8   0.045       0  5008.1    0.14       0
Bank Sta=4991.80,5008.10
Exp/Cntr=0.5,0.3

Type RM Length L Ch R = 1 ,71752.2,40.5,40.5,40.5
XS GIS Cut Line= 3
 1974201.1082624 883880.34643121 1973912.8082914 883691.97706871
 1973617.7765115 883576.13636983
BEGIN DESCRIPTION:
Upstream Section of Bridge/Culvert/Weir
END DESCRIPTION:
#Sta/Elev= 24
  4656.8  596.33  4777.5  590.04  4817.5  587.15  4837.5  587.68  4867.5  586.03
  4877.5  586.23  4887.5   585.9  4897.5   586.6  4917.5  588.84  4927.5  588.82
  4977.3  584.94  4987.5  584.82    4990   583.4    4992   579.9    5008   579.9
    5010   583.4  5011.7  582.83  5021.7  586.46  5031.7  587.86  5061.7  588.43
  5071.7  589.28  5081.7  590.77  5131.7   594.6  5318.1  600.64
#Mann= 3 , 1 , 0
 4656.80    0.12       0    4990   0.045       0    5010    0.14       0
#XS Ineff= 2 , 0
       0  4967.3     588  5032.6       0   590.8
Bank Sta=4990.00,5010.00
Exp/Cntr=0.5,0.3