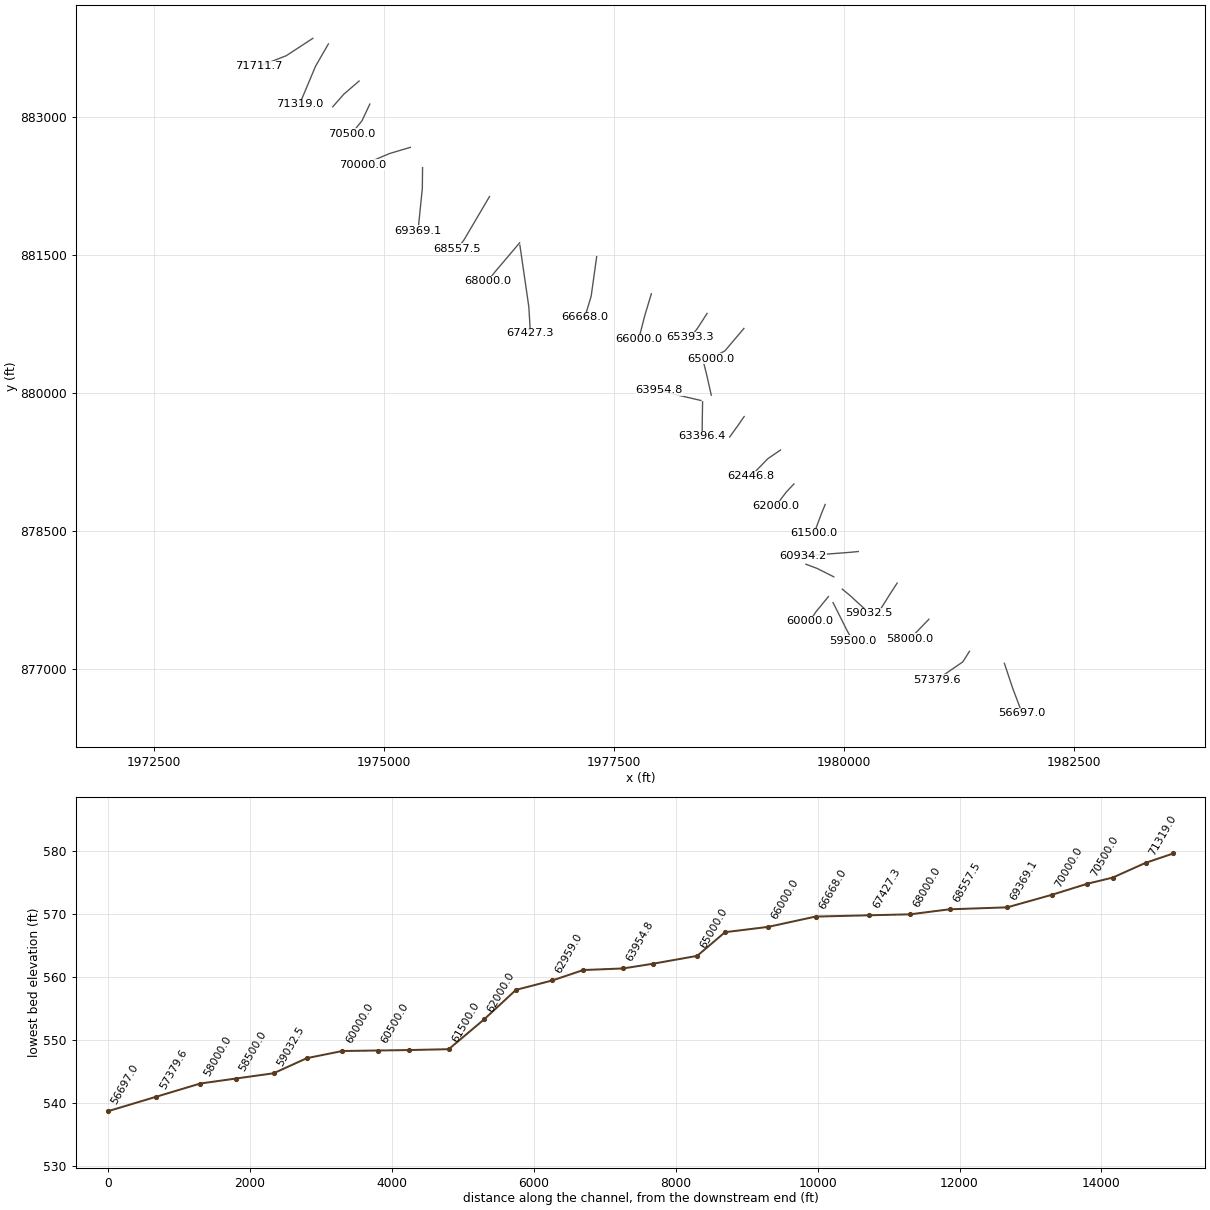
HEC-RAS study S_Fork_Little_River_FINAL.prj: South Fork Little River

--- S_Fork_Little_River_FINAL.g01 (geometry) --- (continued)

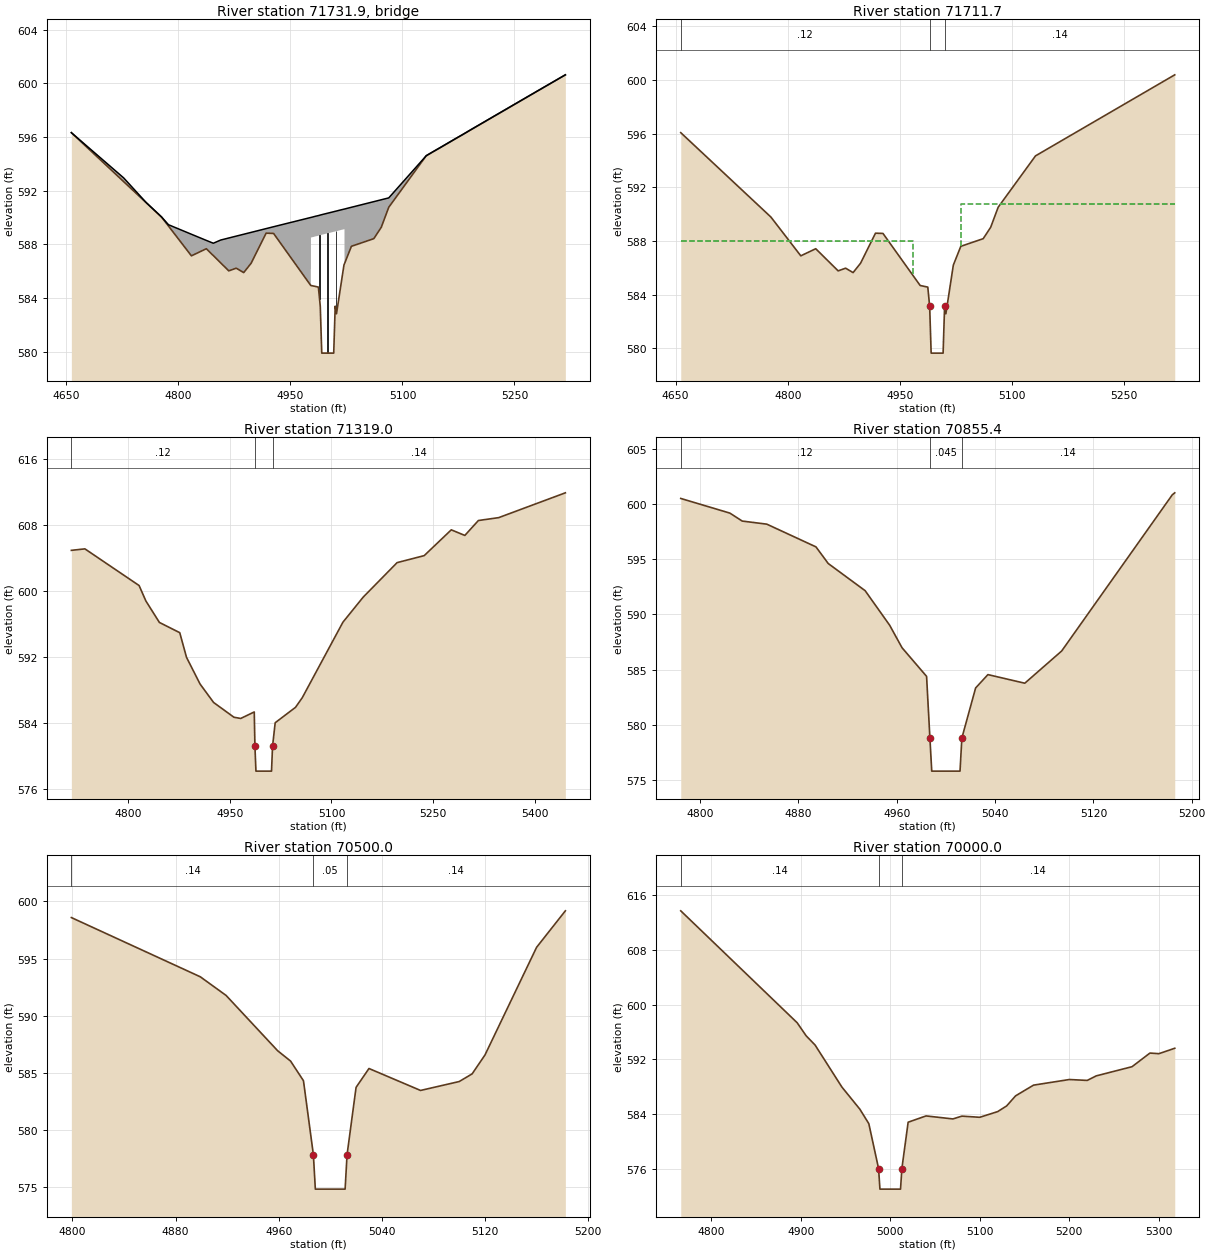
Type RM Length L Ch R = 3 ,71731.9,,,
BEGIN DESCRIPTION:
Pearson Road-TOR
Structure ID: Pearson Road (SFLR)-Bridge
Approximate Survey Structure
END DESCRIPTION:
Bridge Culvert--1,0,-1,-1, 0
Deck Dist Width WeirC Skew NumUp NumDn MinLoCord MaxHiCord MaxSubmerge Is_Ogee
10,20.5,2.6,,42,42,,,0.95,0,1,1,,
  4656.8  4726.8  4756.8  4777.5  4786.8  4817.5  4837.5  4846.8  4856.8  4867.5
  4877.5  4887.5  4897.5  4917.5  4927.5  4977.3 4977.41  4977.5  4983.5  4987.5
    4990    4992    5008    5010  5011.7  5016.5  5021.7 5022.39  5022.5  5031.7
  5061.7  5071.7  5081.7  5131.2  5131.7  5141.2  5151.2  5171.2  5181.2  5191.2
  5271.2  5318.1
  596.33  592.96  591.13  590.05  589.47  588.76   588.3  588.09  588.33  588.48
  588.62  588.76   588.9  589.18  589.32  590.01  590.01  590.01   590.1  590.15
  590.19  590.22  590.44  590.47  590.49  590.56  590.63  590.64  590.64  590.77
  591.19  591.33  591.47  594.57  594.61  594.92  595.24  595.89  596.21  596.54
  599.13  600.64
  596.33  592.68  591.12  590.04  589.37  587.15  587.68  587.17  586.62  586.03
  586.23   585.9   586.6  588.84  588.82  584.94  584.94  588.51   588.6  588.65
  588.69  588.72  588.94  588.97  588.99  589.06  589.13  589.14  586.57  587.86
  588.43  589.28  590.77  594.56   594.6  594.91  595.23  595.88   596.2  596.53
  599.12  600.64
  4656.8  4726.8  4756.8  4777.5  4786.8  4817.5  4837.5  4846.8  4856.8  4867.5
  4877.5  4887.5  4897.5  4917.5  4927.5  4977.3 4977.41  4977.5  4983.5  4987.5
    4990    4992    5008    5010  5011.7  5016.5  5021.7 5022.39  5022.5  5031.7
  5061.7  5071.7  5081.7  5131.2  5131.7  5141.2  5151.2  5171.2  5181.2  5191.2
  5271.2  5318.1
  596.33  592.96  591.13  590.05  589.47  588.76   588.3  588.09  588.33  588.48
  588.62  588.76   588.9  589.18  589.32  590.01  590.01  590.01   590.1  590.15
  590.19  590.22  590.44  590.47  590.49  590.56  590.63  590.64  590.64  590.77
  591.19  591.33  591.47  594.57  594.61  594.92  595.24  595.89  596.21  596.54
  599.13  600.64
  596.08  592.43  590.87  589.79  589.12   586.9  587.43  586.92  586.37  585.78
  585.98  585.65  586.35  588.59  588.57  584.69  584.69  588.26  588.35   588.4
  588.44  588.47  588.69  588.72  588.74  588.81  588.88  588.89  586.32  587.61
  588.18  589.03  590.52  594.31  594.35  594.66  594.98  595.63  595.95  596.28
  598.87  600.39
Pier Skew, UpSta & Num, DnSta & Num=,4989.0, 2 ,4989.0, 2 , 0 , 0 , 0 ,,
       1       1
  582.68  589.68
       1       1
  582.43  589.43
Pier Skew, UpSta & Num, DnSta & Num=,5000.0, 2 ,5000.0, 2 , 0 , 0 , 0 ,,
       1       1
   578.9  589.84
       1       1
  578.65  589.59
Pier Skew, UpSta & Num, DnSta & Num=,5011.0, 2 ,5011.0, 2 , 0 , 0 , 0 ,,
       1       1
   581.9  589.99
       1       1
  581.65  589.74
Abutment Skew #Up #Dn=, 2 , 2
 4977.30 4983.50
  588.51  584.87
 4977.30 4983.50
  588.26  584.62
Abutment Skew #Up #Dn=, 2 , 2
 5016.50 5022.59
  584.57  589.14
 5016.50 5022.59
  584.32  588.89
BR Coef= 1 , 1 , 0 ,1.25, 0 ,,,0.8,0,2,0,
Wspro=,,,, 1 ,,,, 0 ,,,, 0 ,,,,-1 ,-1 ,-1 , 0 , 0 , 0 , 0 , 0
BC Design=,, 0 ,, 0 ,,,,,,
BR U #Sta/Elev= 42
  4656.8  596.33  4726.8  592.68  4756.8  591.12  4777.5  590.04  4786.8  589.37
  4817.5  587.15  4837.5  587.68  4846.8  587.17  4856.8  586.62  4867.5  586.03
  4877.5  586.23  4887.5   585.9  4897.5   586.6  4917.5  588.84  4927.5  588.82
  4977.3  584.94 4977.41  584.94  4977.5  584.94  4983.5  584.87  4987.5  584.82
    4990   583.4    4992   579.9    5008   579.9    5010   583.4  5011.7  582.83
  5016.5  584.57  5021.7  586.46 5022.39  586.56  5022.5  586.57  5031.7  587.86
  5061.7  588.43  5071.7  589.28  5081.7  590.77  5131.2  594.56  5131.7   594.6
  5141.2  594.91  5151.2  595.23  5171.2  595.88  5181.2   596.2  5191.2  596.53
  5271.2  599.12  5318.1  600.64
BR U #Mann= 3
 4656.80    0.12    4990   0.045    5010    0.14
BR U Banks=4990.00,5010.00
BR D #Sta/Elev= 42
  4656.8  596.08  4726.8  592.43  4756.8  590.87  4777.5  589.79  4786.8  589.12
  4817.5   586.9  4837.5  587.43  4846.8  586.92  4856.8  586.37  4867.5  585.78
  4877.5  585.98  4887.5  585.65  4897.5  586.35  4917.5  588.59  4927.5  588.57
  4977.3  584.69 4977.41  584.69  4977.5  584.69  4983.5  584.62  4987.5  584.57
    4990  583.15    4992  579.65    5008  579.65    5010  583.15  5011.7  582.58
  5016.5  584.32  5021.7  586.21 5022.39  586.31  5022.5  586.32  5031.7  587.61
  5061.7  588.18  5071.7  589.03  5081.7  590.52  5131.2  594.31  5131.7  594.35
  5141.2  594.66  5151.2  594.98  5171.2  595.63  5181.2  595.95  5191.2  596.28
  5271.2  598.87  5318.1  600.39
BR D #Mann= 3
 4656.80    0.12    4990   0.045    5010    0.14
BR D Banks=4990.00,5010.00

Type RM Length L Ch R = 1 ,71711.7,392.65,392.65,392.65
XS GIS Cut Line= 3
 1974229.0426341 883851.02202372 1973940.7426632 883662.65266122
 1973645.7108832 883546.81196234
BEGIN DESCRIPTION:
Downstream Section of Bridge/Culvert/Weir
END DESCRIPTION:
#Sta/Elev= 24
  4656.8  596.08  4777.5  589.79  4817.5   586.9  4837.5  587.43  4867.5  585.78
  4877.5  585.98  4887.5  585.65  4897.5  586.35  4917.5  588.59  4927.5  588.57
  4977.3  584.69  4987.5  584.57    4990  583.15    4992  579.65    5008  579.65
    5010  583.15  5011.7  582.58  5021.7  586.21  5031.7  587.61  5061.7  588.18
  5071.7  589.03  5081.7  590.52  5131.7  594.35  5318.1  600.39
#Mann= 3 , 1 , 0
 4656.80    0.12       0    4990   0.045       0    5010    0.14       0
#XS Ineff= 2 , 0
       0  4967.3     588  5032.6       0   590.8
Bank Sta=4990.00,5010.00
Exp/Cntr=0.5,0.3

Type RM Length L Ch R = 1 ,71319.0,463.6,463.6,463.6
XS GIS Cut Line= 3
 1974398.0702120 883790.50755646 1974258.0067155 883547.06386005
 1974084.5947673 883133.54306066
BEGIN DESCRIPTION:
South Fork Little River 143.0
END DESCRIPTION:
#Sta/Elev= 28
    4716  604.94    4736  605.12    4816  600.67    4826   598.8    4846  596.19
    4876  594.95    4886  591.96    4906  588.72    4926  586.48    4956  584.69
    4966  584.54    4986  585.33    4987  581.15  4988.5  578.15  5011.5  578.15
    5013  581.15  5016.9  584.02  5046.9  585.89  5056.9  587.06  5116.9  596.22
  5146.9  599.27  5196.9  603.45  5236.9   604.3  5276.9  607.43  5296.9  606.75
  5316.9  608.56  5346.9  608.91  5445.3  611.92
#Mann= 3 , 1 , 0
 4716.00    0.12       0    4987   0.045       0    5013    0.14       0
Bank Sta=4987.00,5013.00
Exp/Cntr=0.3,0.1

Type RM Length L Ch R = 1 ,70855.4,355.4,355.4,355.4
XS GIS Cut Line= 3
 1974731.5547277 883386.99129254 1974564.8124698 883243.59295082
 1974444.7580442 883106.86429941
BEGIN DESCRIPTION:
South Fork Little River 142.0
END DESCRIPTION:
#Sta/Elev= 20
  4784.3  600.52  4824.3  599.19  4834.3  598.47  4854.3  598.19  4894.3  596.13
  4904.3  594.62  4934.3  592.16  4954.3  589.02  4964.3  586.99  4984.3  584.39
    4987   578.8  4988.5   575.8  5011.5   575.8    5013   578.8  5024.2  583.34
  5034.2  584.55  5064.2  583.77  5094.2  586.69  5184.2  600.85  5186.2  601.03
#Mann= 3 , 1 , 0
 4784.30    0.12       0    4987   0.045       0    5013    0.14       0
Bank Sta=4987.00,5013.00
Exp/Cntr=0.3,0.1

Type RM Length L Ch R = 1 ,70500.0,500,500,500
XS GIS Cut Line= 3
 1974848.2743081 883136.87790581 1974762.8679607  882955.1797576
 1974648.1835987 882813.39792565
BEGIN DESCRIPTION:
South Fork Little River 141.0
END DESCRIPTION:
#Sta/Elev= 18
  4799.2  598.58  4899.2   593.4  4919.2  591.77  4959.2  586.93  4969.2  586.03
  4979.2  584.31  4986.9  577.83  4988.4  574.83  5011.5  574.83    5013  577.83
    5020  583.73    5030  585.38    5070  583.46    5100  584.24    5110  584.91
    5120  586.57    5160  595.98  5182.3  599.17
#Mann= 3 , 1 , 0
 4799.20    0.14       0  4986.9    0.05       0    5013    0.14       0
Bank Sta=4986.90,5013.00
Exp/Cntr=0.3,0.1

Type RM Length L Ch R = 1 ,70000.0,630.9,630.9,630.9
XS GIS Cut Line= 3
 1975288.4738688 882666.66473877 1975064.2301515 882600.19518191
 1974771.5728695 882476.57856485
BEGIN DESCRIPTION:
South Fork Little River 140.0
END DESCRIPTION:
#Sta/Elev= 27
  4766.1  613.67  4896.1  597.34  4906.1  595.44  4916.1  594.09  4946.1  587.95
  4966.1  584.73  4976.1  582.62    4987  576.07  4988.5  573.07  5011.5  573.07
    5013  576.07    5020  582.83    5040  583.75    5070  583.31    5080  583.72
    5100  583.55    5120  584.38    5130  585.21    5140  586.68    5160  588.24
    5200  589.06    5220  588.93    5230  589.59    5270  590.93    5290  592.92
    5300  592.83  5317.7  593.62
#Mann= 3 , 1 , 0
 4766.10    0.14       0    4987    0.05       0    5013    0.14       0
Bank Sta=4987.00,5013.00
Exp/Cntr=0.3,0.1

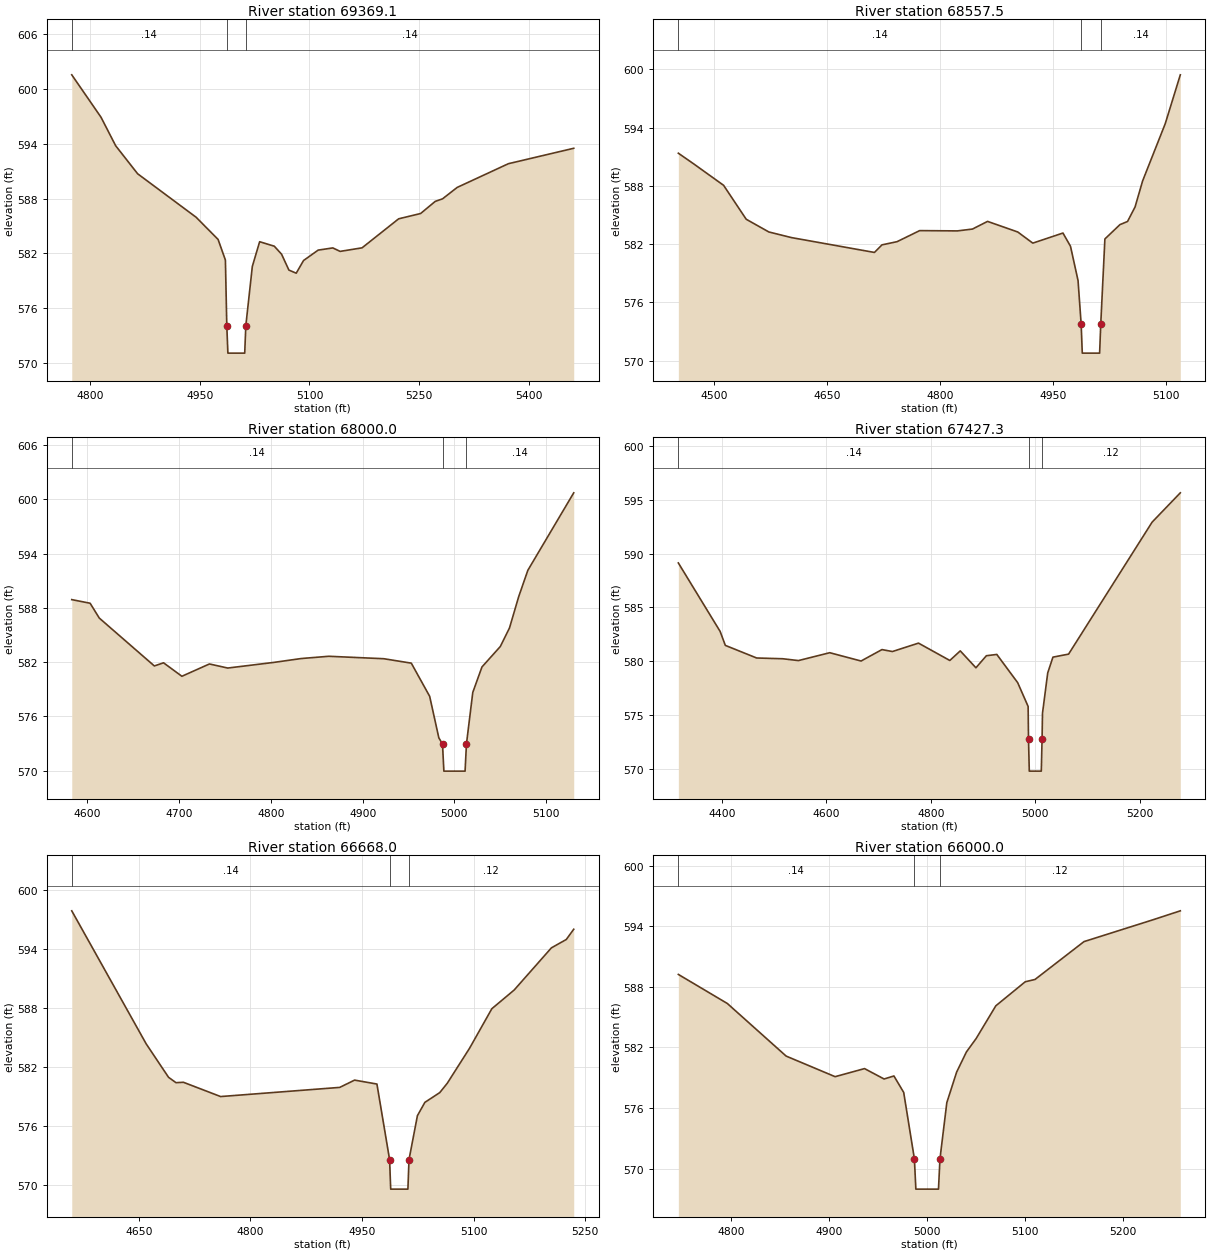
Type RM Length L Ch R = 1 ,69369.1,811.6,811.6,811.6
XS GIS Cut Line= 3
 1975421.0814577 882446.62336141 1975418.5328299 882219.79548781
 1975371.8449977 881762.92170139
BEGIN DESCRIPTION:
South Fork Little River 139.0
END DESCRIPTION:
#Sta/Elev= 29
  4775.1  601.57  4815.1  596.92  4835.1   593.8  4865.1  590.73  4945.1  585.96
  4975.1  583.53  4985.1  581.27    4987  574.07  4988.5  571.07  5011.5  571.07
    5013  574.07  5021.9  580.57  5031.9  583.28  5051.9  582.79  5061.9  581.91
  5071.9  580.17  5081.9  579.83  5091.9  581.22  5111.9  582.36  5131.9   582.6
  5141.9  582.22  5171.9  582.61  5221.9  585.79  5251.9  586.37  5271.9   587.7
  5281.9  587.98  5301.9  589.23  5371.9  591.83  5461.2  593.52
#Mann= 3 , 1 , 0
 4775.10    0.14       0    4987    0.05       0    5013    0.14       0
Bank Sta=4987.00,5013.00
Exp/Cntr=0.3,0.1

Type RM Length L Ch R = 1 ,68557.5,557.5,557.5,557.5
XS GIS Cut Line= 3
 1976148.8639191 882133.08951375 1975872.0717711  881662.8763467
 1975801.2831673 881566.00773094
BEGIN DESCRIPTION:
South Fork Little River 137.0
END DESCRIPTION:
#Sta/Elev= 29
  4452.9  591.37  4472.9  590.29  4512.9  588.06  4542.9  584.56  4572.9  583.25
  4602.9  582.67  4712.9  581.14  4722.9  581.92  4742.9  582.25  4772.9  583.39
  4822.9  583.36  4842.9  583.55  4862.9  584.34  4902.9  583.25  4922.9   582.1
  4962.9  583.14  4972.9  581.77  4982.9  578.24    4987  573.76  4988.5  570.76
  5011.5  570.76    5013  573.76  5018.5  582.53  5038.5  584.01  5048.5  584.33
  5058.5  585.83  5068.5  588.51  5098.5  594.41  5118.5  599.45
#Mann= 3 , 1 , 0
 4452.90    0.14       0    4987    0.05       0    5013    0.14       0
Bank Sta=4987.00,5013.00
Exp/Cntr=0.3,0.1

Type RM Length L Ch R = 1 ,68000.0,572.7,572.7,572.7
XS GIS Cut Line= 3
 1976475.6787444 881629.52789514 1976206.0236259 881311.40788761
 1976124.7402731 881209.94842458
BEGIN DESCRIPTION:
South Fork Little River 136.0
END DESCRIPTION:
#Sta/Elev= 26
    4583  588.91    4603  588.51    4613  586.87    4673  581.58    4683  581.93
    4703  580.44    4733   581.8    4753  581.35    4803  581.97    4833   582.4
    4863  582.65    4923  582.38    4953  581.89    4973  578.23    4983  573.64
    4987  572.96  4988.5  569.96  5011.6  569.96  5013.1  572.96    5020  578.66
    5030  581.47    5050  583.73    5060  585.78    5070  589.23    5080  592.15
    5130  600.71
#Mann= 3 , 1 , 0
 4583.00    0.14       0    4987    0.05       0  5013.1    0.14       0
Bank Sta=4987.00,5013.10
Exp/Cntr=0.3,0.1

Type RM Length L Ch R = 1 ,67427.3,759.3,759.3,759.3
XS GIS Cut Line= 3
 1976478.5445526 881603.08412857 1976575.7240991 880932.54525745
 1976592.3983249 880649.08341916
BEGIN DESCRIPTION:
South Fork Little River 135.0
END DESCRIPTION:
#Sta/Elev= 28
  4316.3  589.13  4396.3  582.78  4406.3  581.48  4466.3  580.31  4516.3  580.24
  4546.3  580.07  4606.3   580.8  4666.3  580.03  4706.3  581.09  4726.3  580.91
  4776.3  581.69  4836.3  580.08  4856.3  580.97  4886.3   579.4  4906.3  580.52
  4926.3  580.64  4966.3  578.02  4986.3  575.81    4987  572.81  4988.5  569.81
  5011.5  569.81    5013  572.81  5013.8  575.18  5023.8  578.92  5033.8  580.39
  5063.8  580.67  5223.8  592.92  5277.8  595.64
#Mann= 3 , 1 , 0
 4316.30    0.14       0    4987    0.05       0    5013    0.12       0
Bank Sta=4987.00,5013.00
Exp/Cntr=0.3,0.1

Type RM Length L Ch R = 1 ,66668.0,668,668,668
XS GIS Cut Line= 3
 1977312.7248787  881479.4598631 1977252.6976659 881049.26483793
 1977183.2210901 880819.45770256
BEGIN DESCRIPTION:
South Fork Little River 133.0
END DESCRIPTION:
#Sta/Elev= 23
    4560  597.86    4660  584.35    4690  580.96    4700  580.41    4710  580.45
    4760     579    4920  579.93    4940  580.67    4970  580.27    4987   572.6
  4988.5   569.6  5011.6   569.6  5013.1   572.6  5024.4  577.06  5034.4  578.41
  5054.4   579.4  5064.4  580.34  5094.4   583.9  5124.4  587.92  5154.4  589.82
  5204.4   594.1  5224.4  594.95  5234.4  595.99
#Mann= 3 , 1 , 0
 4560.00    0.14       0    4987    0.05       0  5013.1    0.12       0
Bank Sta=4987.00,5013.10
Exp/Cntr=0.3,0.1

Type RM Length L Ch R = 1 ,66000.0,606.7,606.7,606.7
XS GIS Cut Line= 3
 1977906.3273165 881075.94359918 1977833.3592979 880832.68368742
 1977769.5986651 880582.38651604
BEGIN DESCRIPTION:
South Fork Little River 132.0
END DESCRIPTION:
#Sta/Elev= 22
    4746  589.23    4796  586.35    4856  581.14    4906   579.1    4936   579.9
    4956  578.87    4966  579.17    4976  577.54  4986.9  570.96  4988.4  567.96
  5011.5  567.96    5013  570.96    5020  576.53    5030  579.55    5040  581.55
    5050  582.89    5070  586.12    5100   588.5    5110  588.73    5160  592.48
    5230  594.63  5258.3  595.53
#Mann= 3 , 1 , 0
 4746.00    0.14       0  4986.9    0.05       0    5013    0.12       0
Bank Sta=4986.90,5013.00
Exp/Cntr=0.3,0.1

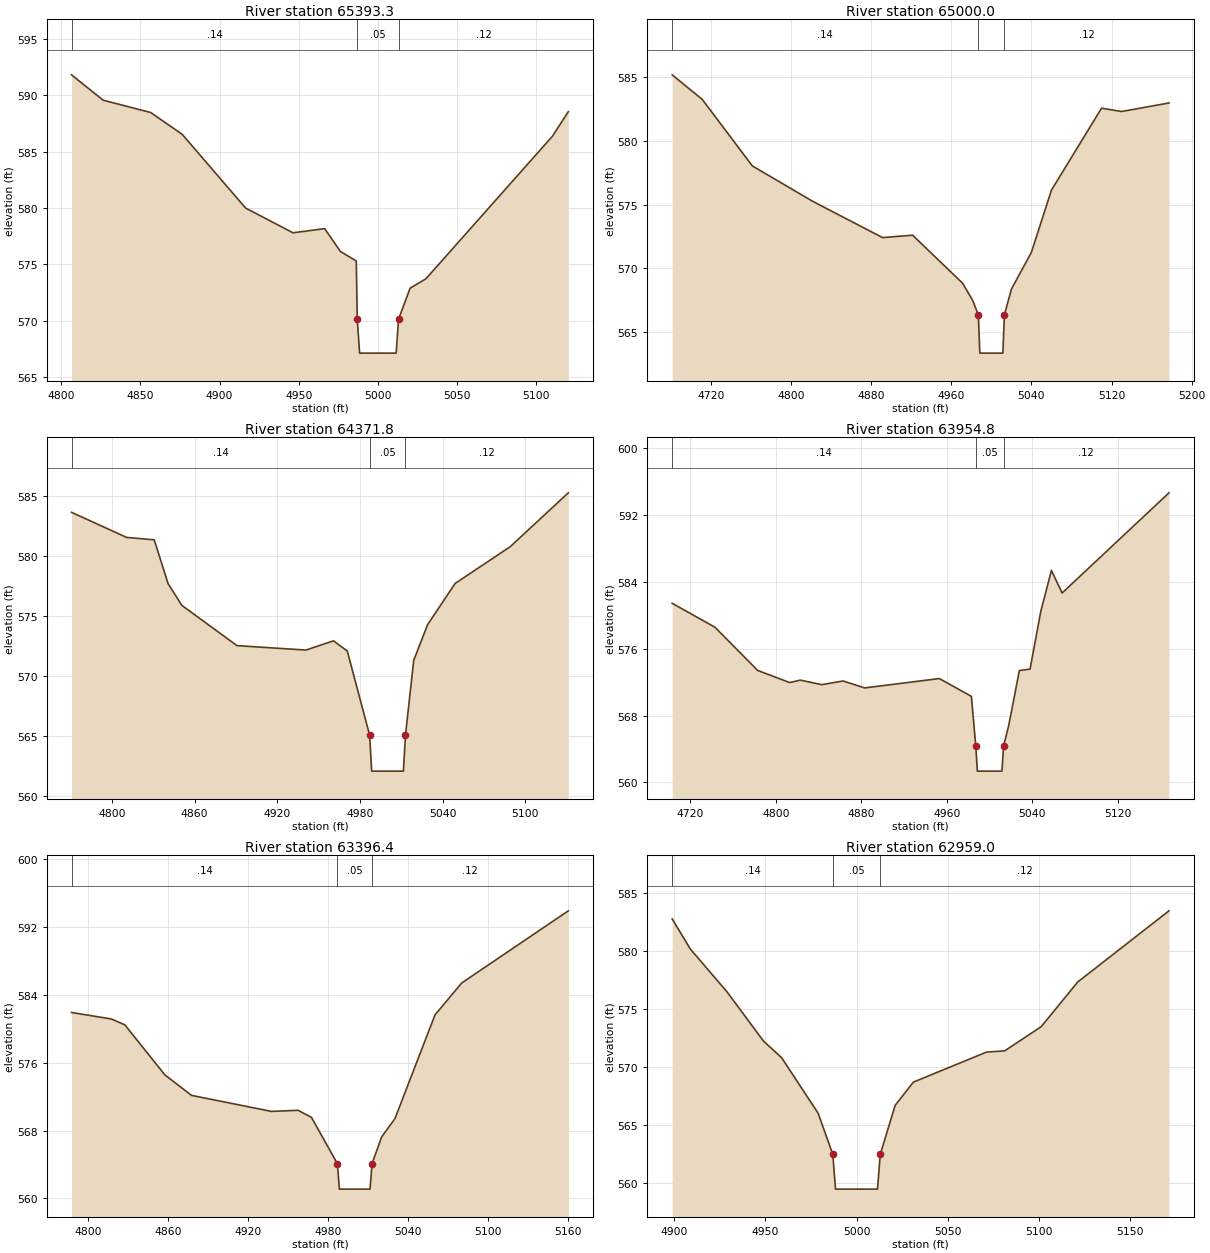
Type RM Length L Ch R = 1 ,65393.3,393.3,393.3,393.3
XS GIS Cut Line= 3
 1978511.5998411 880862.20344689 1978406.5540900 880699.10609651
 1978332.1957461 880604.91886093
BEGIN DESCRIPTION:
South Fork Little River 131.0
END DESCRIPTION:
#Sta/Elev= 17
  4806.4   591.8  4826.4  589.55  4856.4  588.46  4876.4  586.52  4916.4  579.99
  4946.4  577.79  4966.4  578.16  4976.4  576.13  4986.4  575.29    4987  570.12
  4988.5  567.12  5011.6  567.12  5013.1  570.12  5020.4  572.88  5030.4  573.71
  5110.4  586.36  5120.4  588.53
#Mann= 3 , 1 , 0
 4806.40    0.14       0    4987    0.05       0  5013.1    0.12       0
Bank Sta=4987.00,5013.10
Exp/Cntr=0.3,0.1

Type RM Length L Ch R = 1 ,65000.0,628.2,628.2,628.2
XS GIS Cut Line= 3
 1978911.8942909 880699.52997668 1978706.1315751 880456.25595485
 1978549.9524317 880372.29127118
BEGIN DESCRIPTION:
South Fork Little River 130.0
END DESCRIPTION:
#Sta/Elev= 18
  4681.4   585.2  4711.4  583.27  4761.4  578.05  4821.4  575.28  4891.4  572.42
  4921.4  572.61  4971.4  568.83  4981.4  567.48    4987  566.35  4988.5  563.35
  5011.5  563.35    5013  566.35    5020  568.37    5040  571.27    5060  576.15
    5110  582.58    5130  582.32  5177.3  582.99
#Mann= 3 , 1 , 0
 4681.40    0.14       0    4987    0.05       0    5013    0.12       0
Bank Sta=4987.00,5013.00
Exp/Cntr=0.3,0.1

Type RM Length L Ch R = 1 ,64371.8,417,417,417
XS GIS Cut Line= 3
 1978557.6637526 879974.31475299 1978507.4013114 880196.90556422
         1978475          880325
BEGIN DESCRIPTION:
South Fork Little River 129.0
END DESCRIPTION:
#Sta/Elev= 18
  4770.8  583.62  4810.8  581.53  4830.8  581.33  4840.8   577.7  4850.8  575.88
  4890.8  572.53  4940.8  572.16  4960.8  572.93  4970.8  572.08    4987  565.09
  4988.5  562.09  5011.5  562.09    5013  565.09    5019  571.31    5029  574.26
    5049   577.7    5089  580.76  5131.1  585.24
#Mann= 3 , 1 , 0
 4770.80    0.14       0    4987    0.05       0    5013    0.12       0
Bank Sta=4987.00,5013.00
Exp/Cntr=0.3,0.1

Type RM Length L Ch R = 1 ,63954.8,558.4,558.4,558.4
XS GIS Cut Line= 3
 1978445.1716222 879916.87196299 1978157.9576722 879983.88855132
 1977992.8096510 880026.97064381
BEGIN DESCRIPTION:
South Fork Little River 128.0
END DESCRIPTION:
#Sta/Elev= 21
  4702.9  581.42  4742.9  578.56  4782.9  573.39  4812.9  571.94  4822.9  572.23
  4842.9  571.69  4862.9  572.13  4882.9   571.3  4952.9  572.42  4982.9  570.29
    4987  564.35  4988.5  561.35  5011.5  561.35    5013  564.35  5017.8  566.79
  5027.8  573.38  5037.8  573.55  5047.8  580.43  5057.8  585.35  5067.8  582.65
  5167.8  594.63
#Mann= 3 , 1 , 0
 4702.90    0.14       0    4987    0.05       0    5013    0.12       0
Bank Sta=4987.00,5013.00
Exp/Cntr=0.3,0.1

Type RM Length L Ch R = 1 ,63396.4,437.4,437.4,437.4
XS GIS Cut Line= 3
 1978463.2464576 879902.07810414 1978459.5323197 879689.49425259
 1978458.1650432 879529.52290351
BEGIN DESCRIPTION:
South Fork Little River 127.0
END DESCRIPTION:
#Sta/Elev= 17
  4787.6  581.92  4817.6  581.15  4827.6  580.46  4857.6  574.57  4877.6  572.15
  4937.6  570.26  4957.6  570.39  4967.6  569.55    4987   564.1  4988.5   561.1
  5011.5   561.1    5013   564.1  5020.2  567.25  5030.2  569.41  5060.2  581.63
  5080.2  585.39  5160.2   593.9
#Mann= 3 , 1 , 0
 4787.60    0.14       0    4987    0.05       0    5013    0.12       0
Bank Sta=4987.00,5013.00
Exp/Cntr=0.3,0.1

Type RM Length L Ch R = 1 ,62959.0,512.2,512.2,512.2
XS GIS Cut Line= 3
 1978914.8973581 879742.45530866 1978856.8449505 879658.37940801
 1978757.5730678 879520.33927788
BEGIN DESCRIPTION:
South Fork Little River 126.0
END DESCRIPTION:
#Sta/Elev= 17
    4899  582.79    4909  580.18    4929   576.5    4949  572.24    4959  570.79
    4979  565.99    4987  562.44  4988.5  559.44  5011.5  559.44    5013  562.44
  5021.2  566.69  5031.2  568.69  5071.2  571.28  5081.2  571.39  5101.2  573.48
  5121.2  577.34  5171.2  583.49
#Mann= 3 , 1 , 0
 4899.00    0.14       0    4987    0.05       0    5013    0.12       0
Bank Sta=4987.00,5013.00
Exp/Cntr=0.3,0.1

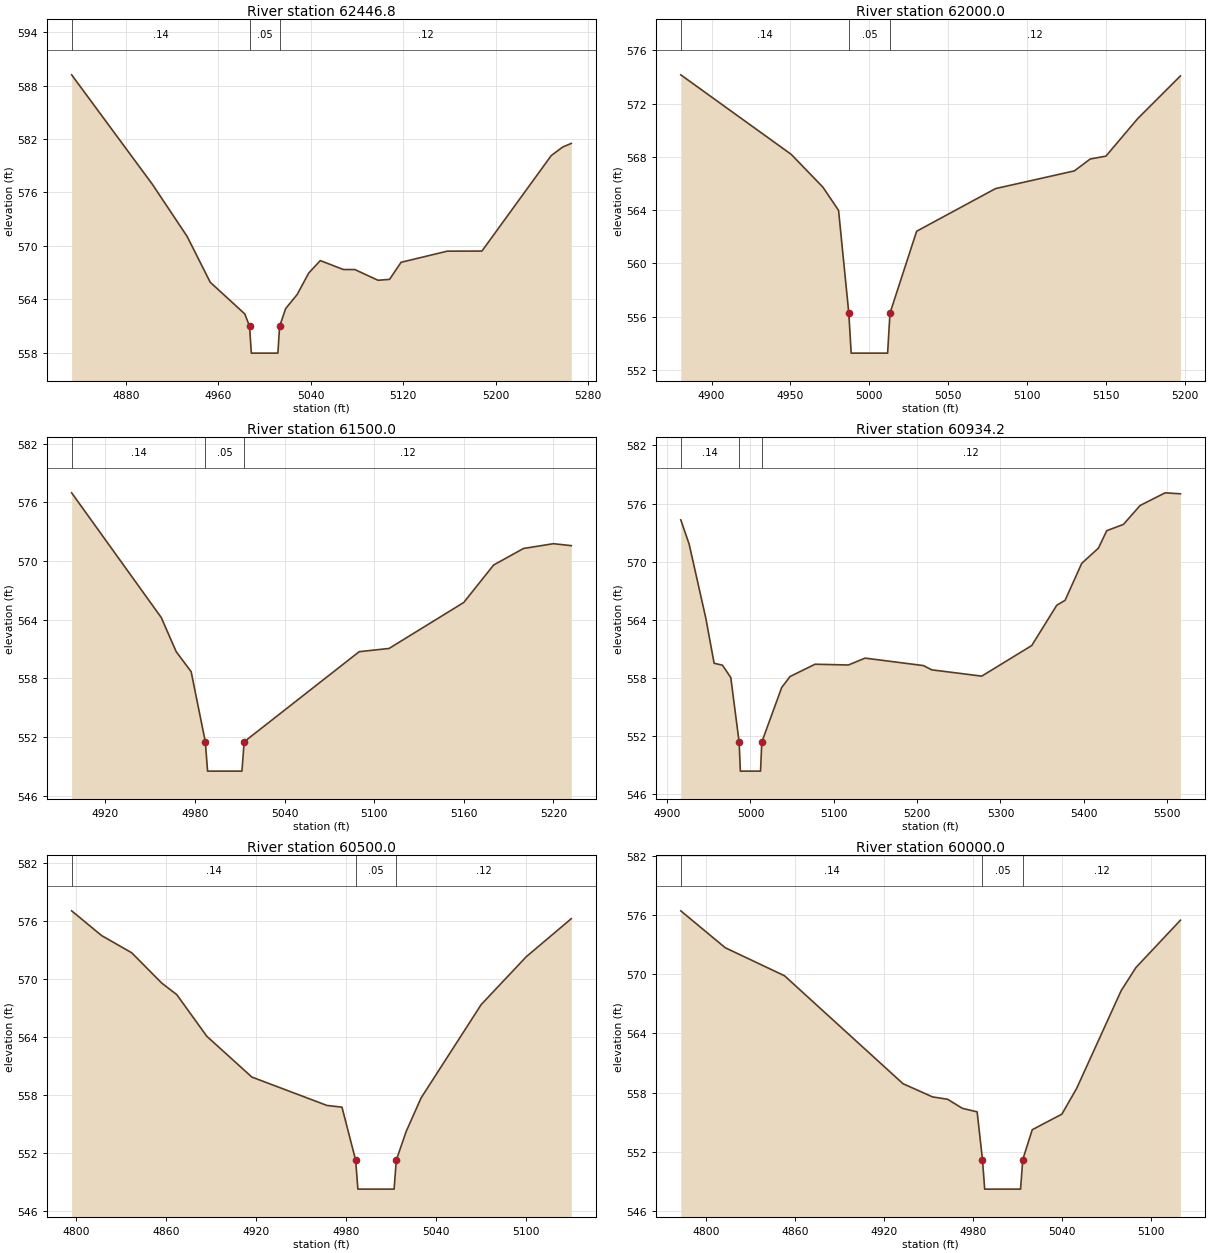
Type RM Length L Ch R = 1 ,62446.8,446.8,446.8,446.8
XS GIS Cut Line= 3
 1979309.2069217 879378.34580678 1979172.7802955 879285.00127304
 1978986.0912280 879093.52530638
BEGIN DESCRIPTION:
South Fork Little River 125.0
END DESCRIPTION:
#Sta/Elev= 23
  4832.9  589.22  4902.9   576.9  4932.9  571.06  4952.9  565.91  4982.9  562.34
    4987  560.94  4988.5  557.94  5011.5  557.94    5013  560.94  5018.2  562.94
  5028.2  564.53  5038.2  566.94  5048.2  568.34  5068.2  567.34  5078.2  567.33
  5098.2  566.13  5108.2  566.23  5118.2  568.15  5158.2   569.4  5188.2  569.41
  5248.2  580.14  5258.2  581.11  5265.6  581.51
#Mann= 3 , 1 , 0
 4832.90    0.14       0    4987    0.05       0    5013    0.12       0
Bank Sta=4987.00,5013.00
Exp/Cntr=0.3,0.1

Type RM Length L Ch R = 1 ,62000.0,500,500,500
XS GIS Cut Line= 3
 1979455.2073463 879009.75457097 1979372.9918072  878922.9650612
 1979254.1575813 878765.62271349
BEGIN DESCRIPTION:
South Fork Little River 124.0
END DESCRIPTION:
#Sta/Elev= 15
  4880.5  574.16  4950.5  568.19  4970.5  565.74  4980.5  563.99    4987  556.27
  4988.5  553.27  5011.6  553.27  5013.1  556.27    5030  562.42    5080  565.62
    5130  566.95    5140  567.84    5150  568.06    5170  570.86  5197.2  574.08
#Mann= 3 , 1 , 0
 4880.50    0.14       0    4987    0.05       0  5013.1    0.12       0
Bank Sta=4987.00,5013.10
Exp/Cntr=0.3,0.1

Type RM Length L Ch R = 1 ,61500.0,565.8,565.8,565.8
XS GIS Cut Line= 3
 1979795.0771871 878787.16375974 1979755.9765525 878692.41624474
         1979675          878475
BEGIN DESCRIPTION:
South Fork Little River 123.0
END DESCRIPTION:
#Sta/Elev= 15
  4897.5  576.96  4957.5  564.21  4967.5  560.72  4977.5  558.68    4987  551.51
  4988.5  548.51  5011.5  548.51    5013  551.51    5090  560.72    5110  561.05
    5160  565.75    5180  569.58    5200  571.27    5220  571.76    5232  571.56
#Mann= 3 , 1 , 0
 4897.50    0.14       0    4987    0.05       0    5013    0.12       0
Bank Sta=4987.00,5013.00
Exp/Cntr=0.3,0.1

Type RM Length L Ch R = 1 ,60934.2,434.2,434.2,434.2
XS GIS Cut Line= 3
 1980154.6740230   878276.073713 1980073.9766682 878268.00397752
 1979557.0756689 878227.98583564
BEGIN DESCRIPTION:
South Fork Little River 122.0
END DESCRIPTION:
#Sta/Elev= 28
  4916.4  574.32  4926.4  571.82  4946.4  564.18  4956.4  559.51  4966.4  559.31
  4976.4  558.03  4986.4  551.37  4987.9  548.37  5012.1  548.37  5013.6  551.37
  5037.5  557.01  5047.5  558.14  5077.5  559.41  5117.5  559.33  5137.5  560.04
  5207.5  559.27  5217.5  558.83  5277.5  558.18  5337.5  561.34  5367.5   565.5
  5377.5  566.01  5397.5  569.83  5417.5   571.4  5427.5   573.2  5447.5  573.85
  5467.5   575.8  5497.5  577.11  5515.9  577.01
#Mann= 3 , 1 , 0
 4916.40    0.14       0  4986.4    0.05       0  5013.6    0.12       0
Bank Sta=4986.40,5013.60
Exp/Cntr=0.3,0.1

Type RM Length L Ch R = 1 ,60500.0,500,500,500
XS GIS Cut Line= 3
 1979888.6324195 878000.93931722 1979707.5995124 878092.11056861
 1979585.9215573 878137.89127509
BEGIN DESCRIPTION:
South Fork Little River 121.0
END DESCRIPTION:
#Sta/Elev= 18
  4797.3  577.03  4817.3  574.47  4837.3   572.7  4857.3  569.57  4867.3  568.38
  4887.3  564.08  4917.3  559.87  4967.3  556.94  4977.3  556.76  4986.4   551.3
  4987.9   548.3    5012   548.3  5013.5   551.3    5020  554.23    5030  557.72
    5070  567.35    5100  572.29    5130  576.22
#Mann= 3 , 1 , 0
 4797.30    0.14       0  4986.4    0.05       0  5013.5    0.12       0
Bank Sta=4986.40,5013.50
Exp/Cntr=0.3,0.1

Type RM Length L Ch R = 1 ,60000.0,500,500,500
XS GIS Cut Line= 3
 1979830.3550277 877786.35978687 1979692.4866255 877618.52535793
 1979627.6721782 877517.53551554
BEGIN DESCRIPTION:
South Fork Little River 120.0
END DESCRIPTION:
#Sta/Elev= 18
  4782.8  576.42  4812.8  572.68  4852.8  569.84  4932.8   558.9  4952.8  557.56
  4962.8  557.33  4972.8  556.41  4982.8  556.05  4986.4  551.22  4987.9  548.22
  5012.1  548.22  5013.6  551.22    5020  554.24    5040  555.82    5050  558.44
    5080  568.33    5090  570.68    5120  575.47
#Mann= 3 , 1 , 0
 4782.80    0.14       0  4986.4    0.05       0  5013.6    0.12       0
Bank Sta=4986.40,5013.60
Exp/Cntr=0.3,0.1

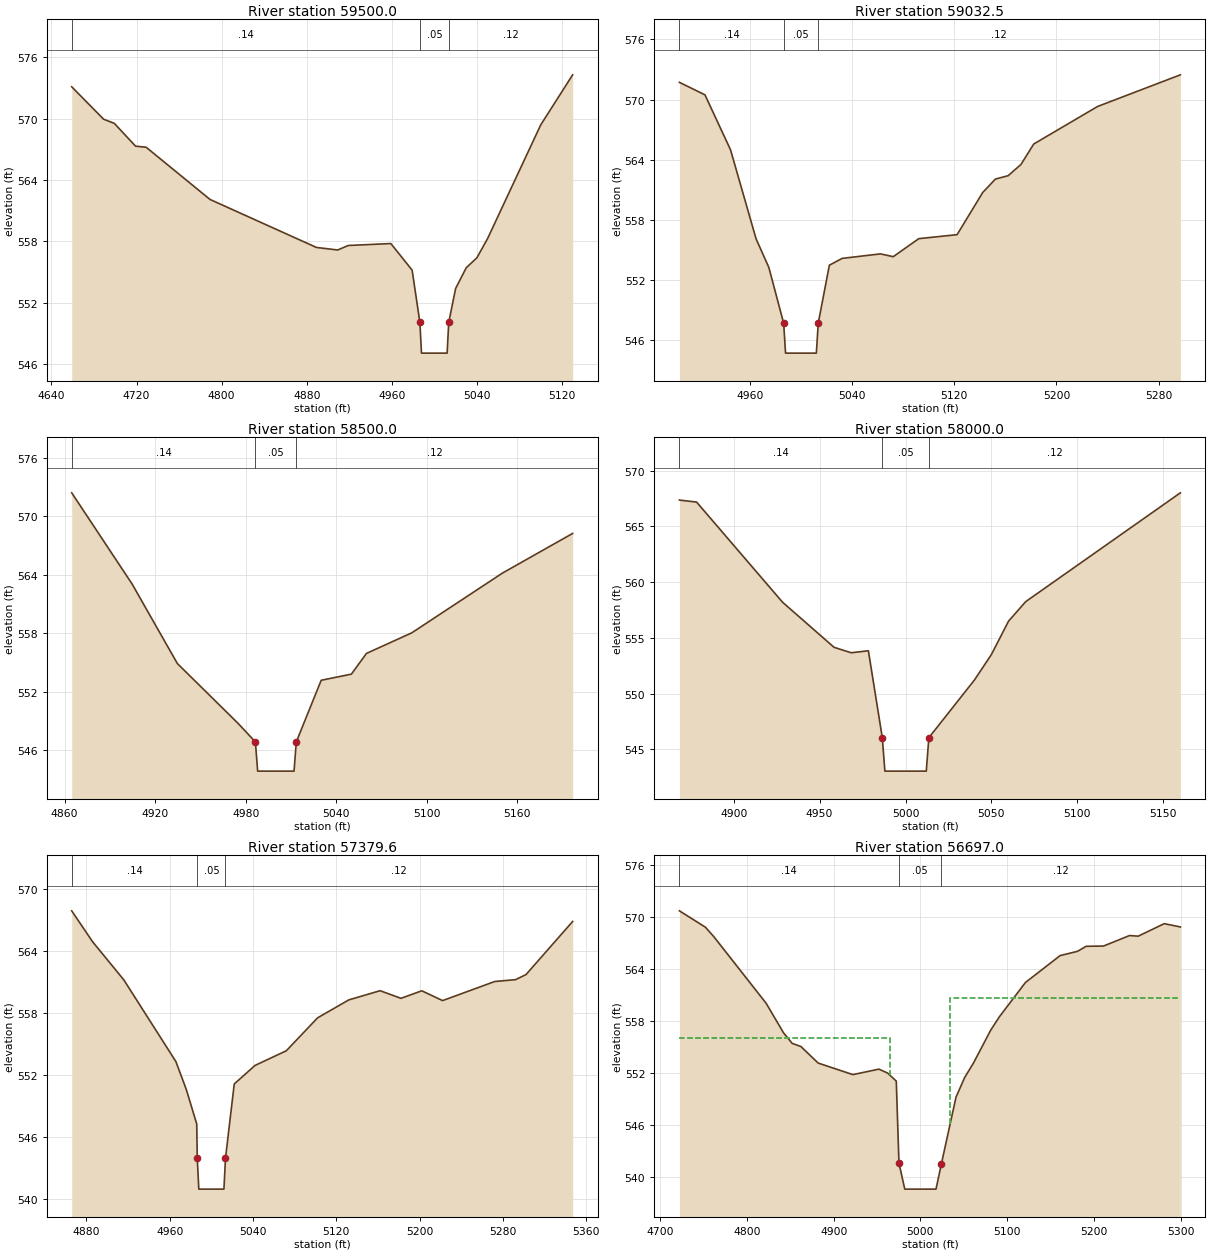
Type RM Length L Ch R = 1 ,59500.0,467.5,467.5,467.5
XS GIS Cut Line= 3
 1979880.5556491 877721.08937187 1980033.1441841 877416.28737796
 1980097.2408040 877303.19003406
BEGIN DESCRIPTION:
South Fork Little River 119.0
END DESCRIPTION:
#Sta/Elev= 21
  4659.1  573.11  4689.1  569.94  4699.1  569.54  4719.1  567.31  4729.1   567.2
  4789.1   562.1  4889.1  557.41  4909.1  557.16  4919.1   557.6  4959.1  557.79
  4979.1  555.19  4986.4  550.08  4987.9  547.08    5012  547.08  5013.5  550.08
    5020   553.4    5030  555.43    5040   556.4    5050  558.27    5100  569.39
    5130  574.28
#Mann= 3 , 1 , 0
 4659.10    0.14       0  4986.4    0.05       0  5013.5    0.12       0
Bank Sta=4986.40,5013.50
Exp/Cntr=0.3,0.1

Type RM Length L Ch R = 1 ,59032.5,532.5,532.5,532.5
XS GIS Cut Line= 3
 1979980.4961873 877867.41461846 1980055.9631917 877805.84943064
 1980273.7671038 877607.19311524
BEGIN DESCRIPTION:
South Fork Little River 118.0
END DESCRIPTION:
#Sta/Elev= 22
  4904.8  571.72  4924.8  570.47  4944.8  564.99  4964.8   556.1  4974.8  553.24
  4986.4  547.68  4987.9  544.68    5012  544.68  5013.5  547.68  5022.2  553.46
  5032.2  554.14  5062.2  554.59  5072.2  554.31  5092.2  556.11  5122.2  556.51
  5142.2  560.71  5152.2  562.06  5162.2   562.4  5172.2  563.52  5182.2  565.56
  5232.2  569.31    5297  572.47
#Mann= 3 , 1 , 0
 4904.80    0.14       0  4986.4    0.05       0  5013.5    0.12       0
Bank Sta=4986.40,5013.50
Exp/Cntr=0.3,0.1

Type RM Length L Ch R = 1 ,58500.0,500,500,500
XS GIS Cut Line= 3
 1980576.4326406   877932.704983 1980502.7550951 877819.22916302
 1980398.2264821 877652.66865732
BEGIN DESCRIPTION:
South Fork Little River 117.0
END DESCRIPTION:
#Sta/Elev= 14
  4864.7  572.42  4904.7  563.06  4934.7  554.89  4974.7  548.78  4986.4  546.84
  4987.9  543.84    5012  543.84  5013.5  546.84    5030  553.17    5050   553.8
    5060  555.93    5090  558.04    5150  564.17  5196.6  568.25
#Mann= 3 , 1 , 0
 4864.70    0.14       0  4986.4    0.05       0  5013.5    0.12       0
Bank Sta=4986.40,5013.50
Exp/Cntr=0.3,0.1

Type RM Length L Ch R = 1 ,58000.0,620.4,620.4,620.4
XS GIS Cut Line= 3
 1980921.6200869 877540.08621814 1980830.1857274 877445.43384534
 1980718.8217106 877330.55504255
BEGIN DESCRIPTION:
South Fork Little River 116.0
END DESCRIPTION:
#Sta/Elev= 15
  4868.4  567.37  4878.4  567.19  4928.4  558.21  4958.4  554.16  4968.4  553.67
  4978.4  553.85  4986.5  546.05    4988  543.05  5012.1  543.05  5013.6  546.05
    5040   551.2    5050  553.51    5060  556.51    5070  558.26    5160  568.02
#Mann= 3 , 1 , 0
 4868.40    0.14       0  4986.5    0.05       0  5013.6    0.12       0
Bank Sta=4986.50,5013.60
Exp/Cntr=0.3,0.1

Type RM Length L Ch R = 1 ,57379.6,682.65,682.65,682.65
XS GIS Cut Line= 3
  1981362.874329 877192.13119675 1981290.1890882 877077.24162265
 1981005.9352612 876882.08227875
BEGIN DESCRIPTION:
South Fork Little River 115.0
END DESCRIPTION:
#Sta/Elev= 23
    4866  567.92    4886  564.93    4916  561.23    4966  553.31    4976   550.6
    4986  547.26  4986.5  543.95    4988  540.95  5012.1  540.95  5013.6  543.95
    5022  551.14    5042  552.94    5072  554.36    5102  557.55    5132  559.29
    5162  560.18    5182  559.44    5202  560.17    5222  559.22    5272  561.07
    5292  561.25    5302  561.74  5346.8  566.89
#Mann= 3 , 1 , 0
 4866.00    0.14       0  4986.5    0.05       0  5013.6    0.12       0
Bank Sta=4986.50,5013.60
Exp/Cntr=0.5,0.3

Type RM Length L Ch R = 1 ,56697.0,36.5,36.5,36.5
XS GIS Cut Line= 3
 1981741.8120900 877061.30694847 1981830.8630487 876793.71046855
 1981935.2549473 876517.64495229
BEGIN DESCRIPTION:
Upstream Section of Bridge/Culvert/Weir
END DESCRIPTION:
#Sta/Elev= 30
  4722.2  570.72  4752.2  568.83  4762.2   567.7  4822.2  560.06  4842.2  556.66
  4852.2  555.44  4862.2  555.08  4882.2  553.17  4922.2  551.84  4952.2  552.47
  4962.2  552.02  4972.2  551.09  4975.3  541.64    4982  538.64    5018  538.64
  5024.2  541.55  5041.1  549.25  5051.1  551.52  5061.1  553.16  5081.1  556.97
  5091.1  558.51  5121.1  562.46  5161.1  565.56  5181.1  566.05  5191.1  566.63
  5211.1  566.66  5241.1  567.87  5251.1   567.8  5281.1  569.24  5299.7  568.86
#Mann= 3 , 1 , 0
 4722.20    0.14       0  4975.3    0.05       0  5024.2    0.12       0
#XS Ineff= 2 , 0
       0  4965.3  556.06  5034.2       0  560.72
Bank Sta=4975.30,5024.20
Exp/Cntr=0.5,0.3