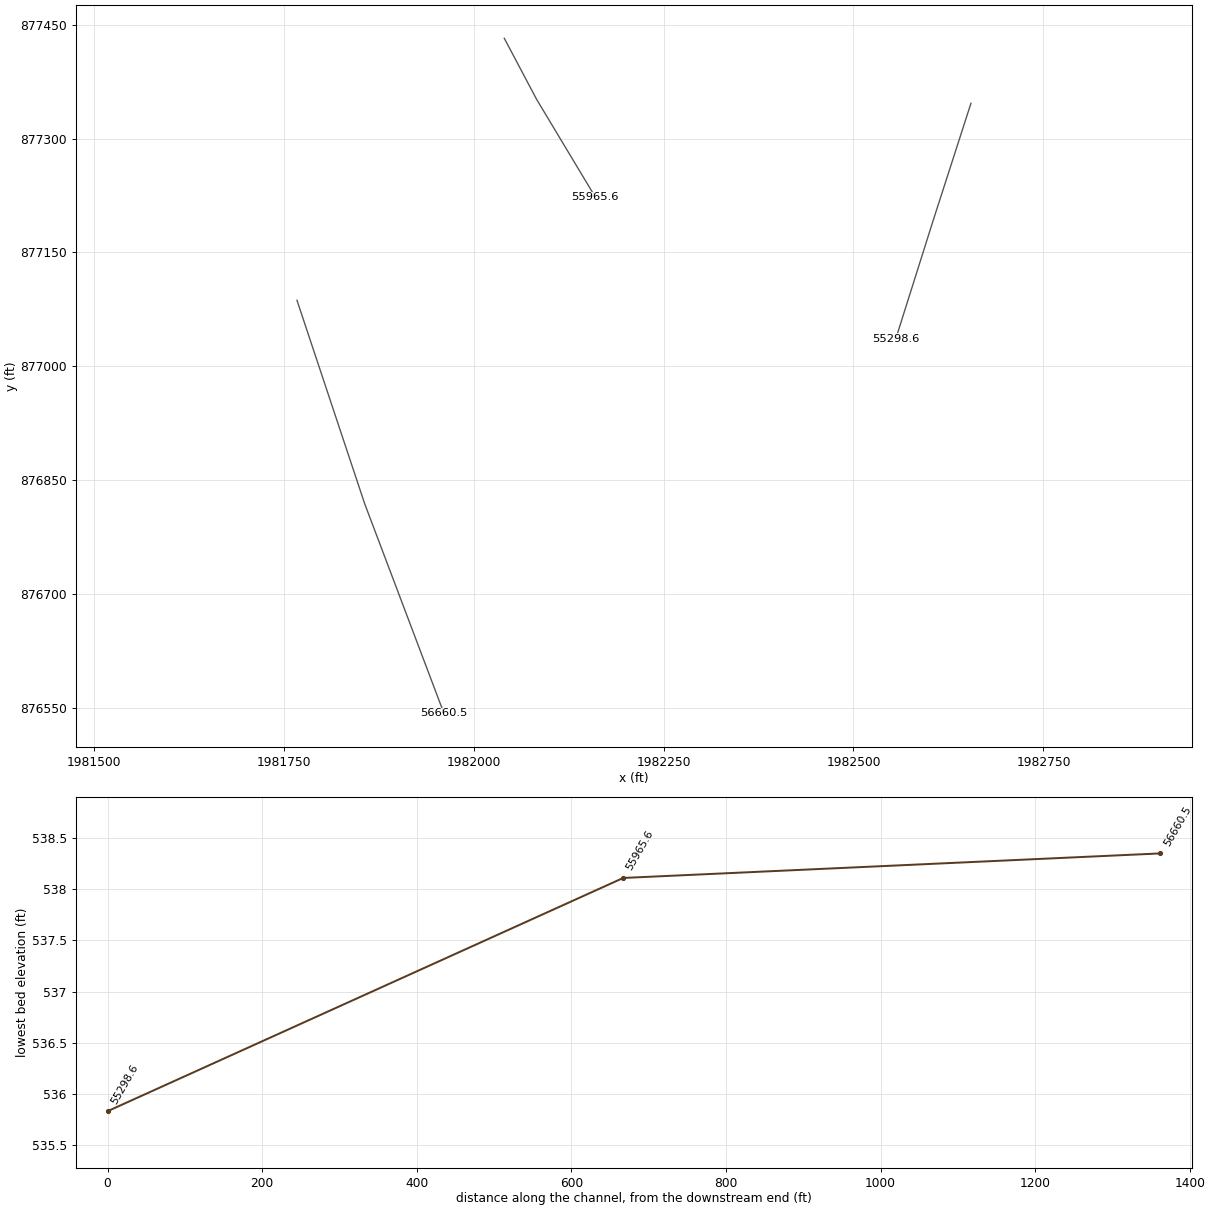
HEC-RAS study S_Fork_Little_River_FINAL.prj: South Fork Little River

--- S_Fork_Little_River_FINAL.g01 (geometry) --- (continued)

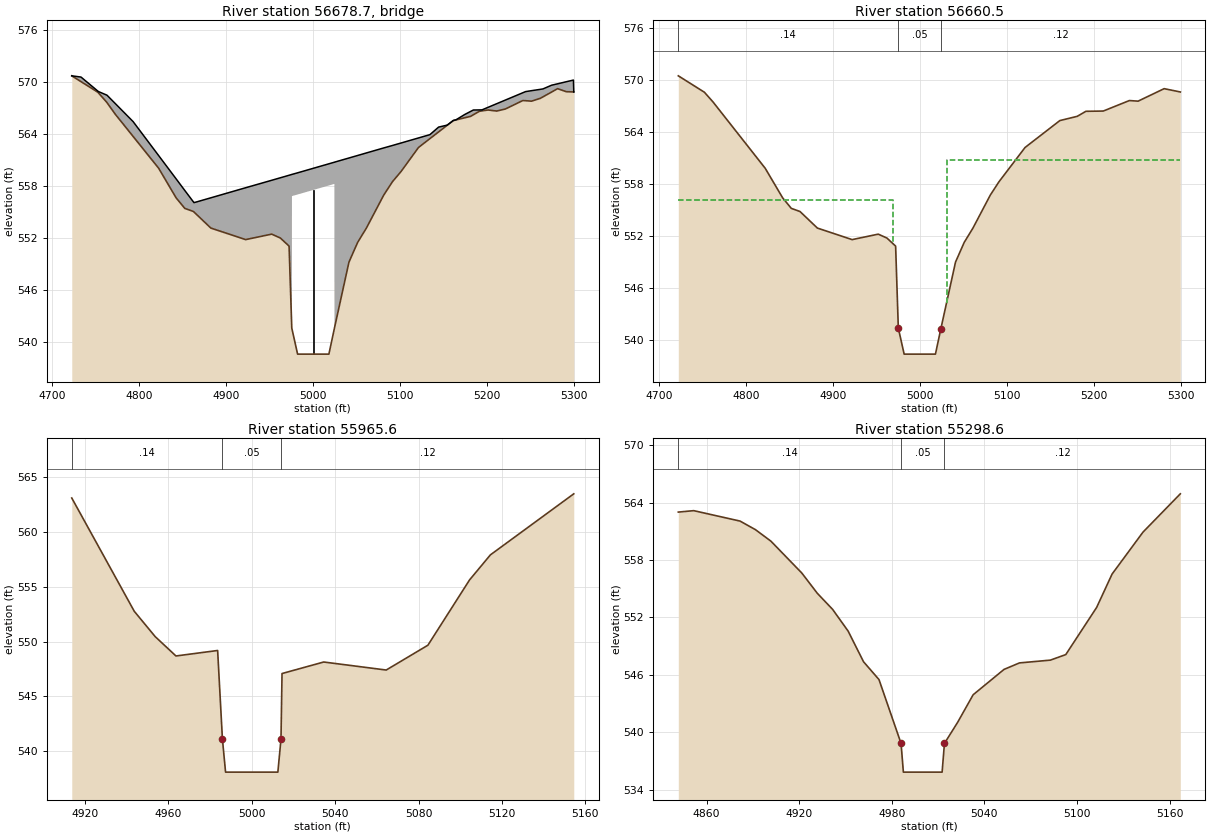
Type RM Length L Ch R = 3 ,56678.7,,,
BEGIN DESCRIPTION:
Brock Drive-TOR
Structure ID: Brock Drive (SFLR)-Bridge
Approximate Survey Structure
END DESCRIPTION:
Bridge Culvert--1,0,-1,-1, 0
Deck Dist Width WeirC Skew NumUp NumDn MinLoCord MaxHiCord MaxSubmerge Is_Ogee
10,16.5,2.6,,58,58,,,0.95,0,1,1,,
  4722.2  4732.8  4752.2  4752.8  4762.2  4762.8  4772.2  4792.8  4822.2  4842.2
  4852.2  4862.2  4862.8  4882.2  4922.2  4952.2  4962.2  4972.2  4975.3 4975.41
  4975.5  4975.6    4982    5018  5024.2 5024.29  5024.4  5024.5  5041.1  5051.1
  5061.1  5081.1  5091.1  5101.1  5121.1  5134.2  5144.2  5154.2  5161.1  5164.2
  5174.2  5181.1  5184.2  5191.1  5194.2  5201.1  5211.1  5221.1  5241.1  5244.2
  5251.1  5261.1  5264.2  5274.2  5281.1  5291.1  5299.3  5299.7
  570.68  570.54  568.92  568.87  568.47  568.44  567.49   565.4  561.48  558.81
  557.47  556.14  556.06  556.62  557.78  558.64  558.93  559.22  559.31  559.31
  559.32  559.32   559.5  560.54  560.72  560.73  560.73  560.73  561.21   561.5
  561.79  562.37  562.65  562.94  563.52   563.9  564.77     565  565.53  565.61
  566.22  566.58  566.74  566.75  566.76  567.05  567.47  567.89  568.73  568.86
  568.97  569.12  569.17   569.6  569.76     570  570.19  568.82
  570.68  570.01  568.79  568.72  567.66  567.58  566.26  563.69  560.02  556.62
   555.4  555.04  554.98  553.13   551.8  552.43  551.98  551.05   541.6  541.55
  556.82  556.82     557  558.04  558.22  558.23   541.6  541.65  549.21  551.48
  553.12  556.93  558.47  559.66  562.42  563.44  564.21  564.99  565.52   565.6
  565.84  566.01  566.19  566.59  566.64  566.74  566.62  566.86  567.83  567.81
  567.76  568.08  568.25  568.81   569.2  568.85  568.82  568.82
  4722.2  4732.8  4752.2  4752.8  4762.2  4762.8  4772.2  4792.8  4822.2  4842.2
  4852.2  4862.2  4862.8  4882.2  4922.2  4952.2  4962.2  4972.2  4975.3 4975.41
  4975.5  4975.6    4982    5018  5024.2 5024.29  5024.4  5024.5  5041.1  5051.1
  5061.1  5081.1  5091.1  5101.1  5121.1  5134.2  5144.2  5154.2  5161.1  5164.2
  5174.2  5181.1  5184.2  5191.1  5194.2  5201.1  5211.1  5221.1  5241.1  5244.2
  5251.1  5261.1  5264.2  5274.2  5281.1  5291.1  5299.3  5299.7
  570.68  570.54  568.92  568.87  568.47  568.44  567.49   565.4  561.48  558.81
  557.47  556.14  556.06  556.62  557.78  558.64  558.93  559.22  559.31  559.31
  559.32  559.32   559.5  560.54  560.72  560.73  560.73  560.73  561.21   561.5
  561.79  562.37  562.65  562.94  563.52   563.9  564.77     565  565.53  565.61
  566.22  566.58  566.74  566.75  566.76  567.05  567.47  567.89  568.73  568.86
  568.97  569.12  569.17   569.6  569.76     570  570.19  568.82
  570.43  569.76  568.54  568.47  567.41  567.33  566.01  563.44  559.77  556.37
  555.15  554.79  554.73  552.88  551.55  552.18  551.73   550.8  541.35   541.3
  556.57  556.57  556.75  557.79  557.97  557.98  541.35   541.4  548.96  551.23
  552.87  556.68  558.22  559.41  562.17  563.19  563.96  564.74  565.27  565.35
  565.59  565.76  565.94  566.34  566.39  566.49  566.37  566.61  567.58  567.56
  567.51  567.83     568  568.56  568.95   568.6  568.57  568.57
Pier Skew, UpSta & Num, DnSta & Num=,5000.0, 2 ,5000.0, 2 , 0 , 0 , 0 ,,
     1.5     1.5
   537.6  558.54
     1.5     1.5
  537.35  558.29
BR Coef= 1 , 1 , 0 ,1.25, 0 ,,,0.8,0,2,0,
Wspro=,,,, 1 ,,,, 0 ,,,, 0 ,,,,-1 ,-1 ,-1 , 0 , 0 , 0 , 0 , 0
BC Design=,, 0 ,, 0 ,,,,,,
BR U #Sta/Elev= 58
  4722.2  570.68  4732.8  570.01  4752.2  568.79  4752.8  568.72  4762.2  567.66
  4762.8  567.58  4772.2  566.26  4792.8  563.69  4822.2  560.02  4842.2  556.62
  4852.2   555.4  4862.2  555.04  4862.8  554.98  4882.2  553.13  4922.2   551.8
  4952.2  552.43  4962.2  551.98  4972.2  551.05  4975.3   541.6 4975.41  541.55
  4975.5  541.51  4975.6  541.47    4982   538.6    5018   538.6  5024.2  541.51
 5024.29  541.55  5024.4   541.6  5024.5  541.65  5041.1  549.21  5051.1  551.48
  5061.1  553.12  5081.1  556.93  5091.1  558.47  5101.1  559.66  5121.1  562.42
  5134.2  563.44  5144.2  564.21  5154.2  564.99  5161.1  565.52  5164.2   565.6
  5174.2  565.84  5181.1  566.01  5184.2  566.19  5191.1  566.59  5194.2  566.64
  5201.1  566.74  5211.1  566.62  5221.1  566.86  5241.1  567.83  5244.2  567.81
  5251.1  567.76  5261.1  568.08  5264.2  568.25  5274.2  568.81  5281.1   569.2
  5291.1  568.85  5299.3  568.82  5299.7  568.82
BR U #Mann= 3
 4722.20    0.14  4975.3    0.05  5024.2    0.12
BR U Banks=4975.30,5024.20
BR D #Sta/Elev= 58
  4722.2  570.43  4732.8  569.76  4752.2  568.54  4752.8  568.47  4762.2  567.41
  4762.8  567.33  4772.2  566.01  4792.8  563.44  4822.2  559.77  4842.2  556.37
  4852.2  555.15  4862.2  554.79  4862.8  554.73  4882.2  552.88  4922.2  551.55
  4952.2  552.18  4962.2  551.73  4972.2   550.8  4975.3  541.35 4975.41   541.3
  4975.5  541.26  4975.6  541.22    4982  538.35    5018  538.35  5024.2  541.26
 5024.29   541.3  5024.4  541.35  5024.5   541.4  5041.1  548.96  5051.1  551.23
  5061.1  552.87  5081.1  556.68  5091.1  558.22  5101.1  559.41  5121.1  562.17
  5134.2  563.19  5144.2  563.96  5154.2  564.74  5161.1  565.27  5164.2  565.35
  5174.2  565.59  5181.1  565.76  5184.2  565.94  5191.1  566.34  5194.2  566.39
  5201.1  566.49  5211.1  566.37  5221.1  566.61  5241.1  567.58  5244.2  567.56
  5251.1  567.51  5261.1  567.83  5264.2     568  5274.2  568.56  5281.1  568.95
  5291.1   568.6  5299.3  568.57  5299.7  568.57
BR D #Mann= 3
 4722.20    0.14  4975.3    0.05  5024.2    0.12
BR D Banks=4975.30,5024.20

Type RM Length L Ch R = 1 ,56660.5,694.85,694.85,694.85
XS GIS Cut Line= 3
 1981767.6214876 877087.11634598 1981856.6724462 876819.51986606
 1981961.0643448 876543.45434980
BEGIN DESCRIPTION:
Downstream Section of Bridge/Culvert/Weir
END DESCRIPTION:
#Sta/Elev= 30
  4722.2  570.43  4752.2  568.54  4762.2  567.41  4822.2  559.77  4842.2  556.37
  4852.2  555.15  4862.2  554.79  4882.2  552.88  4922.2  551.55  4952.2  552.18
  4962.2  551.73  4972.2   550.8  4975.3  541.35    4982  538.35    5018  538.35
  5024.2  541.26  5041.1  548.96  5051.1  551.23  5061.1  552.87  5081.1  556.68
  5091.1  558.22  5121.1  562.17  5161.1  565.27  5181.1  565.76  5191.1  566.34
  5211.1  566.37  5241.1  567.58  5251.1  567.51  5281.1  568.95  5299.7  568.57
#Mann= 3 , 1 , 0
 4722.20    0.14       0  4975.3    0.05       0  5024.2    0.12       0
#XS Ineff= 2 , 0
       0 4968.63  556.06 5030.87       0  560.72
Bank Sta=4975.30,5024.20
Exp/Cntr=0.5,0.3

Type RM Length L Ch R = 1 ,55965.6,667,667,667
XS GIS Cut Line= 3
 1982040.4888771 877431.82773930 1982083.0374471 877351.45821829
 1982160.2785661 877222.91817989
BEGIN DESCRIPTION:
South Fork Little River 112.0
END DESCRIPTION:
#Sta/Elev= 16
  4913.6  563.08  4943.6  552.76  4953.6  550.46  4963.6  548.69  4983.6  549.19
  4985.9  541.11  4987.4  538.11  5012.5  538.11    5014  541.11  5014.5  547.09
  5034.5  548.14  5064.5  547.41  5084.5  549.67  5104.5  555.62  5114.5   557.9
  5154.5  563.46
#Mann= 3 , 1 , 0
 4913.60    0.14       0  4985.9    0.05       0    5014    0.12       0
Bank Sta=4985.90,5014.00
Exp/Cntr=0.3,0.1

Type RM Length L Ch R = 1 ,55298.6,0,0,0
XS GIS Cut Line= 3
 1982654.6184867 877346.34801917 1982605.1800384 877193.08882949
 1982555.7415901 877036.53374325
BEGIN DESCRIPTION:
South Fork Little River 111.0
END DESCRIPTION:
#Sta/Elev= 25
  4841.7  563.02  4851.7  563.17  4881.7  562.08  4891.7  561.18  4901.7  559.98
  4921.7  556.65  4931.7  554.54  4941.7  552.84  4951.7  550.58  4961.7  547.37
  4971.7  545.51    4986  538.83  4987.5  535.83  5012.6  535.83  5014.1  538.83
  5022.7  541.05  5032.7  543.92  5052.7  546.57  5062.7  547.25  5082.7  547.54
  5092.7  548.12  5112.7  553.05  5122.7  556.54  5142.7  560.92  5166.9  564.93
#Mann= 3 , 1 , 0
 4841.70    0.14       0    4986    0.05       0  5014.1    0.12       0
Bank Sta=4986.00,5014.10
Exp/Cntr=0.3,0.1

Chan Stop Cuts=-1