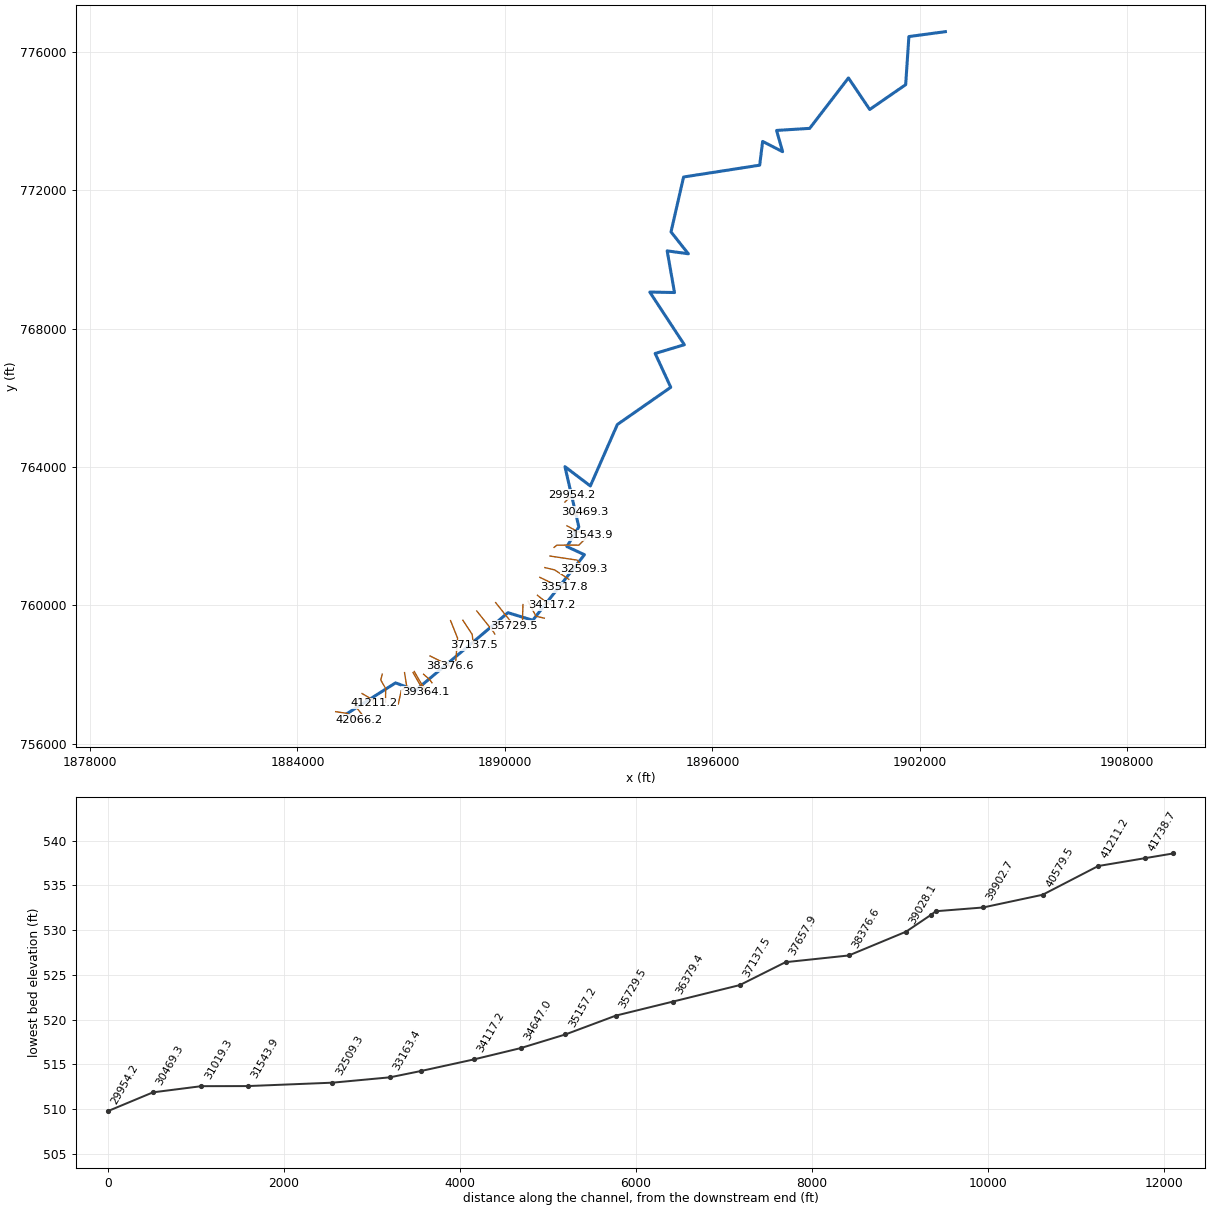
--- SOUTH FORK.PRJ (project) ---

Proj Title=South Fork
Current Plan=p01
Default Exp/Contr=0.3,0.1
English Units
Geom File=g01
Flow File=f01
Plan File=p01
Y Axis Title=Elevation
X Axis Title(PF)=Main Channel Distance
X Axis Title(XS)=Station
BEGIN DESCRIPTION:
####(Watershed Name)####
SOUTH FORK
HCFCD Unit X###-##-##
(Flood Hazard, Floodway) Model
10, 2, 1, 0.2% Event
Filename:  N:\NC_flood\60273\Approximates\Eng\Haw-Big_Alamance\Eng\South Fork\South Fork.prj
Prepared by:  ________     Date: ________
Reviewed by:  ________     Date: ________
STATUS (Draft RAS, SVSQ, FINAL)
END DESCRIPTION:
DSS Export Rating Curves= 0
DSS Export Rating Curve Sorted= 0
DSS Export Volume Flow Curves= 0
DXF OffsetX= 0
DXF OffsetY= 0
DXF ScaleX= 1
DXF ScaleY= 10

--- SOUTH FORK.p01 (plan) ---

Plan Title=100-Year-Single
Program Version=3.10
Short Identifier=Plan01
Geom File=g01
Flow File=f01
Subcritical Flow
K Sum by GR= 0
Std Step Tol= 0.01
Critical Tol= 0.01
Num of Std Step Trials= 20
Max Error Tol= 0.3
Flow Tol Ratio= 0.001
Split Flow NTrial= 30
Split Flow Tol= 0.02
Split Flow Ratio= 0.02
Log Output Level= 0
Friction Slope Method= 1
Unsteady Friction Slope Method= 2
Parabolic Critical Depth
Global Vel Dist= 0 , 0 , 0
Global Log Level= 0
CheckData=True
Encroach Param=-1 ,10,10, 2
Encroach River=South Fork
Encroach Reach=Reach - 1
Encroach Node=42066.2
       1    4900    5060
Encroach Node=41738.7
       4      .7
Encroach Node=41211.2
       4      .7
Encroach Node=40579.5
       4      .7
Encroach Node=39902.7
       4      .7
Encroach Node=39364.1
       4      .7
Encroach Node=39340.1
       4      .7
Encroach Node=39316.1
       4      .7
Encroach Node=39028.1
       1    4908    5020
Encroach Node=38376.6
       4      .7
Encroach Node=37657.9
       4      .7
Encroach Node=37137.5
       4      .7
Encroach Node=36379.4
       4      .7
Encroach Node=35729.5
       4      .7
Encroach Node=35157.2
       4      .7
Encroach Node=34647.0
       4      .7
Encroach Node=34117.2
       4      .7
Encroach Node=33517.8
       4      .7
Encroach Node=33163.4
       4      .7
Encroach Node=32509.3
       4      .7
Encroach Node=31543.9
       4      .7
Encroach Node=31019.3
       4      .7
Encroach Node=30469.3
       1    4915    5023
Encroach Node=29954.2
       1    4965    5065
Encroach Node=29279.5
       1    4920    5024
Encroach Node=28588.0
       1    4951    5049
Encroach Node=28563.2
       1    4951    5049
Encroach Node=28538.5
       1    4951    5049
Encroach Node=27711.1
       1    4885    5045
Encroach Node=26906.6
       1    4930    5030
Encroach Node=26251.7
       4      .7
Encroach Node=25702.1
       4      .7
Encroach Node=24917.9
       4      .7
Encroach Node=24489.8
       4      .7
Encroach Node=23965.0
       4      .7
Encroach Node=23408.3
       4      .7
Encroach Node=22653.5
       4      .7
Encroach Node=22043.5
       4      .7
Encroach Node=21225.0
       4      .7
Encroach Node=20822.9
       4      .7
Encroach Node=20172.4
       4      .7
Encroach Node=19638.4
       4      .7
Encroach Node=19342.5
       4      .7
Encroach Node=18605.2
       4      .7
Encroach Node=17800.8
       1    4950    5035
Encroach Node=17311.3
       1    4956    5020
Encroach Node=16827.0
       1    4977    5038
Encroach Node=15974.4
       1    4863    5040
Encroach Node=15553.0
       1    4920    5040
Encroach Node=15001.3
       1    4960    5080
Encroach Node=14388.1
       4      .7
Encroach Node=13401.2
       4      .7
Encroach Node=12988.1
       4      .7
Encroach Node=12487.4
       4      .7
Encroach Node=11922.5
       4      .7
Encroach Node=11422.5
       4      .7
Encroach Node=10892.0
       4      .7
Encroach Node=10398.0
       4      .7
Encroach Node=9869.8
       1    4962    5300
Encroach Node=9292.4
       1    4947    5072
Encroach Node=9268.4
       1    4947    5072
Encroach Node=9244.4
       1    4947    5072
Encroach Node=8646.7
       4      .7
Encroach Node=7836.9
       4      .7
Encroach Node=7371.8
       4      .7
Encroach Node=6890.2
       4      .7
Encroach Node=6463.1
       4      .7
Encroach Node=6042.5
       4      .7
Encroach Node=5470.5
       4      .7
Encroach Node=4977.0
       4      .7
Encroach Node=3890.4
       1    4645    5025
Encroach Node=3383.9
       4      .7
Encroach Node=2773.4
       4      .7
Encroach Node=1895.0
       4      .7
Encroach Node=1177.0
       4      .7
Encroach Node=527.3
       1    4965    5025
Computation Interval=1HOUR
Output Interval=1HOUR
Run HTab= 0
Run UNet= 0
Run PostProcess= 0
UNET Theta= 1
UNET Theta Warmup= 1
UNET ZTol= 0.02
UNET ZSATol= 0.05
UNET MxIter= 20
UNET MaxInSteps= 1
UNET DtIC= 0
UNET DtMin= 0
UNET MaxCRTS= 20
UNET WFStab= 2
UNET SFStab= 1
UNET WFX= 1
UNET SFX= 1
UNET DSS MLevel= 4
UNET Convert EG Bridges=-1
UNET Use Existing IB Tables=-1
UNET Froude Reduction=False
UNET Froude Limit= 1
UNET Froude Power= 10
Instantaneous Interval=1HOUR
Write IC File= 0
Echo Input=False
Echo Output=False
Write Detailed= 0

--- SOUTH FORK.f01 (steady flow) ---

Flow Title= 100-Year-Single
Program Version=3.10
Number of Profiles= 2
Profile Names=100-Year,AFW
River Rch & RM=South Fork,Reach - 1       ,42066.2
    2070    2070
River Rch & RM=South Fork,Reach - 1       ,41211.2
    2110    2110
River Rch & RM=South Fork,Reach - 1       ,39364.1
    2420    2420
River Rch & RM=South Fork,Reach - 1       ,39316.1
    2590    2590
River Rch & RM=South Fork,Reach - 1       ,34117.2
    3140    3140
River Rch & RM=South Fork,Reach - 1       ,28588
    3260    3260
River Rch & RM=South Fork,Reach - 1       ,20822.9
    3650    3650
River Rch & RM=South Fork,Reach - 1       ,19638.4
    3710    3710
River Rch & RM=South Fork,Reach - 1       ,14388.1
    5050    5050
River Rch & RM=South Fork,Reach - 1       ,10398
    5230    5230
River Rch & RM=South Fork,Reach - 1       ,9292.4
    5380    5380
River Rch & RM=South Fork,Reach - 1       ,1895.0
    5390    5390
Boundary for River Rch & Prof#=South Fork,Reach - 1       , 1
Up Type= 0
Dn Type= 3
Dn Slope=0.003
DSS Import GetInterval= 0
DSS Import GetPeak= 0
DSS Import FillOption= 0

--- SOUTH FORK.g01 (geometry) ---

Geom Title=Geom 01 by CodeH2 for Windows

River Reach=South Fork,Reach - 1
Reach XY= 30
      1885439.28       756872.32      1886835.63       757756.88
         1887420       757542.69         1890087       759786.88
      1890804.75       759568.13      1892298.88       761463.94
      1891792.38       761699.31      1892136.88        762267.5
      1891735.63       764010.13      1892470.25          763453
      1893251.38       765229.69      1894795.75       766306.19
      1894344.75       767284.31      1895188.75       767537.31
      1894189.25       769060.38      1894904.13       769046.81
      1894692.13       770252.06      1895304.13       770166.88
      1894803.13       770800.19      1895166.88       772388.13
      1897367.38       772729.75      1897453.13       773416.56
      1898031.25       773120.19      1897856.13       773734.69
      1898813.63       773794.38      1899934.63       775252.94
      1900549.38       774340.56       1901589.5       775058.19
      1901682.75       776449.44      1902738.13       776591.31

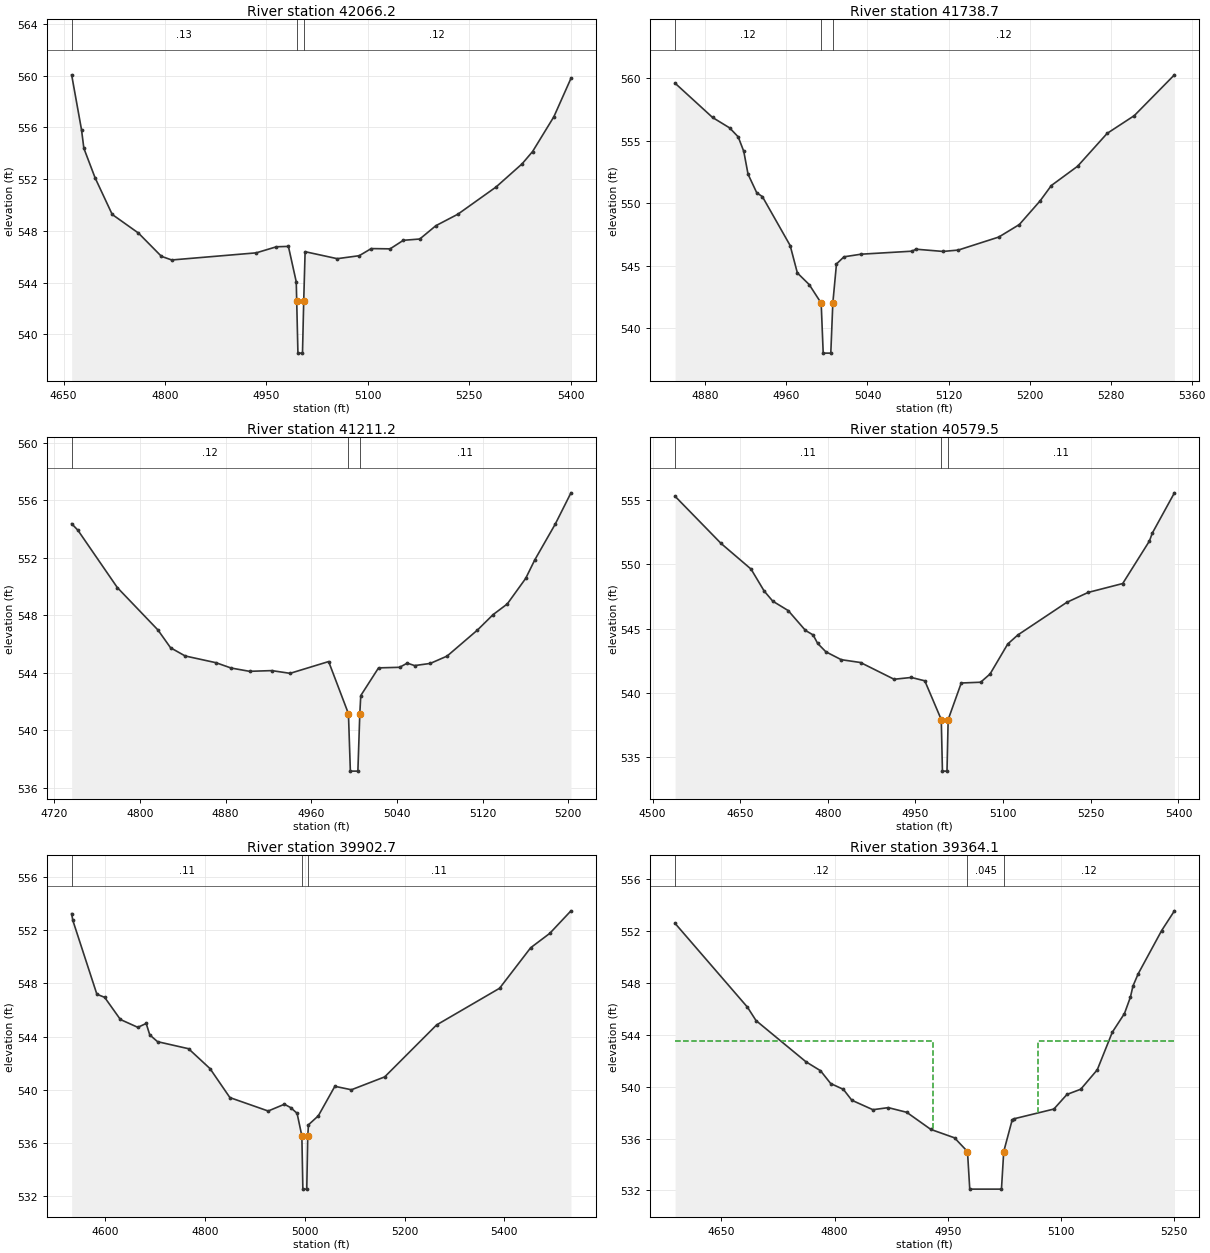
Type RM Length L Ch R = 1 ,42066.2,327.5,327.5,327.5
XS GIS Cut Line= 3
      1885105.61       756924.79      1885434.16       756875.09
      1885791.74       756682.35
BEGIN DESCRIPTION:
South Fork 67.0
END DESCRIPTION:
#Sta/Elev= 30
  4661.9  560.07  4676.5  555.83    4680  554.39  4696.6  552.11  4721.9  549.28
  4760.7  547.84  4794.7  546.04    4810  545.76  4934.8  546.31  4964.8  546.78
  4982.5  546.81  4994.1  544.07 4994.78  542.56 4996.58  538.56 5003.33  538.56
 5005.13  542.56  5007.2   546.4  5054.7  545.86  5087.2  546.09    5105  546.64
  5132.9  546.62  5152.5  547.28  5176.8  547.38  5200.6  548.41  5233.2   549.3
  5289.6   551.4  5328.1  553.19  5343.6  554.14  5375.1  556.83  5400.4   559.8
#Mann= 3 , 1 , 0
 4661.90    0.13       0 4994.78    0.05       0 5005.13    0.12       0
Bank Sta=4994.78,5005.13
Exp/Cntr=0.3,0.1

Type RM Length L Ch R = 1 ,41738.7,527.5,527.5,527.5
XS GIS Cut Line= 3
      1885662.57       757246.50      1885663.33       757101.65
      1885878.79       756828.32
BEGIN DESCRIPTION:
South Fork 66.0
END DESCRIPTION:
#Sta/Elev= 30
  4850.1   559.6  4887.1  556.86  4903.9  556.03  4912.4  555.31  4917.9  554.15
  4922.1  552.33  4930.7  550.84  4936.3  550.53  4963.7  546.62  4970.8  544.43
  4982.5   543.5  4994.3  542.02  4996.3  538.02  5003.8  538.02  5005.8  542.02
  5009.4  545.15  5016.8  545.72  5033.7  545.93    5084  546.17  5087.8  546.33
  5114.6  546.15  5129.6  546.26  5169.6   547.3  5189.9   548.3  5210.4  550.19
  5221.5  551.42  5247.4  552.96  5276.6  555.59  5303.4  557.01    5343  560.27
#Mann= 3 , 1 , 0
 4850.10    0.12       0  4994.3    0.05       0  5005.8    0.12       0
Bank Sta=4994.30,5005.80
Exp/Cntr=0.3,0.1

Type RM Length L Ch R = 1 ,41211.2,631.7,631.7,631.7
XS GIS Cut Line= 4
      1885866.50       757449.91      1886099.96       757314.33
      1886179.51       757272.38      1886206.14       757169.38
BEGIN DESCRIPTION:
South Fork 65.0
END DESCRIPTION:
#Sta/Elev= 30
  4736.2  554.38    4742  553.93  4778.9  549.93  4816.8  546.98  4828.6  545.74
  4842.2  545.17    4871   544.7  4885.1  544.33  4902.3   544.1  4923.1  544.15
  4940.2  543.96  4976.2  544.78 4994.69  541.15 4996.49  537.15 5003.51  537.15
 5005.31  541.15  5006.2  542.41  5022.8  544.34  5042.5  544.38  5049.6  544.67
  5056.5   544.5  5071.1  544.65  5086.8  545.16  5115.1  546.97  5129.8  548.05
    5143  548.79  5160.2  550.57  5168.7  551.86  5187.8  554.35  5202.5  556.53
#Mann= 3 , 1 , 0
 4736.20    0.12       0 4994.69    0.05       0 5005.31    0.11       0
Bank Sta=4994.69,5005.31
Exp/Cntr=0.3,0.1

Type RM Length L Ch R = 1 ,40579.5,676.8,676.8,676.8
XS GIS Cut Line= 4
      1886451.28       758007.99      1886408.68       757840.09
      1886550.48       757594.71      1886547.32       757196.85
BEGIN DESCRIPTION:
South Fork 64.0
END DESCRIPTION:
#Sta/Elev= 30
  4538.6  555.27  4617.3  551.61  4668.6  549.62    4691  547.92  4705.8  547.13
  4732.2   546.4  4761.7  544.86  4774.8  544.51  4782.6  543.85  4796.7   543.2
  4822.9  542.59  4855.9  542.37  4913.4  541.07  4942.8  541.21  4965.9  540.95
  4994.1  537.94  4996.1  533.94  5003.9  533.94  5005.9  537.94  5028.3  540.78
  5061.5  540.84  5077.6  541.48  5107.9  543.81  5125.2  544.51  5208.9  547.04
  5245.5  547.81  5304.6   548.5  5350.3   551.8  5355.2  552.41  5393.1  555.54
#Mann= 3 , 1 , 0
 4538.60    0.11       0  4994.1   0.045       0  5005.9    0.11       0
Bank Sta=4994.10,5005.90
Exp/Cntr=0.3,0.1

Type RM Length L Ch R = 1 ,39902.7,538.6,538.6,538.6
XS GIS Cut Line= 5
      1887096.59       758054.49      1887158.68       757657.80
      1887114.72       757616.41      1887002.43       757538.01
      1886915.46       757145.69
BEGIN DESCRIPTION:
South Fork 63.0
END DESCRIPTION:
#Sta/Elev= 30
  4532.7  553.26    4535  552.76  4583.3  547.19  4598.8  546.96  4630.4  545.29
  4665.3   544.7  4682.1  544.99  4689.3  544.13  4704.9  543.62    4767  543.09
  4810.1  541.59  4849.9  539.41  4926.6   538.4  4959.1  538.91  4971.5  538.66
  4984.5  538.23  4994.1  536.52  4996.1  532.52  5003.9  532.52  5005.9  536.52
  5007.3  537.36  5027.1  538.04  5060.2  540.26  5093.4     540  5160.1  540.97
  5264.1  544.88  5390.3  547.64  5452.6  550.69  5490.8  551.77  5533.4  553.47
#Mann= 3 , 1 , 0
 4532.70    0.11       0  4994.1   0.045       0  5005.9    0.11       0
Bank Sta=4994.10,5005.90
Exp/Cntr=0.5,0.3

Type RM Length L Ch R = 1 ,39364.1,48,48,48
XS GIS Cut Line= 3
      1887340.42       758056.86      1887548.52       757698.28
      1887699.93       757503.37
BEGIN DESCRIPTION:
Upstream Section of Bridge/Culvert/Weir
END DESCRIPTION:
#Sta/Elev= 30
  4588.7  552.61  4684.6  546.14  4695.9  545.11    4762  541.93  4781.3  541.24
  4794.8  540.25  4811.6   539.8  4822.8  538.96  4850.7  538.23  4871.1  538.39
  4895.5  538.03  4927.4  536.71  4958.8  536.06    4976     535    4979   532.1
    5021   532.1    5024     535  5035.1  537.42    5037  537.52  5090.4  538.28
  5107.8  539.41    5126  539.81  5147.9  541.31  5167.8  544.21  5183.9  545.65
  5191.8  546.92  5195.2  547.78  5202.1  548.72  5233.2  552.06  5250.1  553.58
#Mann= 3 , 1 , 0
 4588.70    0.12       0    4976   0.045       0    5024    0.12       0
#XS Ineff= 2 , 0
       0    4930   543.5    5070       0   543.5
Bank Sta=4976.00,5024.00
Exp/Cntr=0.5,0.3

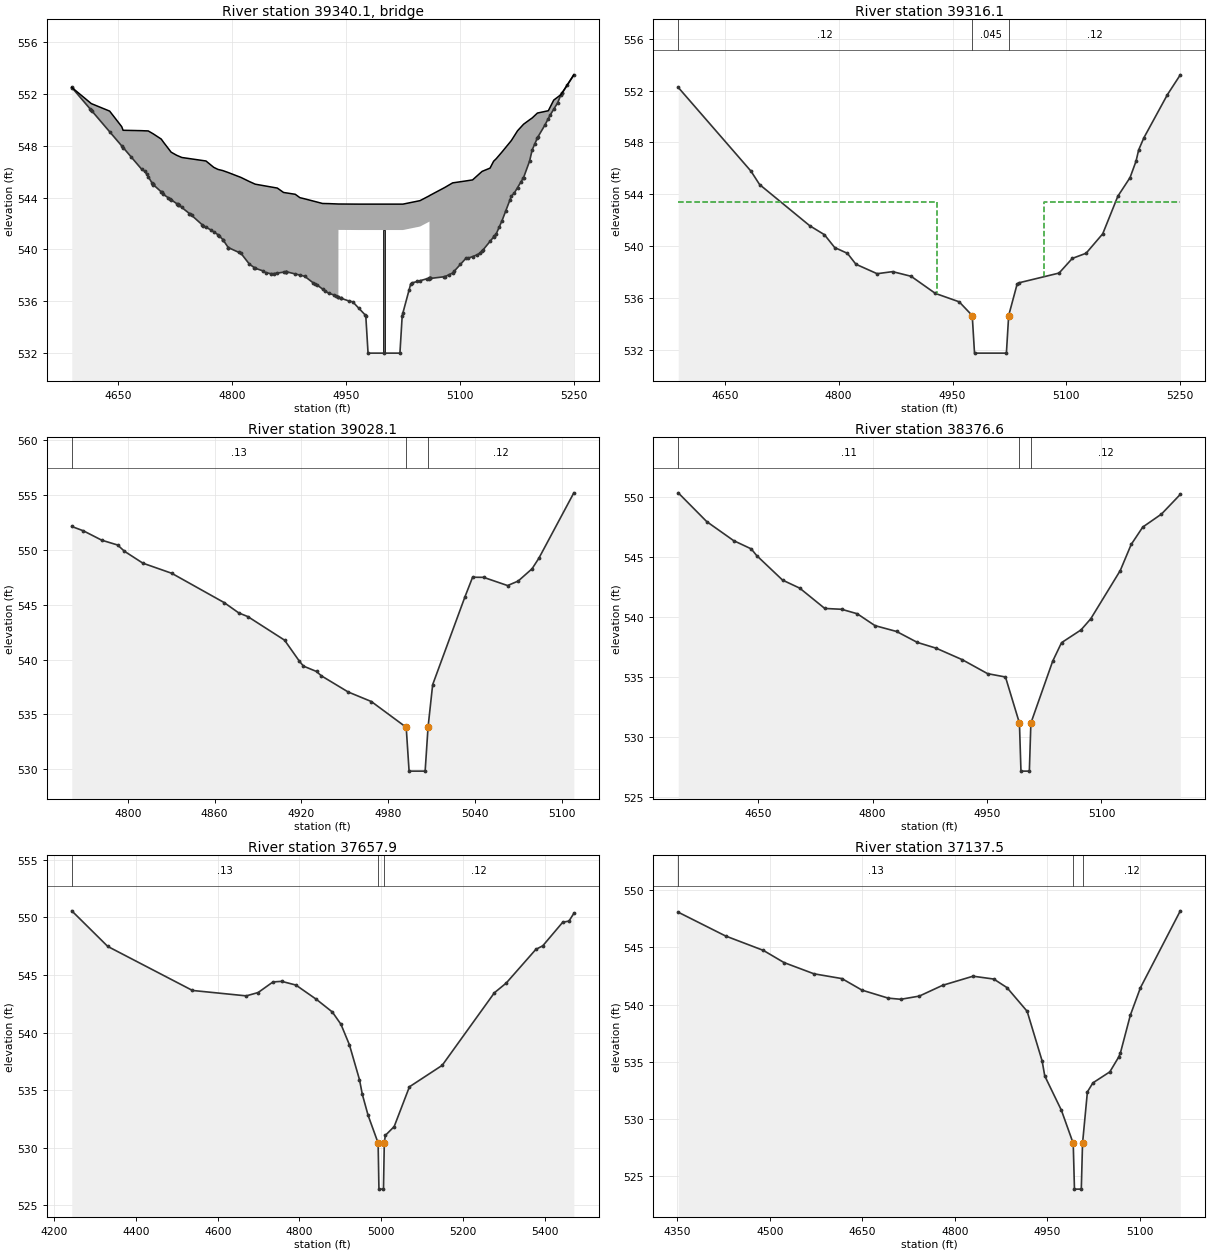
Type RM Length L Ch R = 3 ,39340.1,,,
BEGIN DESCRIPTION:
South Fork - Moon Lindley Rd
Structure ID: NCF-0379
Approximate Survey Structure
END DESCRIPTION:
Bridge Culvert--1,0,-1,-1, 0
Deck Dist Width WeirC Skew NumUp NumDn MinLoCord MaxHiCord MaxSubmerge Is_Ogee
10,28,2.6,, 60, 60,,,0.95,0,1,1,,
  4588.7  4614.4  4638.6  4654.5  4656.3  4680.8  4684.6  4689.4  4695.9  4706.6
  4709.4  4719.6  4726.9  4733.7  4765.5  4775.7  4781.3  4787.6  4794.8  4811.6
  4822.8  4830.4  4850.7  4859.5  4867.7  4871.1  4883.1  4889.2  4895.5  4919.1
  4927.4 4939.91    4940    4967  5024.9  5047.5 5059.89    5060  5080.2  5090.4
  5107.8  5116.7    5126  5129.3  5139.7  5144.4  5147.9  5155.5  5167.8  5171.8
  5175.9  5183.9  5191.8  5195.2  5202.1  5216.5  5223.6  5228.8  5233.2  5250.1
  552.51  551.26  550.68  549.48   549.2  549.17  549.16  549.15  548.93  548.52
  548.29  547.51  547.27   547.1  546.83  546.34  546.18  546.09  545.94  545.56
  545.24  545.04  544.83  544.74   544.4  544.37  544.26     544  543.91  543.55
  543.54  543.51  543.51   543.5   543.5  543.77  544.15  544.16  544.79  545.14
  545.29  545.37  545.86  546.03  546.28  546.81  547.01  547.53  548.41  548.78
  549.16  549.67  550.01  550.15  550.53  550.71  551.53  551.76  551.96  553.48
  552.51  550.75  549.09  547.99  547.87  546.19  546.04  545.62  545.01  544.45
  544.25  543.84  543.54  543.24  541.72  541.36  541.14  540.77  540.15   539.7
  538.86  538.55  538.13  538.18  538.25  538.29  538.11  538.02  537.93  536.94
  536.61  536.33  541.51   541.5   541.5  541.77  542.15  537.76   537.9  538.18
  539.31  539.45  539.71  539.89  540.63  540.96  541.21  542.22  544.11  544.37
  544.77  545.55  546.82  547.68  548.62   550.1  550.82  551.32  551.96  553.48
  4588.7  4614.4  4638.6  4654.5  4656.3  4680.8  4684.6  4689.4  4695.9  4706.6
  4709.4  4719.6  4726.9  4733.7  4765.5  4775.7  4781.3  4787.6  4794.8  4811.6
  4822.8  4830.4  4850.7  4859.5  4867.7  4871.1  4883.1  4889.2  4895.5  4919.1
  4927.4 4939.91    4940    4967  5024.9  5047.5 5059.89    5060  5080.2  5090.4
  5107.8  5116.7    5126  5129.3  5139.7  5144.4  5147.9  5155.5  5167.8  5171.8
  5175.9  5183.9  5191.8  5195.2  5202.1  5216.5  5223.6  5228.8  5233.2  5250.1
  552.51  551.26  550.68  549.48   549.2  549.17  549.16  549.15  548.93  548.52
  548.29  547.51  547.27   547.1  546.83  546.34  546.18  546.09  545.94  545.56
  545.24  545.04  544.83  544.74   544.4  544.37  544.26     544  543.91  543.55
  543.54  543.51  543.51   543.5   543.5  543.77  544.15  544.16  544.79  545.14
  545.29  545.37  545.86  546.03  546.28  546.81  547.01  547.53  548.41  548.78
  549.16  549.67  550.01  550.15  550.53  550.71  551.53  551.76  551.96  553.48
  552.26   550.5  548.84  547.74  547.62  545.94  545.79  545.37  544.76   544.2
     544  543.59  543.29  542.99  541.47  541.11  540.89  540.52   539.9  539.45
  538.61   538.3  537.88  537.93     538  538.04  537.86  537.77  537.68  536.69
  536.36  536.08  541.26  541.25  541.25  541.52   541.9  537.51  537.65  537.93
  539.06   539.2  539.46  539.64  540.38  540.71  540.96  541.97  543.86  544.12
  544.52   545.3  546.57  547.43  548.37  549.85  550.57  551.07  551.71  553.23
Pier Skew, UpSta & Num, DnSta & Num=,5000.0, 2 ,5000.0, 2 , 0 , 0 , 0 ,,
     1.5     1.5
     531   542.5
     1.5     1.5
  530.75  542.25
Abutment Skew #Up #Dn=, 2 , 2
 4939.80 4967.00
  541.51  535.45
 4939.80 4967.00
  541.26  535.20
Abutment Skew #Up #Dn=, 2 , 2
 5033.00 5060.09
  536.86  542.15
 5033.00 5060.09
  536.61  541.90
BR Coef= 1 , 1 , 0 ,1.25, 0 ,,,0.8,0,2,0,
Wspro=,,,, 1 ,,,, 0 ,,,, 0 ,,,,-1 ,-1 ,-1 , 0 , 0 , 0 , 0 , 0
BC Design=,, 0 ,, 0 ,,,,,,
BR U #Sta/Elev= 134
  4588.7  552.51  4589.1  552.48  4613.3  550.82  4614.4  550.75  4615.7  550.66
  4638.6  549.09  4654.5  547.99  4656.3  547.87  4667.2  547.12  4680.8  546.19
  4684.6  546.04  4687.4  545.82  4689.4  545.62  4694.6  545.11  4695.3  545.06
  4695.8  545.02  4695.9  545.01  4706.6  544.45  4707.1  544.42  4709.4  544.25
    4716  543.98  4718.4  543.89  4719.6  543.84  4726.9  543.54  4728.4  543.48
  4729.1  543.43  4729.8  543.43  4733.7  543.24  4743.6  542.77  4743.9  542.76
  4746.5  542.64  4760.4  541.91    4762  541.83  4765.5  541.72  4771.8  541.51
  4775.7  541.36  4781.3  541.14  4782.5  541.07  4787.6  540.77  4788.2  540.72
  4794.8  540.15  4795.1  540.14  4808.7  539.78  4811.6   539.7  4822.8  538.86
  4829.4  538.59  4830.4  538.55  4840.4  538.35    4844  538.22  4850.7  538.13
  4854.8  538.14  4859.5  538.18  4867.7  538.25  4870.6  538.27  4871.1  538.29
  4871.4  538.28  4883.1  538.11  4889.2  538.02  4895.5  537.93  4906.8  537.42
  4909.3  537.33  4911.9  537.26  4919.1  536.94  4922.3   536.8  4927.4  536.61
  4933.6   536.5  4936.8  536.41 4939.91  536.33    4940  536.33  4942.8  536.25
  4942.9  536.25  4953.4  536.03  4958.8  535.96    4967  535.45  4974.8  534.97
    4976   534.9    4979     532  4999.9     532    5021     532    5024   534.9
  5024.9   535.1    5033  536.86  5035.1  537.32    5037  537.42    5044  537.53
  5047.5  537.59  5056.6  537.74  5059.6  537.75 5059.89  537.76    5060  537.76
  5060.1  537.76  5060.6  537.76  5079.6   537.9  5080.2   537.9  5085.8  538.05
  5090.4  538.18  5092.8  538.34  5100.7  538.85  5107.8  539.31    5111  539.33
  5116.7  539.45  5122.9  539.59    5126  539.71  5129.3  539.89    5130  539.93
  5139.7  540.63  5144.4  540.96  5145.2  541.02  5147.9  541.21  5152.1  541.77
  5155.5  542.22  5160.2  542.94  5165.8   543.8  5167.8  544.11  5171.8  544.37
  5175.9  544.77  5180.7  545.24  5183.6  545.52  5183.9  545.55  5191.8  546.82
  5195.2  547.68  5198.8  548.17  5202.1  548.62  5202.4  548.65  5211.7  549.57
  5216.5   550.1    5219  550.38  5223.6  550.82  5228.8  551.32  5233.2  551.96
  5234.3  552.04  5235.1  552.11  5241.5   552.7  5250.1  553.48
BR U #Mann= 3
 4588.70    0.12    4976   0.045    5024    0.12
BR U Banks=4976.00,5024.00
BR D #Sta/Elev= 134
  4588.7  552.26  4589.1  552.23  4613.3  550.57  4614.4   550.5  4615.7  550.41
  4638.6  548.84  4654.5  547.74  4656.3  547.62  4667.2  546.87  4680.8  545.94
  4684.6  545.79  4687.4  545.57  4689.4  545.37  4694.6  544.86  4695.3  544.81
  4695.8  544.77  4695.9  544.76  4706.6   544.2  4707.1  544.17  4709.4     544
    4716  543.73  4718.4  543.64  4719.6  543.59  4726.9  543.29  4728.4  543.23
  4729.1  543.18  4729.8  543.18  4733.7  542.99  4743.6  542.52  4743.9  542.51
  4746.5  542.39  4760.4  541.66    4762  541.58  4765.5  541.47  4771.8  541.26
  4775.7  541.11  4781.3  540.89  4782.5  540.82  4787.6  540.52  4788.2  540.47
  4794.8   539.9  4795.1  539.89  4808.7  539.53  4811.6  539.45  4822.8  538.61
  4829.4  538.34  4830.4   538.3  4840.4   538.1    4844  537.97  4850.7  537.88
  4854.8  537.89  4859.5  537.93  4867.7     538  4870.6  538.02  4871.1  538.04
  4871.4  538.03  4883.1  537.86  4889.2  537.77  4895.5  537.68  4906.8  537.17
  4909.3  537.08  4911.9  537.01  4919.1  536.69  4922.3  536.55  4927.4  536.36
  4933.6  536.25  4936.8  536.16 4939.91  536.08    4940  536.08  4942.8     536
  4942.9     536  4953.4  535.78  4958.8  535.71    4967   535.2  4974.8  534.72
    4976  534.65    4979  531.75  4999.9  531.75    5021  531.75    5024  534.65
  5024.9  534.85    5033  536.61  5035.1  537.07    5037  537.17    5044  537.28
  5047.5  537.34  5056.6  537.49  5059.6   537.5 5059.89  537.51    5060  537.51
  5060.1  537.51  5060.6  537.51  5079.6  537.65  5080.2  537.65  5085.8   537.8
  5090.4  537.93  5092.8  538.09  5100.7   538.6  5107.8  539.06    5111  539.08
  5116.7   539.2  5122.9  539.34    5126  539.46  5129.3  539.64    5130  539.68
  5139.7  540.38  5144.4  540.71  5145.2  540.77  5147.9  540.96  5152.1  541.52
  5155.5  541.97  5160.2  542.69  5165.8  543.55  5167.8  543.86  5171.8  544.12
  5175.9  544.52  5180.7  544.99  5183.6  545.27  5183.9   545.3  5191.8  546.57
  5195.2  547.43  5198.8  547.92  5202.1  548.37  5202.4   548.4  5211.7  549.32
  5216.5  549.85    5219  550.13  5223.6  550.57  5228.8  551.07  5233.2  551.71
  5234.3  551.79  5235.1  551.86  5241.5  552.45  5250.1  553.23
BR D #Mann= 3
 4588.70    0.12    4976   0.045    5024    0.12
BR D Banks=4976.00,5024.00

Type RM Length L Ch R = 1 ,39316.1,288,288,288
XS GIS Cut Line= 3
      1887377.31       758087.56      1887585.42       757728.98
      1887736.82       757534.07
BEGIN DESCRIPTION:
Downstream Section of Bridge/Culvert/Weir
END DESCRIPTION:
#Sta/Elev= 30
  4588.7  552.24  4684.6  545.77  4695.9  544.74    4762  541.56  4781.3  540.87
  4794.8  539.88  4811.6  539.43  4822.8  538.59  4850.7  537.86  4871.1  538.02
  4895.5  537.66  4927.4  536.34  4958.8  535.69    4976  534.63    4979  531.73
    5021  531.73    5024  534.63  5035.1  537.05    5037  537.15  5090.4  537.91
  5107.8  539.04    5126  539.44  5147.9  540.94  5167.8  543.84  5183.9  545.28
  5191.8  546.55  5195.2  547.41  5202.1  548.35  5233.2  551.69  5250.1  553.21
#Mann= 3 , 1 , 0
 4588.70    0.12       0    4976   0.045       0    5024    0.12       0
#XS Ineff= 2 , 0
       0    4930  543.43    5070       0  543.43
Bank Sta=4976.00,5024.00
Exp/Cntr=0.5,0.3

Type RM Length L Ch R = 1 ,39028.1,651.5,651.5,651.5
XS GIS Cut Line= 3
      1887647.80       758005.36      1887824.79       757852.52
      1887890.40       757760.21
BEGIN DESCRIPTION:
South Fork 62.0
END DESCRIPTION:
#Sta/Elev= 30
  4761.2  552.14  4769.3  551.74  4781.9  550.89  4792.9  550.45  4797.6  549.88
  4810.4  548.79  4830.3  547.87  4866.5   545.2  4876.7  544.25  4882.9  543.92
  4908.3  541.77  4918.6  539.84  4921.4   539.4  4930.4  538.91  4933.7  538.52
  4952.3  537.04  4968.3  536.17  4992.4  533.82  4994.4  529.82  5005.5  529.82
  5007.5  533.82  5010.7  537.71  5033.1  545.75  5038.3  547.51  5045.9   547.5
  5062.5  546.75  5069.8  547.16  5079.4  548.28  5084.1  549.24  5108.3  555.21
#Mann= 3 , 1 , 0
 4761.20    0.13       0  4992.4    0.05       0  5007.5    0.12       0
Bank Sta=4992.40,5007.50
Exp/Cntr=0.3,0.1

Type RM Length L Ch R = 1 ,38376.6,718.7,718.7,718.7
XS GIS Cut Line= 3
      1887834.77       758535.17      1888237.98       758336.03
      1888419.69       758233.80
BEGIN DESCRIPTION:
South Fork 61.0
END DESCRIPTION:
#Sta/Elev= 30
  4545.2  550.34  4582.6  547.94  4617.8  546.36  4640.9  545.67  4648.1  545.11
    4682  543.07  4704.5   542.4  4737.3  540.71  4759.4  540.64  4779.8  540.27
  4803.1  539.28  4831.5  538.79  4858.7  537.88  4883.3   537.4  4917.6  536.44
  4950.7  535.28  4974.2     535  4992.5  531.16  4994.5  527.16  5005.5  527.16
  5007.5  531.16  5036.1  536.32  5047.7  537.86  5073.2  538.92    5086  539.85
  5124.7  543.87    5139  546.04  5154.2  547.49  5178.7  548.57  5203.4  550.21
#Mann= 3 , 1 , 0
 4545.20    0.11       0  4992.5    0.05       0  5007.5    0.12       0
Bank Sta=4992.50,5007.50
Exp/Cntr=0.3,0.1

Type RM Length L Ch R = 1 ,37657.9,520.4,520.4,520.4
XS GIS Cut Line= 4
      1888427.58       759559.28      1888631.22       759050.18
      1888612.98       758848.18      1888577.79       758372.12
BEGIN DESCRIPTION:
South Fork 60.0
END DESCRIPTION:
#Sta/Elev= 30
  4242.9  550.56    4331  547.47  4538.2  543.65  4669.9  543.18  4698.9  543.47
  4735.3  544.39  4756.5  544.44  4791.2  544.12  4841.4  542.88  4880.5  541.78
  4901.6  540.71  4922.2  538.94  4946.9  535.91  4953.8  534.64    4968  532.81
  4992.5  530.41  4994.5  526.41  5005.6  526.41  5007.6  530.41  5010.1  531.07
  5031.8  531.84  5069.1  535.29  5149.2  537.15    5277  543.45  5305.9  544.29
  5378.3  547.21  5395.5  547.53  5444.2  549.57  5459.4  549.67  5471.4  550.34
#Mann= 3 , 1 , 0
 4242.90    0.13       0  4992.5    0.05       0  5007.6    0.12       0
Bank Sta=4992.50,5007.60
Exp/Cntr=0.3,0.1

Type RM Length L Ch R = 1 ,37137.5,758.1,758.1,758.1
XS GIS Cut Line= 4
      1888782.74       759569.30      1889053.09       759159.55
      1889070.45       759008.77      1889097.47       758838.68
BEGIN DESCRIPTION:
South Fork 59.0
END DESCRIPTION:
#Sta/Elev= 30
  4351.3  548.08  4428.1     546  4489.4  544.74  4523.1  543.67  4571.6  542.69
    4617  542.27  4649.6  541.26  4692.2  540.56  4712.6  540.46  4742.6  540.74
  4780.3  541.68  4829.8  542.48  4863.5  542.23  4884.9  541.48  4917.6  539.41
  4941.9  535.07  4946.2  533.75  4973.2  530.75  4992.4  527.85  4994.4  523.85
  5005.5  523.85  5007.5  527.85  5015.4  532.36  5024.4  533.15  5051.8  534.11
    5066  535.39    5069  535.77  5085.1  539.07  5101.4  541.46  5166.2   548.2
#Mann= 3 , 1 , 0
 4351.30    0.13       0  4992.4    0.05       0  5007.5    0.12       0
Bank Sta=4992.40,5007.50
Exp/Cntr=0.3,0.1

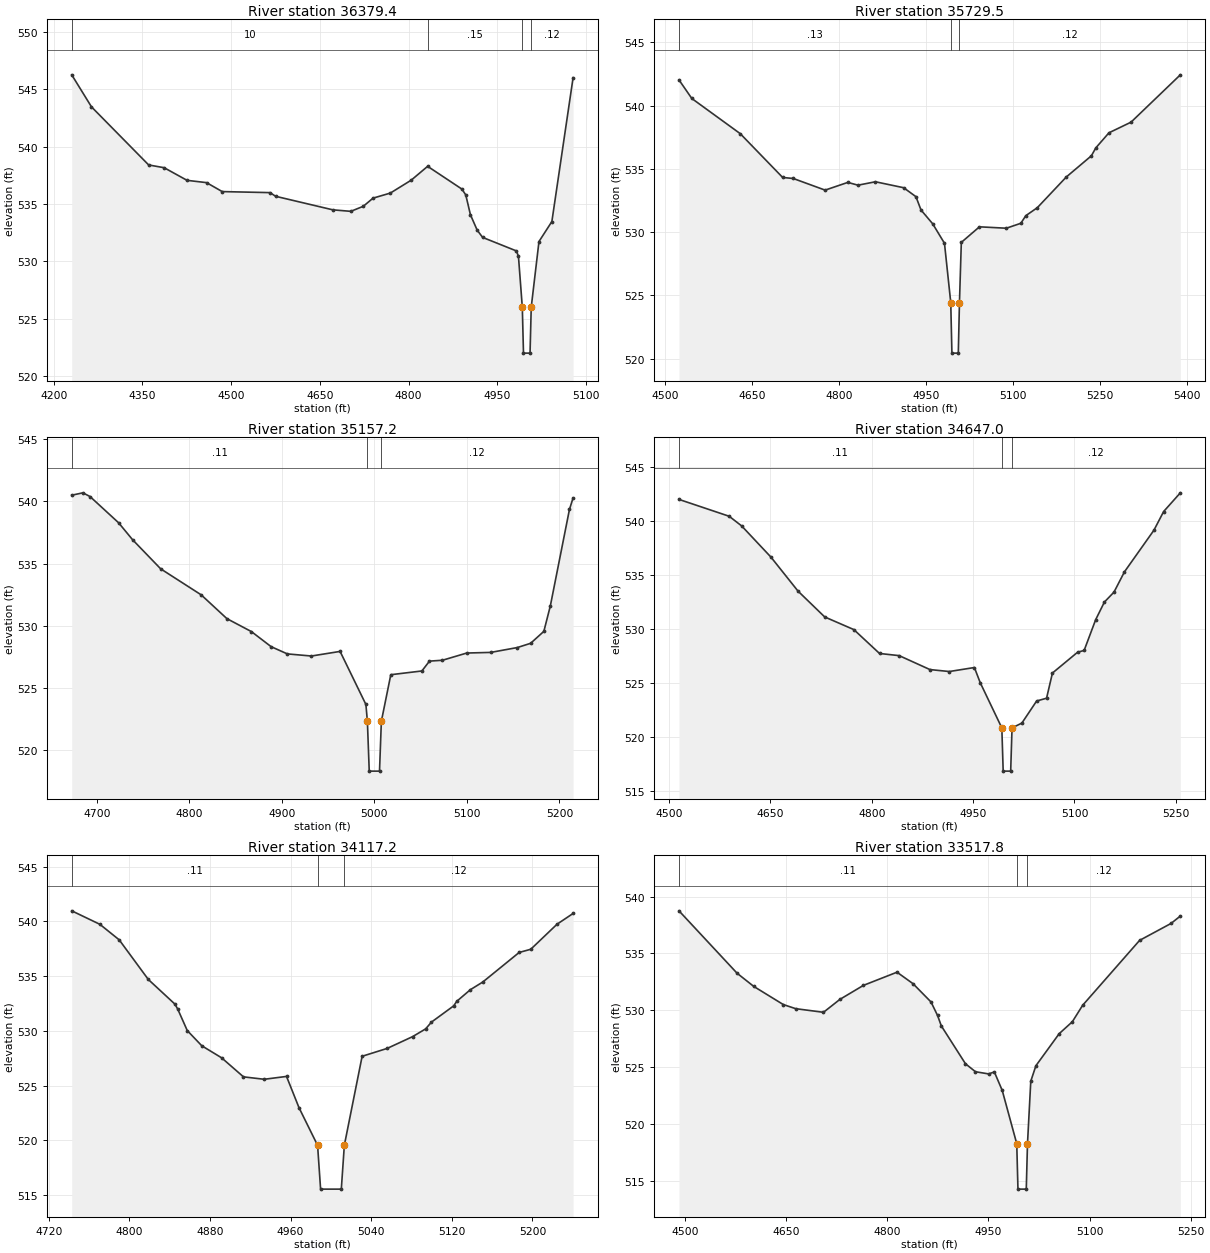
Type RM Length L Ch R = 1 ,36379.4,649.9,649.9,649.9
XS GIS Cut Line= 3
      1889185.15       759835.96      1889670.27       759230.99
      1889708.07       759169.19
BEGIN DESCRIPTION:
South Fork 58.0
END DESCRIPTION:
#Sta/Elev= 30
  4230.4  546.25  4263.8  543.46  4360.5   538.4  4386.7  538.16  4425.4  537.06
  4458.4  536.86  4484.9  536.08  4565.8  535.99  4575.2  535.67    4672  534.49
  4702.4  534.36  4723.5   534.8    4740  535.51  4769.2  535.95  4804.4  537.07
  4832.3  538.28  4890.2   536.3  4896.8  535.79  4904.7  534.06  4916.1  532.72
  4925.3  532.09  4982.5  530.91  4985.9  530.43  4992.4  526.01  4994.4  522.01
  5005.5  522.01  5007.5  526.01  5020.6  531.73  5042.4  533.47  5078.3     546
#Mann= 4 , 1 , 0
 4230.40      10       0  4832.3    0.15       0  4992.4    0.05       0
  5007.5    0.12       0
Bank Sta=4992.40,5007.50
Exp/Cntr=0.3,0.1

Type RM Length L Ch R = 1 ,35729.5,572.3,572.3,572.3
XS GIS Cut Line= 3
      1889731.22       760078.28      1890029.65       759704.08
      1890272.57       759405.95
BEGIN DESCRIPTION:
South Fork 57.0
END DESCRIPTION:
#Sta/Elev= 30
  4524.6  542.03  4546.7  540.56  4630.1  537.78  4703.1  534.32  4721.3  534.24
  4776.2  533.32  4815.3  533.93  4832.8  533.71  4862.8  533.98  4911.4  533.51
  4932.6   532.8  4941.3  531.75  4961.4  530.66  4981.7  529.12  4992.5  524.44
  4994.5  520.44  5005.5  520.44  5007.5  524.44  5010.7  529.19  5041.9  530.42
  5088.2  530.31  5113.2   530.7  5121.7   531.3  5141.5  531.93  5191.5  534.36
  5234.6  536.03  5242.3  536.66  5264.9  537.85  5302.9  538.69  5387.8  542.43
#Mann= 3 , 1 , 0
 4524.60    0.13       0  4992.5    0.05       0  5007.5    0.12       0
Bank Sta=4992.50,5007.50
Exp/Cntr=0.3,0.1

Type RM Length L Ch R = 1 ,35157.2,510.2,510.2,510.2
XS GIS Cut Line= 3
      1890521.84       760021.53      1890510.55       759698.88
      1890510.89       759479.97
BEGIN DESCRIPTION:
South Fork 56.0
END DESCRIPTION:
#Sta/Elev= 30
  4672.9  540.49    4685  540.68  4692.7  540.38  4723.5  538.28  4738.6  536.92
    4769  534.58  4812.8  532.49  4840.6  530.58  4867.1  529.54  4888.4  528.33
  4905.9  527.75  4931.9  527.58  4962.9  527.95  4990.8  523.69  4992.4  522.34
  4994.4  518.34  5005.5  518.34  5007.5  522.34  5017.7  526.08  5051.3  526.38
  5059.5  527.17  5073.5  527.24  5099.8  527.82  5125.7  527.87  5154.4  528.26
  5168.8   528.6  5183.1  529.56  5190.1   531.6  5210.8  539.36  5214.7  540.27
#Mann= 3 , 1 , 0
 4672.90    0.11       0  4992.4    0.05       0  5007.5    0.12       0
Bank Sta=4992.40,5007.50
Exp/Cntr=0.3,0.1

Type RM Length L Ch R = 1 ,34647.0,529.8,529.8,529.8
XS GIS Cut Line= 4
      1890665.07       760123.10      1890895.10       759690.20
      1890906.00       759681.29      1891138.12       759629.84
BEGIN DESCRIPTION:
South Fork 55.0
END DESCRIPTION:
#Sta/Elev= 30
  4514.7  541.96    4589   540.4  4607.4  539.51  4650.8  536.62  4690.9  533.47
  4730.4  531.08  4773.5  529.91  4811.5   527.7  4840.6   527.5  4886.1  526.21
  4914.8  526.03  4951.9   526.4  4960.5     525  4992.5  520.81  4994.5  516.81
  5005.6  516.81  5007.6  520.81  5022.2  521.26    5044   523.3  5058.7  523.56
  5067.4  525.89  5104.7  527.82  5114.3  527.98  5131.4  530.83  5144.3  532.46
  5158.5  533.38    5174  535.26  5217.6  539.11    5232  540.84  5256.7  542.57
#Mann= 3 , 1 , 0
 4514.70    0.11       0  4992.5    0.05       0  5007.6    0.12       0
Bank Sta=4992.50,5007.60
Exp/Cntr=0.3,0.1

Type RM Length L Ch R = 1 ,34117.2,599.4,599.4,599.4
XS GIS Cut Line= 3
      1890940.11       760290.29      1891147.70       760126.83
      1891346.72       760005.33
BEGIN DESCRIPTION:
South Fork 54.0
END DESCRIPTION:
#Sta/Elev= 30
  4742.9  540.96  4770.8  539.73    4790  538.31  4818.9  534.69  4845.3  532.44
  4848.1  531.98  4857.5  530.03  4871.9  528.64  4891.6  527.54  4913.3   525.8
  4933.9  525.58    4956  525.84  4968.4  522.98  4986.8  519.55  4989.8  515.55
 5010.35  515.55 5013.35  519.55    5031  527.68  5055.9   528.4    5081  529.47
    5094  530.18  5099.8   530.8  5121.8  532.28  5124.9   532.7  5138.4  533.76
  5150.7  534.46  5186.8  537.16  5198.3  537.45  5224.4  539.74  5240.3  540.72
#Mann= 3 , 1 , 0
 4742.90    0.11       0  4986.8    0.05       0 5013.35    0.12       0
Bank Sta=4986.80,5013.35
Exp/Cntr=0.3,0.1

Type RM Length L Ch R = 1 ,33517.8,354.4,354.4,354.4
XS GIS Cut Line= 3
      1891008.25       760810.86      1891471.49       760588.63
      1891691.41       760523.33
BEGIN DESCRIPTION:
South Fork 53.0
END DESCRIPTION:
#Sta/Elev= 30
  4491.4  538.75  4577.5  533.26  4602.2   532.1  4646.1   530.5  4664.4  530.14
  4705.6  529.82    4730  530.96  4764.8  532.19  4814.6  533.35  4838.3  532.34
    4865  530.73  4874.7  529.54  4880.3  528.62  4916.1  525.29  4930.9  524.59
  4950.3   524.4  4958.9  524.57  4970.6  522.94 4992.08  518.26 4993.88  514.26
 5006.21  514.26 5008.01  518.26  5012.9  523.76  5020.5  525.12    5055  527.94
  5074.5  528.99  5089.8  530.44  5174.2  536.15  5220.8  537.64  5234.6  538.29
#Mann= 3 , 1 , 0
 4491.40    0.11       0 4992.08    0.05       0 5008.01    0.12       0
Bank Sta=4992.08,5008.01
Exp/Cntr=0.3,0.1

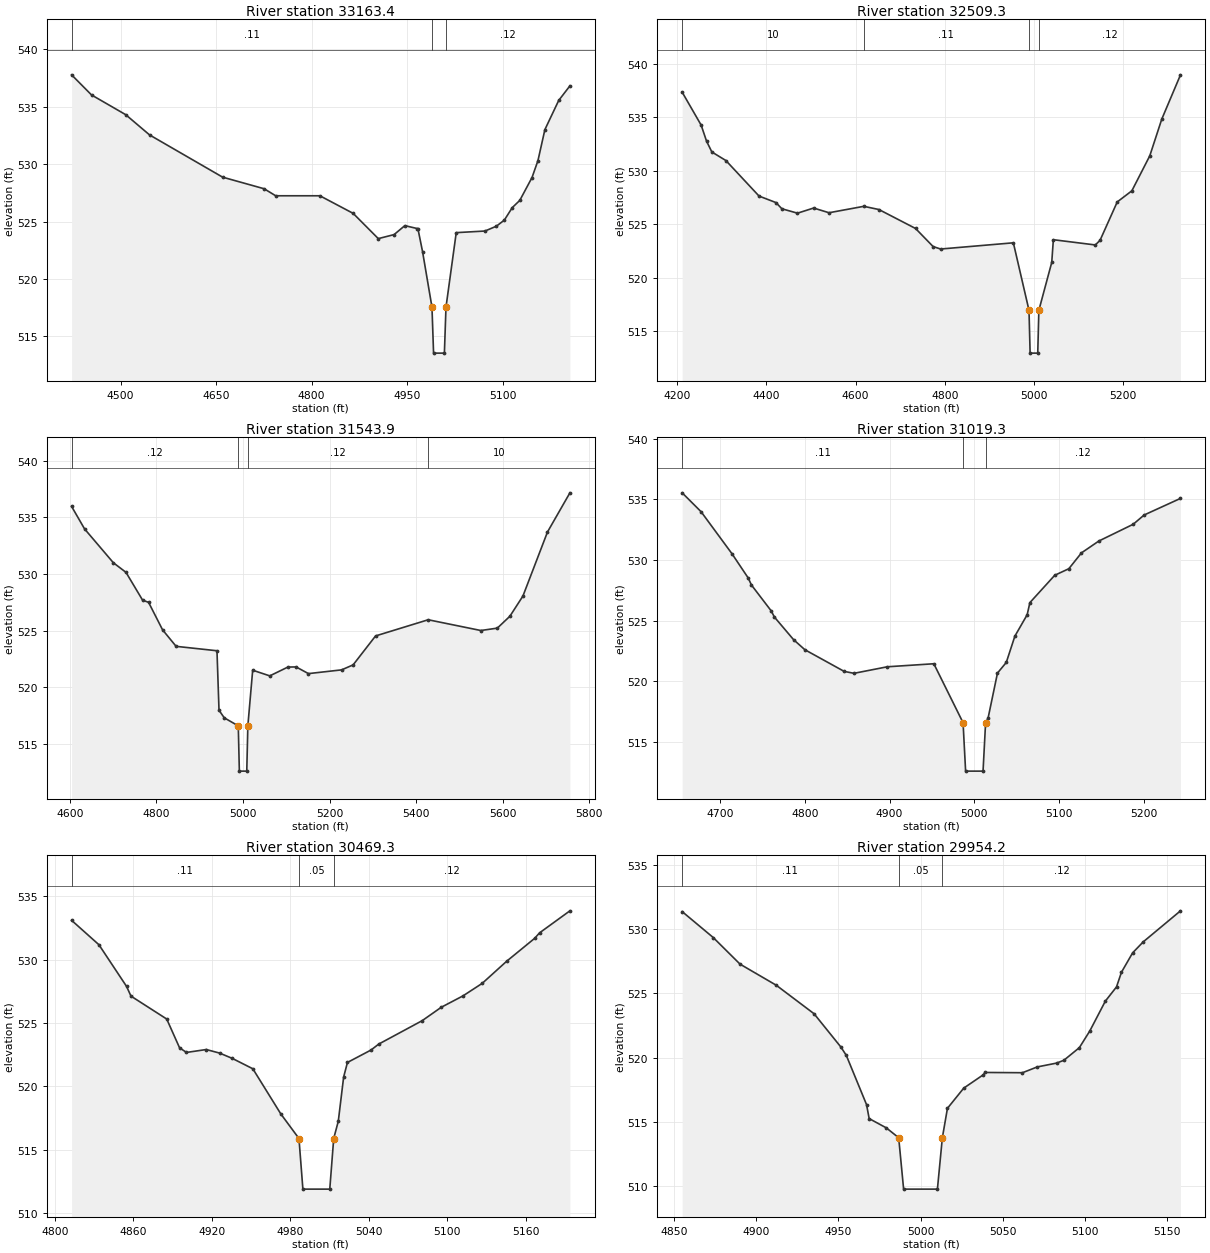
Type RM Length L Ch R = 1 ,33163.4,654.1,654.1,654.1
XS GIS Cut Line= 4
      1891154.44       761091.63      1891436.00       761025.05
      1891672.01       760872.49      1891847.24       760752.90
BEGIN DESCRIPTION:
South Fork 52.0
END DESCRIPTION:
#Sta/Elev= 30
  4423.1  537.78  4454.4  536.03  4508.1  534.31  4545.5  532.55  4660.3  528.87
  4725.5  527.86  4743.6  527.25    4813  527.25  4865.2  525.72  4904.7  523.52
  4929.5  523.87  4946.4  524.65  4965.6   524.4  4967.1  524.34  4974.2  522.39
    4989  517.55  4991.5  513.55  5008.5  513.55    5011  517.55  5027.1  524.04
  5072.2  524.18  5090.1   524.6  5102.6  525.13  5115.1  526.22  5126.9  526.85
  5146.1  528.84  5155.4  530.31  5166.3  533.01    5188  535.55  5205.6  536.82
#Mann= 3 , 1 , 0
 4423.10    0.11       0    4989    0.05       0    5011    0.12       0
Bank Sta=4989.00,5011.00
Exp/Cntr=0.3,0.1

Type RM Length L Ch R = 1 ,32509.3,965.4,965.4,965.4
XS GIS Cut Line= 3
      1891301.50       761425.72      1892086.94       761308.25
      1892290.48       761056.64
BEGIN DESCRIPTION:
South Fork 51.0
END DESCRIPTION:
#Sta/Elev= 30
  4210.9  537.34  4253.5  534.26  4265.6  532.76  4277.5  531.75    4309  530.95
  4383.3  527.63  4421.3  527.02  4434.6  526.44  4469.6  526.03  4505.8  526.51
  4540.3  526.07  4618.3  526.67  4652.3  526.37  4734.4   524.6  4773.8  522.91
  4790.6  522.68  4953.8  523.26 4988.88  516.95 4991.38  512.95  5008.5  512.95
    5011  516.95  5039.9  521.43  5043.5  523.55  5137.6  523.06  5148.2  523.49
  5186.8  527.08  5219.6  528.12  5259.8  531.39  5286.7  534.82  5328.7  538.96
#Mann= 4 , 1 , 0
 4210.90      10       0  4618.3    0.11       0 4988.88    0.05       0
    5011    0.12       0
Bank Sta=4988.88,5011.00
Exp/Cntr=0.3,0.1

Type RM Length L Ch R = 1 ,31543.9,524.6,524.6,524.6
XS GIS Cut Line= 5
      1891421.74       761675.17      1891498.12       761738.55
      1891789.20       761742.28      1892138.74       761741.15
      1892430.85       762030.83
BEGIN DESCRIPTION:
South Fork 50.0
END DESCRIPTION:
#Sta/Elev= 30
  4603.9  535.97  4633.9  533.98  4700.4  530.99  4729.6  530.14    4768  527.68
  4781.8  527.49  4814.1  525.06  4845.4   523.6  4939.8  523.21  4944.5  517.95
  4956.7  517.28    4989  516.57  4991.5  512.57 5008.63  512.57 5011.13  516.57
  5022.3  521.49  5061.8  520.99  5103.7  521.77  5122.6  521.78  5151.1  521.19
  5227.7  521.52  5254.3  521.96  5306.2  524.52  5427.8  525.95  5549.4     525
  5587.5  525.21  5616.5  526.26  5646.7  528.05  5703.4  533.71  5755.2  537.17
#Mann= 4 , 1 , 0
 4603.90    0.12       0    4989    0.05       0 5011.13    0.12       0
  5427.8      10       0
Bank Sta=4989.00,5011.13
Exp/Cntr=0.3,0.1

Type RM Length L Ch R = 1 ,31019.3,550,550,550
XS GIS Cut Line= 3
      1891792.30       762301.61      1892102.56       762133.77
      1892333.15       762090.84
BEGIN DESCRIPTION:
South Fork 49.0
END DESCRIPTION:
#Sta/Elev= 30
  4655.6  535.55  4677.9  533.99  4714.3  530.52  4733.3  528.53  4737.3  527.93
  4760.3  525.82  4764.4  525.28  4786.9  523.42  4800.2  522.59  4846.5   520.8
  4858.1  520.64  4897.4  521.18  4952.2  521.43 4986.65  516.56 4989.65  512.56
  5010.2  512.56  5013.2  516.56  5016.1  516.93  5027.2  520.66  5037.6  521.54
  5047.7  523.71  5062.2  525.48  5065.4  526.48  5094.7  528.74  5111.3  529.28
  5126.2  530.59  5146.7  531.57  5187.1  532.95  5200.1  533.72  5242.9  535.09
#Mann= 3 , 1 , 0
 4655.60    0.11       0 4986.65    0.05       0  5013.2    0.12       0
Bank Sta=4986.65,5013.20
Exp/Cntr=0.3,0.1

Type RM Length L Ch R = 1 ,30469.3,515.1,515.1,515.1
XS GIS Cut Line= 3
      1891929.32       762601.89      1892110.10       762652.61
      1892297.02       762700.82
BEGIN DESCRIPTION:
South Fork 48.0
END DESCRIPTION:
#Sta/Elev= 29
  4812.9  533.11  4833.8  531.18  4854.9  527.89  4858.3  527.12  4885.6  525.31
  4895.4  523.04  4900.7  522.67  4915.8   522.9    4926  522.62  4935.7   522.2
  4951.4  521.38  4972.8  517.81 4986.65  515.87 4989.65  511.87  5010.2  511.87
  5013.2  515.87  5016.7  517.23  5020.8  520.73  5023.7  521.88  5041.7  522.86
  5047.6  523.33  5080.8  525.18  5095.4  526.24    5112  527.14  5126.7  528.13
  5145.4  529.88  5166.8  531.69  5170.5  532.12  5193.7  533.86
#Mann= 3 , 1 , 0
 4812.90    0.11       0 4986.65    0.05       0  5013.2    0.12       0
Bank Sta=4986.65,5013.20
Exp/Cntr=0.3,0.1

Type RM Length L Ch R = 1 ,29954.2,674.7,674.7,674.7
XS GIS Cut Line= 4
      1891731.76       762984.11      1891733.26       762987.46
      1891837.62       763082.75      1891945.24       763198.44
BEGIN DESCRIPTION:
South Fork 47.0
END DESCRIPTION:
#Sta/Elev= 30
    4855  531.36  4873.9  529.34  4890.2  527.27  4912.2  525.63  4935.2  523.41
  4951.5  520.82  4954.8  520.17  4967.1  516.34  4968.7  515.25  4979.1  514.53
 4986.65  513.76 4989.65  509.76  5010.2  509.76  5013.2  513.76  5016.3  516.05
  5026.2  517.62  5038.1  518.66  5039.1  518.84  5061.9  518.82  5070.9  519.27
  5082.7  519.57  5087.1  519.79  5096.5  520.77  5102.9  522.08  5112.3  524.39
  5119.1   525.5  5122.1  526.64  5128.9  528.15  5135.3     529    5158  531.42
#Mann= 3 , 1 , 0
 4855.00    0.11       0 4986.65    0.05       0  5013.2    0.12       0
Bank Sta=4986.65,5013.20
Exp/Cntr=0.3,0.1