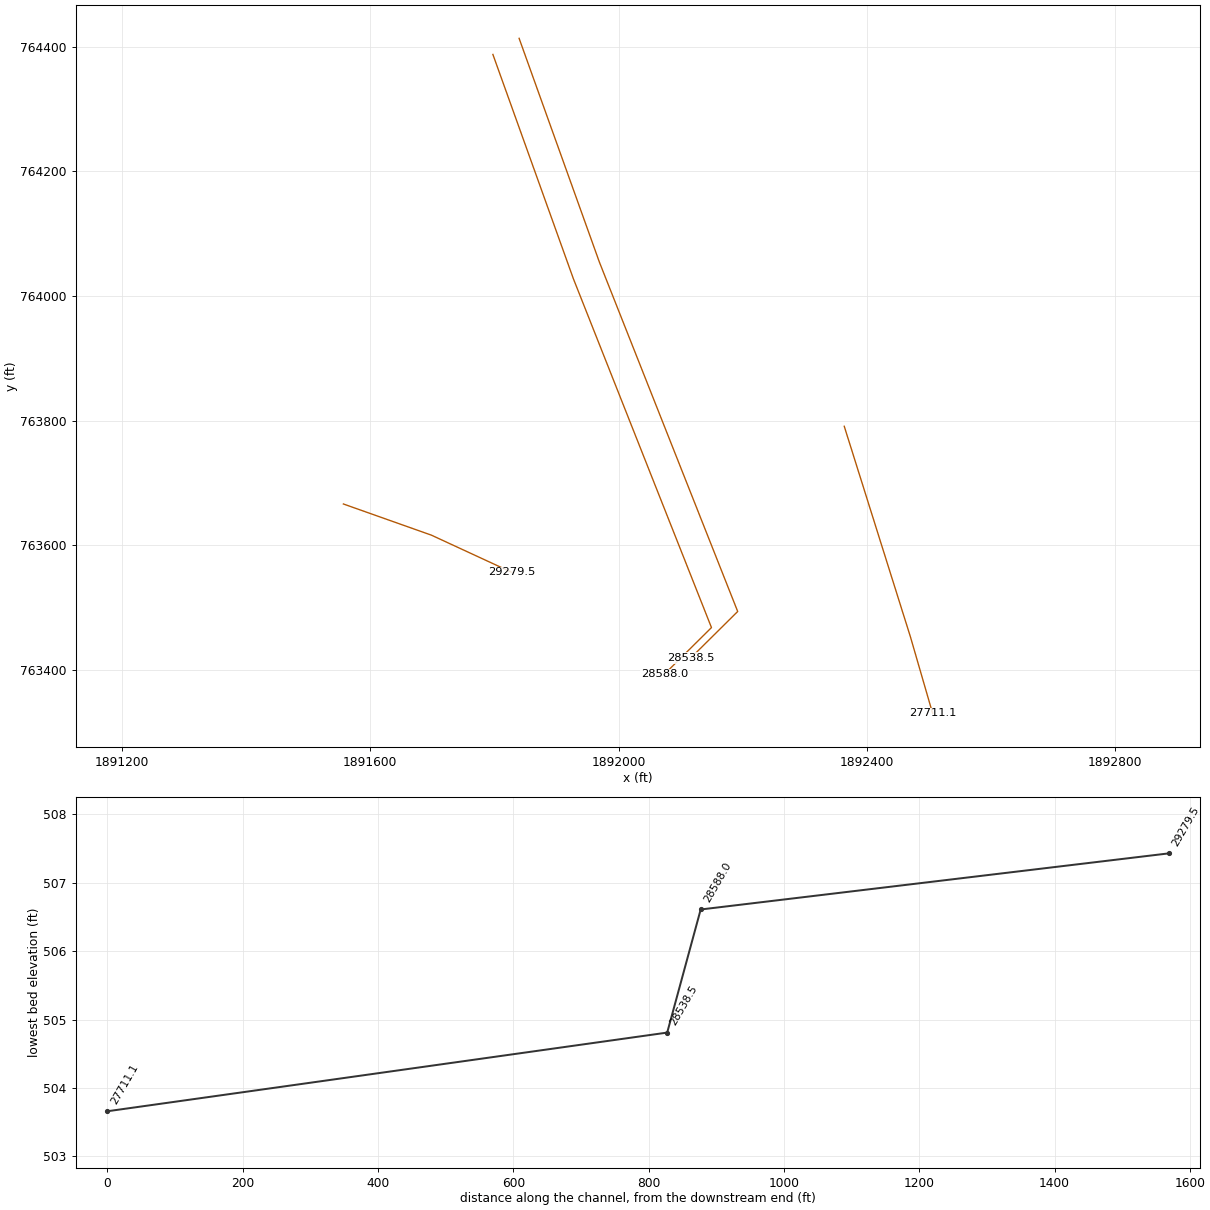
HEC-RAS study SOUTH FORK.PRJ: South Fork

--- SOUTH FORK.g01 (geometry) --- (continued)

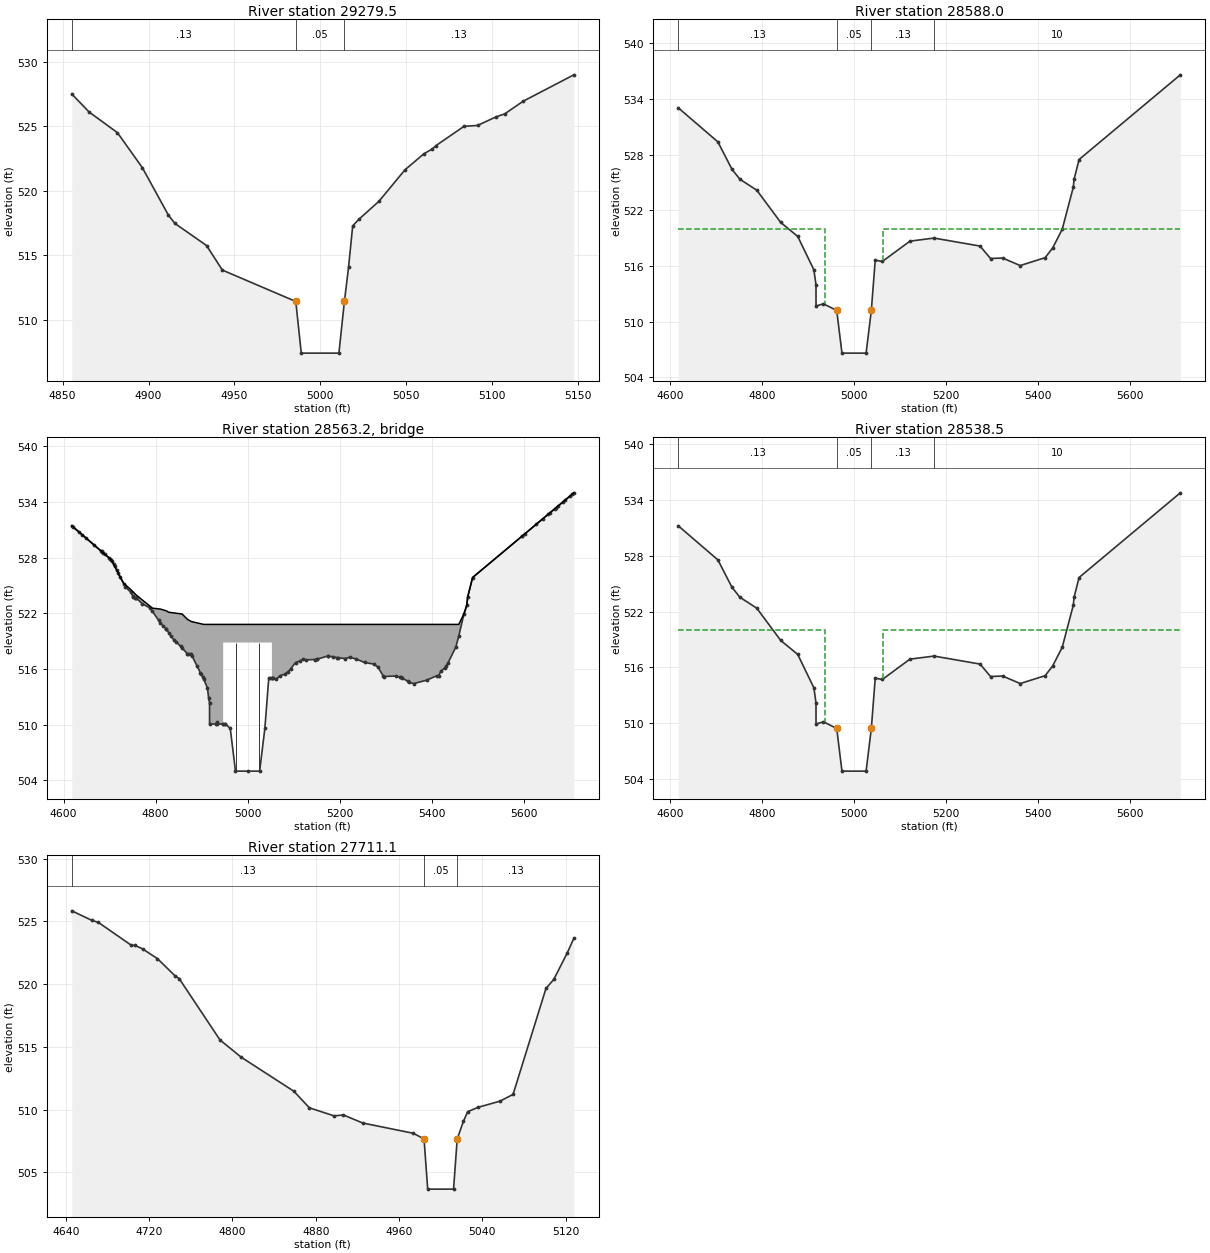
Type RM Length L Ch R = 1 ,29279.5,691.55,691.55,691.55
XS GIS Cut Line= 3
      1891556.77       763666.22      1891698.64       763616.15
      1891827.56       763556.75
BEGIN DESCRIPTION:
South Fork 46.0
END DESCRIPTION:
#Sta/Elev= 26
  4855.3   527.5  4865.4   526.1  4881.9   524.5  4896.4  521.79  4911.6  518.11
  4915.4  517.47  4933.8  515.76    4943  513.86 4985.76  511.43 4988.96  507.43
 5010.88  507.43 5014.08  511.43  5016.5  514.08  5018.9  517.28  5022.4  517.78
  5034.2  519.19  5049.4  521.63  5060.4  522.87  5065.3  523.24  5067.3  523.49
  5083.7  524.99  5091.6  525.06  5102.5  525.73  5107.5  525.96  5118.1  526.93
  5147.7  528.98
#Mann= 3 , 1 , 0
 4855.30    0.13       0 4985.76    0.05       0 5014.08    0.13       0
Bank Sta=4985.76,5014.08
Exp/Cntr=0.5,0.3

Type RM Length L Ch R = 1 ,28588.0,49.5,49.5,49.5
XS GIS Cut Line= 4
      1891797.60       764387.85      1891927.08       764028.26
      1892149.74       763467.83      1892074.05       763393.10
BEGIN DESCRIPTION:
Upstream Section of Bridge/Culvert/Weir
END DESCRIPTION:
#Sta/Elev= 30
  4617.8  533.03    4704  529.36  4734.6  526.41    4752  525.33  4788.5  524.16
  4840.7  520.68  4877.6  519.18  4912.7  515.58  4917.3  513.98  4917.4  511.68
  4933.5  511.92 4962.38  511.21 4973.75  506.61 5026.25  506.61 5037.63  511.21
  5046.1  516.62  5061.5  516.48  5121.6  518.67  5173.9     519    5274  518.14
  5296.8   516.8  5323.1  516.85  5361.3  516.04  5415.5  516.89  5431.7  517.92
  5452.7  519.95  5476.7  524.47  5478.5  525.35  5489.3  527.46  5709.4  536.58
#Mann= 4 , 1 , 0
 4617.80    0.13       0 4962.38    0.05       0 5037.63    0.13       0
  5173.9      10       0
#XS Ineff= 2 , 0
       0    4936     520    5063       0     520
Bank Sta=4962.38,5037.63
Exp/Cntr=0.5,0.3

Type RM Length L Ch R = 3 ,28563.2,,,
BEGIN DESCRIPTION:
South Fork - Bethel South Fork Rd
Structure ID: NCF-0101
Approximate Survey Structure
END DESCRIPTION:
Bridge Culvert--1,0,-1,-1, 0
Deck Dist Width WeirC Skew NumUp NumDn MinLoCord MaxHiCord MaxSubmerge Is_Ogee
10,29.5,2.6,, 60, 60,,,0.95,0,1,1,,
  4617.8    4704  4722.5  4731.4  4734.6  4745.5    4752  4758.2  4770.4  4788.5
  4793.2  4810.6  4823.4  4828.5  4840.7  4857.7  4869.4  4877.6  4904.5  4912.7
  4915.3  4917.3  4917.4  4931.6  4933.5  4933.6 4946.91    4947 5052.89    5053
  5061.5  5071.6  5081.1  5088.3  5104.4  5121.6  5147.7  5173.9  5211.8  5222.7
  5254.3    5274  5283.1  5296.8  5323.1  5334.3  5351.7  5361.3  5389.3  5415.5
  5420.1  5429.4  5436.2  5452.7  5459.2  5470.5  5476.7  5478.5  5489.3  5709.4
  531.42  527.75  525.95  525.19  525.05  524.58  524.26  523.95  523.46  522.74
  522.55  522.45  522.26  522.11  522.03  521.92  521.34  521.11   520.8   520.8
   520.8   520.8   520.8   520.8   520.8   520.8   520.8   520.8   520.8   520.8
   520.8   520.8   520.8   520.8   520.8   520.8   520.8   520.8   520.8   520.8
   520.8   520.8   520.8   520.8   520.8   520.8   520.8   520.8   520.8   520.8
   520.8   520.8   520.8   520.8   520.8  521.94  522.86  523.74  525.85  534.97
  531.42  527.75  525.95   525.1   524.8  524.31  523.72  523.65  523.04  522.55
  522.21  520.98   520.3  519.91  519.07  518.26  517.62  517.57   514.9  513.97
  512.88  512.37  510.07  510.07  510.31  510.07  510.07  518.85  518.85  515.02
  514.87  515.29  515.44  515.71  516.69  517.06  517.02  517.39  517.12  517.26
   516.7  516.53  516.22  515.19  515.24  515.09  514.55  514.43  514.79  515.28
  515.74  516.14  516.69  518.34  519.54  521.94  522.86  523.74  525.85  534.97
  4617.8    4704  4722.5  4731.4  4734.6  4745.5    4752  4758.2  4770.4  4788.5
  4793.2  4810.6  4823.4  4828.5  4840.7  4857.7  4869.4  4877.6  4904.5  4912.7
  4915.3  4917.3  4917.4  4931.6  4933.5  4933.6 4946.91    4947 5052.89    5053
  5061.5  5071.6  5081.1  5088.3  5104.4  5121.6  5147.7  5173.9  5211.8  5222.7
  5254.3    5274  5283.1  5296.8  5323.1  5334.3  5351.7  5361.3  5389.3  5415.5
  5420.1  5429.4  5436.2  5452.7  5459.2  5470.5  5476.7  5478.5  5489.3  5709.4
  531.37  527.71  525.91  525.19  525.05  524.58  524.26  523.95  523.46  522.74
  522.55  522.45  522.26  522.11  522.03  521.92  521.34  521.11   520.8   520.8
   520.8   520.8   520.8   520.8   520.8   520.8   520.8   520.8   520.8   520.8
   520.8   520.8   520.8   520.8   520.8   520.8   520.8   520.8   520.8   520.8
   520.8   520.8   520.8   520.8   520.8   520.8   520.8   520.8   520.8   520.8
   520.8   520.8   520.8   520.8   520.8   521.9  522.82   523.7  525.81  534.92
  531.32  527.65  525.85     525   524.7  524.21  523.62  523.55  522.94  522.45
  522.11  520.88   520.2  519.81  518.97  518.16  517.52  517.47   514.8  513.87
  512.78  512.27  509.97  509.97  510.21  509.97  509.97  518.75  518.75  514.92
  514.77  515.19  515.34  515.61  516.59  516.96  516.92  517.29  517.02  517.16
   516.6  516.43  516.12  515.09  515.14  514.99  514.45  514.33  514.69  515.18
  515.64  516.04  516.59  518.24  519.44  521.84  522.76  523.64  525.75  534.87
Pier Skew, UpSta & Num, DnSta & Num=,4975.4, 2 ,4975.4, 2 , 0 , 0 , 0 ,,
       1       1
     504  519.85
       1       1
   503.9  519.75
Pier Skew, UpSta & Num, DnSta & Num=,5024.6, 2 ,5024.6, 2 , 0 , 0 , 0 ,,
       1       1
     504  519.85
       1       1
   503.9  519.75
Abutment Skew #Up #Dn=, 2 , 2
 4946.80 4950.80
  518.85  510.07
 4946.80 4950.80
  518.75  509.97
Abutment Skew #Up #Dn=, 2 , 2
 5049.30 5053.09
  515.02  518.85
 5049.30 5053.09
  514.92  518.75
BR Coef= 1 , 1 , 0 ,1.25, 0 ,,,0.8,0,2,0,
Wspro=,,,, 1 ,,,, 0 ,,,, 0 ,,,,-1 ,-1 ,-1 , 0 , 0 , 0 , 0 , 0
BC Design=,, 0 ,, 0 ,,,,,,
BR U #Sta/Elev= 133
  4617.8  531.42  4619.6  531.34  4633.6  530.75  4640.8  530.44    4649  530.09
  4666.5  529.34  4680.9  528.73  4682.6  528.66  4684.2  528.59  4685.7  528.52
  4689.3  528.37  4699.6  527.94  4701.6  527.85    4704  527.75  4705.5  527.63
  4709.4  527.26    4711  527.11    4716  526.64  4718.6  526.39  4722.5  525.95
  4731.4   525.1  4734.6   524.8  4745.5  524.31  4750.7  523.84    4752  523.72
  4754.7  523.69  4756.5  523.67  4758.2  523.65  4770.4  523.04  4788.5  522.55
  4793.2  522.21  4806.4  521.25  4810.6  520.98  4815.3  520.68  4823.4   520.3
  4823.7  520.28  4828.5  519.91    4833  519.57  4840.7  519.07  4844.1  518.94
  4854.2  518.45  4857.7  518.26  4869.4  517.62  4871.5  517.61  4874.5  517.59
  4877.6  517.57  4878.9  517.44  4890.3  516.31  4897.2  515.62  4899.2   515.5
  4902.5  515.13  4904.5   514.9  4912.7  513.97  4915.3  512.88  4917.3  512.37
  4917.4  510.07  4931.6  510.07  4933.5  510.31  4933.6  510.07 4946.91  510.07
    4947  510.07  4950.8  510.07    4952  510.07 4962.38   509.6 4973.75     505
    5000     505 5026.25     505 5037.63   509.6  5046.1  515.01  5049.3  515.02
 5052.89  515.02    5053  515.02  5055.7  515.03  5061.5  514.87  5071.6  515.29
  5081.1  515.44  5088.3  515.71    5094  516.03  5104.4  516.69  5114.3  516.86
  5121.6  517.06  5126.3  516.98  5147.7  517.02  5151.1  517.07  5151.8  517.06
  5173.9  517.39    5174  517.39  5185.6  517.32  5193.4  517.22  5195.6  517.23
  5211.8  517.12  5222.7  517.26  5236.7  517.06  5254.3   516.7    5274  516.53
  5283.1  516.22    5295  515.25  5296.8  515.19  5323.1  515.24  5332.1   515.1
  5334.3  515.09  5336.4  515.01  5348.8  514.67  5351.7  514.55  5361.3  514.43
  5389.3  514.79    5411  515.26  5415.5  515.28  5420.1  515.74  5429.4  516.14
  5431.7  516.31  5436.2  516.69  5452.7  518.34  5459.2  519.54  5470.5  521.94
  5476.7  522.86  5478.5  523.74  5489.3  525.85  5595.9  530.27  5597.2  530.32
    5603  530.56    5628   531.6  5642.4  532.19  5653.7  532.66  5658.2  532.85
  5667.5  533.23  5670.9  533.37    5675  533.54  5685.6  533.98  5690.2  534.17
  5701.1  534.63  5706.2  534.84  5709.4  534.97
BR U #Mann= 4
 4617.80    0.13 4962.38    0.05 5037.63    0.13  5173.9      10
BR U Banks=4962.38,5037.63
BR D #Sta/Elev= 133
  4617.8  531.32  4619.6  531.24  4633.6  530.65  4640.8  530.34    4649  529.99
  4666.5  529.24  4680.9  528.63  4682.6  528.56  4684.2  528.49  4685.7  528.42
  4689.3  528.27  4699.6  527.84  4701.6  527.75    4704  527.65  4705.5  527.53
  4709.4  527.16    4711  527.01    4716  526.54  4718.6  526.29  4722.5  525.85
  4731.4     525  4734.6   524.7  4745.5  524.21  4750.7  523.74    4752  523.62
  4754.7  523.59  4756.5  523.57  4758.2  523.55  4770.4  522.94  4788.5  522.45
  4793.2  522.11  4806.4  521.15  4810.6  520.88  4815.3  520.58  4823.4   520.2
  4823.7  520.18  4828.5  519.81    4833  519.47  4840.7  518.97  4844.1  518.84
  4854.2  518.35  4857.7  518.16  4869.4  517.52  4871.5  517.51  4874.5  517.49
  4877.6  517.47  4878.9  517.34  4890.3  516.21  4897.2  515.52  4899.2   515.4
  4902.5  515.03  4904.5   514.8  4912.7  513.87  4915.3  512.78  4917.3  512.27
  4917.4  509.97  4931.6  509.97  4933.5  510.21  4933.6  509.97 4946.91  509.97
    4947  509.97  4950.8  509.97    4952  509.97 4962.38   509.5 4973.75   504.9
    5000   504.9 5026.25   504.9 5037.63   509.5  5046.1  514.91  5049.3  514.92
 5052.89  514.92    5053  514.92  5055.7  514.93  5061.5  514.77  5071.6  515.19
  5081.1  515.34  5088.3  515.61    5094  515.93  5104.4  516.59  5114.3  516.76
  5121.6  516.96  5126.3  516.88  5147.7  516.92  5151.1  516.97  5151.8  516.96
  5173.9  517.29    5174  517.29  5185.6  517.22  5193.4  517.12  5195.6  517.13
  5211.8  517.02  5222.7  517.16  5236.7  516.96  5254.3   516.6    5274  516.43
  5283.1  516.12    5295  515.15  5296.8  515.09  5323.1  515.14  5332.1     515
  5334.3  514.99  5336.4  514.91  5348.8  514.57  5351.7  514.45  5361.3  514.33
  5389.3  514.69    5411  515.16  5415.5  515.18  5420.1  515.64  5429.4  516.04
  5431.7  516.21  5436.2  516.59  5452.7  518.24  5459.2  519.44  5470.5  521.84
  5476.7  522.76  5478.5  523.64  5489.3  525.75  5595.9  530.17  5597.2  530.22
    5603  530.46    5628   531.5  5642.4  532.09  5653.7  532.56  5658.2  532.75
  5667.5  533.13  5670.9  533.27    5675  533.44  5685.6  533.88  5690.2  534.07
  5701.1  534.53  5706.2  534.74  5709.4  534.87
BR D #Mann= 4
 4617.80    0.13 4962.38    0.05 5037.63    0.13  5173.9      10
BR D Banks=4962.38,5037.63

Type RM Length L Ch R = 1 ,28538.5,827.35,827.35,827.35
XS GIS Cut Line= 4
      1891839.84       764413.67      1891969.32       764054.08
      1892191.98       763493.65      1892116.29       763418.91
BEGIN DESCRIPTION:
Downstream Section of Bridge/Culvert/Weir
END DESCRIPTION:
#Sta/Elev= 30
  4617.8  531.23    4704  527.56  4734.6  524.61    4752  523.53  4788.5  522.36
  4840.7  518.88  4877.6  517.38  4912.7  513.78  4917.3  512.18  4917.4  509.88
  4933.5  510.12 4962.38  509.41 4973.75  504.81 5026.25  504.81 5037.63  509.41
  5046.1  514.82  5061.5  514.68  5121.6  516.87  5173.9   517.2    5274  516.34
  5296.8     515  5323.1  515.05  5361.3  514.24  5415.5  515.09  5431.7  516.12
  5452.7  518.15  5476.7  522.67  5478.5  523.55  5489.3  525.66  5709.4  534.78
#Mann= 4 , 1 , 0
 4617.80    0.13       0 4962.38    0.05       0 5037.63    0.13       0
  5173.9      10       0
#XS Ineff= 2 , 0
       0    4936     520    5063       0     520
Bank Sta=4962.38,5037.63
Exp/Cntr=0.5,0.3

Type RM Length L Ch R = 1 ,27711.1,804.5,804.5,804.5
XS GIS Cut Line= 3
      1892363.63       763790.98      1892470.25       763453.00
      1892506.02       763330.10
BEGIN DESCRIPTION:
South Fork 45.0
END DESCRIPTION:
#Sta/Elev= 30
  4645.6  525.84  4664.9  525.08  4671.1  524.92  4702.9  523.09  4706.4  523.08
  4713.6  522.81  4727.9  522.03  4744.7  520.67  4748.8  520.44    4788  515.55
  4808.3  514.18    4859  511.46  4873.9  510.14  4897.6   509.5  4906.6  509.57
  4925.1  508.93  4973.8  508.11 4984.08  507.66 4987.58  503.66 5012.43  503.66
 5015.93  507.66  5021.9  509.06    5026  509.83    5036  510.18    5057  510.67
  5069.6  511.21  5101.2  519.65  5108.7  520.37  5121.6  522.47    5128  523.65
#Mann= 3 , 1 , 0
 4645.60    0.13       0 4984.08    0.05       0 5015.93    0.13       0
Bank Sta=4984.08,5015.93
Exp/Cntr=0.3,0.1