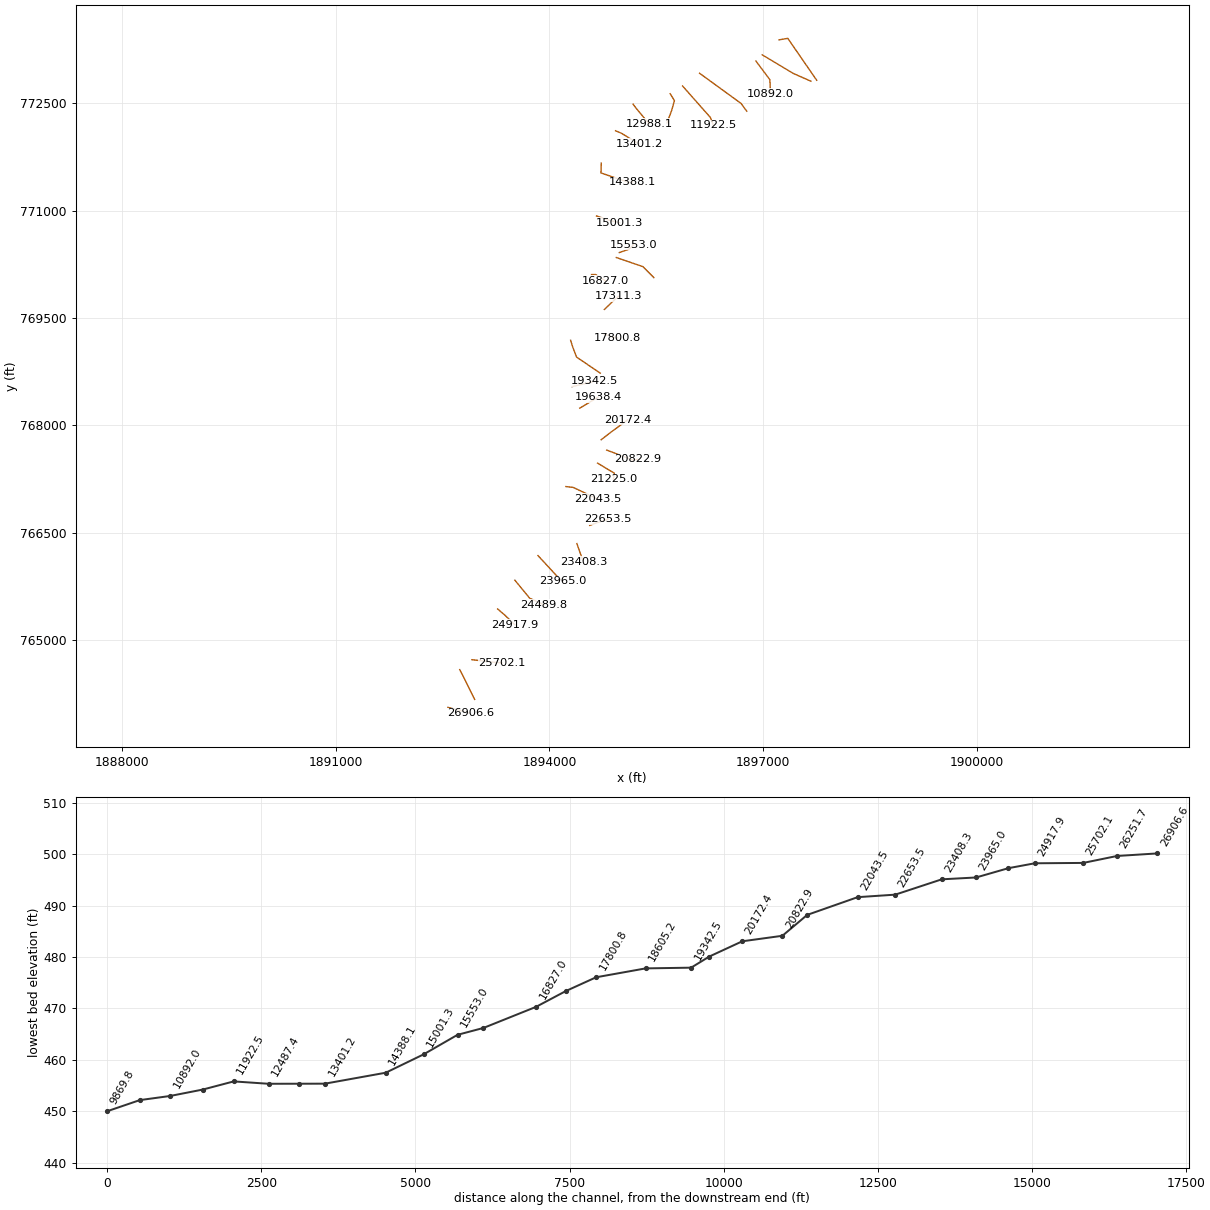
HEC-RAS study SOUTH FORK.PRJ: South Fork

--- SOUTH FORK.g01 (geometry) --- (continued)

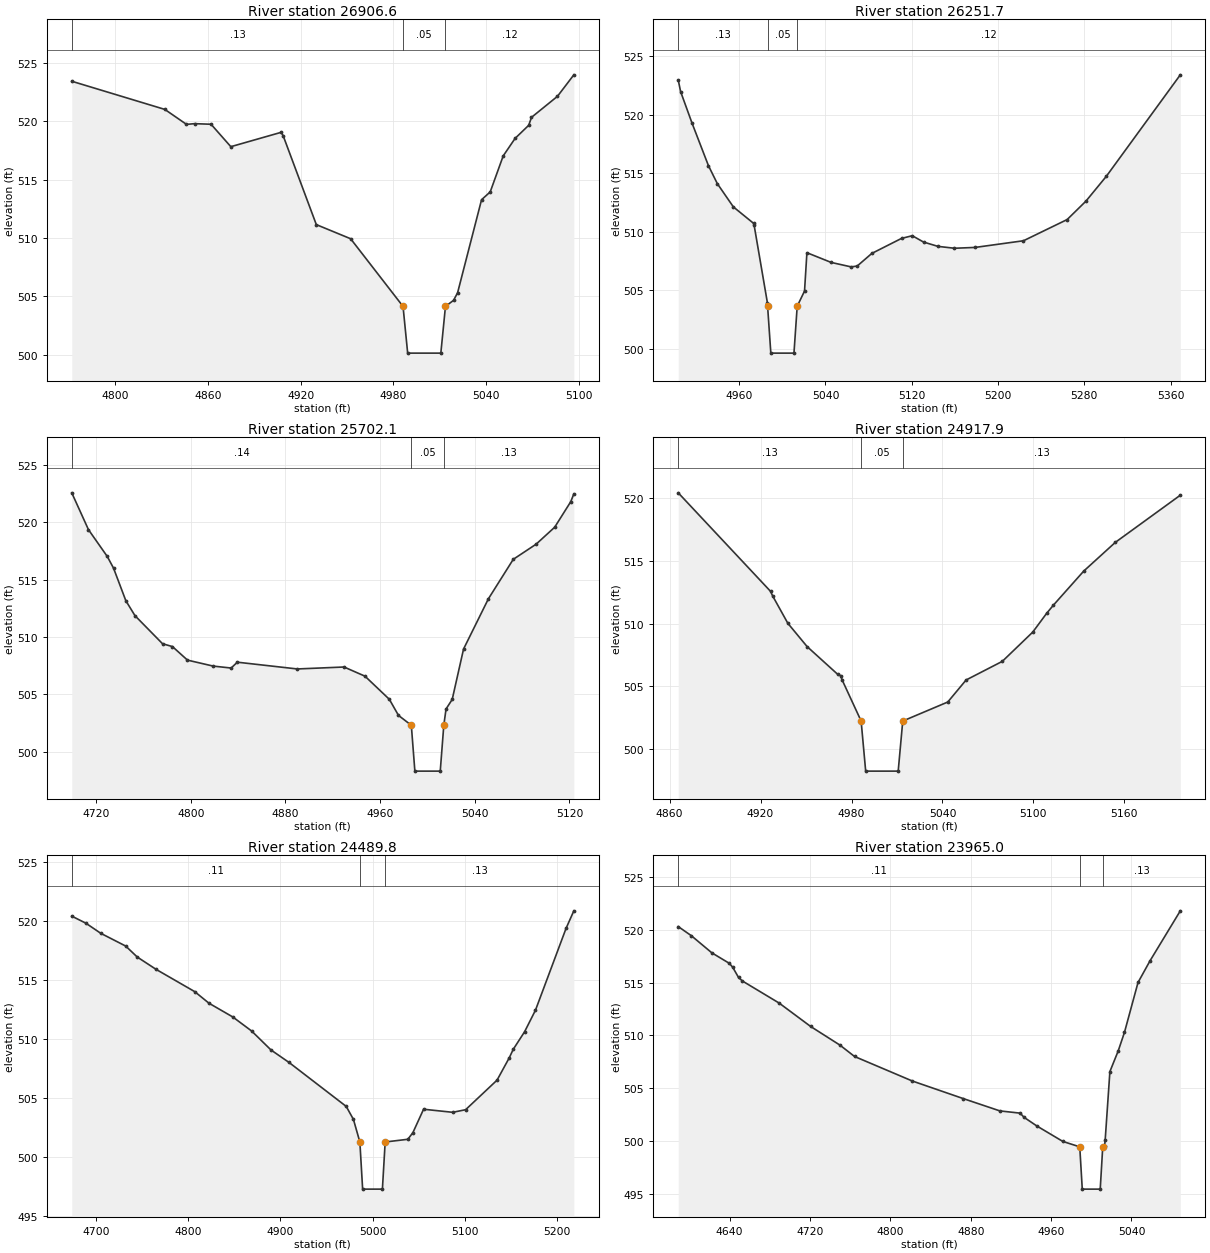
Type RM Length L Ch R = 1 ,26906.6,654.9,654.9,654.9
XS GIS Cut Line= 3
      1892573.96       764063.14      1892792.67       764004.93
      1892887.58       763978.68
BEGIN DESCRIPTION:
South Fork 44.0
END DESCRIPTION:
#Sta/Elev= 24
  4771.9  523.41  4832.1     521  4846.1  519.72  4851.4  519.78    4862  519.73
  4874.8  517.81  4907.4  519.04  4908.7  518.73  4930.1  511.14  4952.3  509.93
  4986.2  504.14  4989.2  500.14 5010.65  500.14 5013.65  504.14  5018.9  504.66
  5021.5  505.31    5037  513.27  5042.6  513.94    5051  517.02  5058.7  518.52
  5067.5  519.64  5069.3  520.32  5086.1  522.12  5096.7  523.96
#Mann= 3 , 1 , 0
 4771.90    0.13       0  4986.2    0.05       0 5013.65    0.12       0
Bank Sta=4986.20,5013.65
Exp/Cntr=0.3,0.1

Type RM Length L Ch R = 1 ,26251.7,549.6,549.6,549.6
XS GIS Cut Line= 3
      1892740.14       764589.50      1892785.25       764504.18
      1892949.54       764173.78
BEGIN DESCRIPTION:
South Fork 43.0
END DESCRIPTION:
#Sta/Elev= 30
  4903.5  522.95  4905.7  521.96  4916.2  519.29  4931.5  515.64  4939.7  514.11
  4954.6  512.12  4973.3  510.72  4973.8  510.59  4986.2  503.92 4986.35  503.64
 4989.35  499.64  5010.8  499.64  5013.8  503.64  5020.6  504.94  5022.8  508.21
  5045.3  507.38  5063.8     507  5069.4  507.07    5083  508.15  5110.5  509.43
  5120.5  509.66  5130.9  509.12  5144.3  508.75  5159.6  508.59  5178.7  508.66
  5223.6  509.23  5264.1  511.04  5281.5  512.61  5300.5  514.74    5369  523.39
#Mann= 3 , 1 , 0
 4903.50    0.13       0 4986.35    0.05       0  5013.8    0.12       0
Bank Sta=4986.35,5013.80
Exp/Cntr=0.3,0.1

Type RM Length L Ch R = 1 ,25702.1,784.2,784.2,784.2
XS GIS Cut Line= 3
      1892911.71       764728.22      1893210.38       764694.19
      1893333.64       764683.76
BEGIN DESCRIPTION:
South Fork 42.0
END DESCRIPTION:
#Sta/Elev= 30
  4699.4  522.56  4713.5  519.35  4729.4  517.01  4734.7  515.99  4745.1  513.15
  4752.8  511.85  4776.1   509.4  4784.5  509.15  4797.2  507.97  4818.9  507.45
  4834.1  507.28  4839.3  507.79    4890   507.2  4929.5  507.37  4947.2  506.57
  4967.8  504.55  4975.5  503.15 4986.35  502.29 4989.35  498.29  5010.8  498.29
  5013.8  502.29  5015.7  503.71  5020.9  504.54  5030.5  508.94  5051.5  513.32
  5072.5  516.76  5091.8  518.08  5107.5  519.56  5121.1  521.79  5123.7  522.47
#Mann= 3 , 1 , 0
 4699.40    0.14       0 4986.35    0.05       0  5013.8    0.13       0
Bank Sta=4986.35,5013.80
Exp/Cntr=0.3,0.1

Type RM Length L Ch R = 1 ,24917.9,428.1,428.1,428.1
XS GIS Cut Line= 3
      1893272.45       765436.89      1893374.75       765349.88
      1893516.71       765213.44
BEGIN DESCRIPTION:
South Fork 41.0
END DESCRIPTION:
#Sta/Elev= 21
  4865.7  520.45  4926.6  512.58    4928  512.21    4938  510.03  4950.7  508.17
    4971  505.94  4972.8  505.85  4973.8  505.51 4986.35  502.22 4989.35  498.22
  5010.8  498.22  5013.8  502.22  5043.5  503.74  5055.6   505.5  5079.5  506.99
  5099.6  509.33  5108.7  510.82  5113.2  511.48  5133.2   514.2    5154  516.49
  5196.9  520.26
#Mann= 3 , 1 , 0
 4865.70    0.13       0 4986.35    0.05       0  5013.8    0.13       0
Bank Sta=4986.35,5013.80
Exp/Cntr=0.3,0.1

Type RM Length L Ch R = 1 ,24489.8,524.8,524.8,524.8
XS GIS Cut Line= 3
      1893514.12       765839.15      1893722.00       765587.62
      1893920.49       765496.78
BEGIN DESCRIPTION:
South Fork 40.0
END DESCRIPTION:
#Sta/Elev= 30
  4673.7  520.44    4689  519.84  4705.2  518.98  4732.2   517.9  4744.7  516.97
  4765.2  515.92  4807.1  514.03  4822.5  513.05  4848.4  511.88  4868.8  510.69
  4889.8  509.08  4909.4  508.02  4971.4  504.29  4979.2  503.19  4986.2  501.27
  4989.2  497.27 5010.65  497.27 5013.65  501.27  5038.2   501.5  5043.7  502.06
  5055.3  504.05  5086.9  503.79  5100.9  504.01    5135  506.52  5148.2  508.41
  5152.6  509.14  5164.9  510.63  5176.7  512.46  5209.9  519.41  5218.3  520.89
#Mann= 3 , 1 , 0
 4673.70    0.11       0  4986.2    0.05       0 5013.65    0.13       0
Bank Sta=4986.20,5013.65
Exp/Cntr=0.3,0.1

Type RM Length L Ch R = 1 ,23965.0,556.7,556.7,556.7
XS GIS Cut Line= 3
      1893838.61       766182.51      1894118.75       765881.50
      1894186.14       765823.98
BEGIN DESCRIPTION:
South Fork 39.0
END DESCRIPTION:
#Sta/Elev= 30
  4588.8   520.3  4601.8  519.44  4622.2  517.82  4639.7  516.82  4643.1  516.44
  4648.8  515.49  4652.7  515.15  4689.3  513.06  4720.6  510.85  4749.7  509.09
  4764.3  508.01  4821.8  505.69  4872.7  504.02    4909  502.86  4929.1  502.65
  4933.1  502.25  4945.7  501.44  4971.7  499.97  4988.5  499.46    4991  495.46
 5008.88  495.46 5011.38  499.46  5013.2  499.57  5013.8  500.09  5018.5  506.58
  5026.8  508.54    5033  510.29  5046.5  515.01  5058.5  517.07  5088.6  521.79
#Mann= 3 , 1 , 0
 4588.80    0.11       0  4988.5    0.05       0 5011.38    0.13       0
Bank Sta=4988.50,5011.38
Exp/Cntr=0.3,0.1

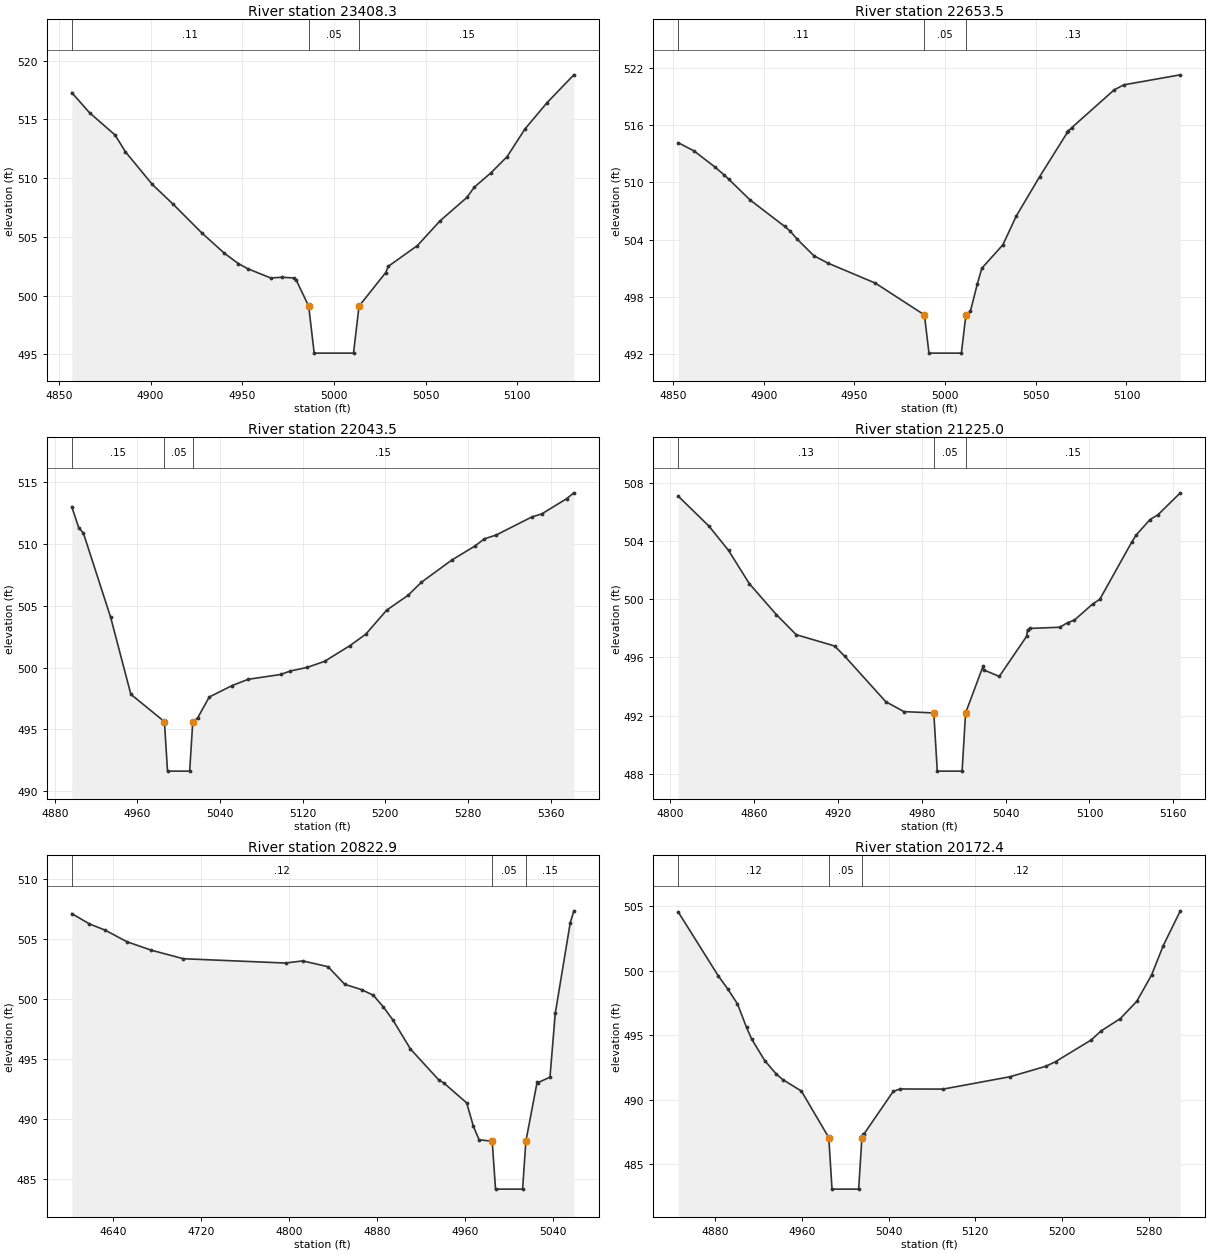
Type RM Length L Ch R = 1 ,23408.3,754.8,754.8,754.8
XS GIS Cut Line= 3
      1894384.86       766350.21      1894432.12       766215.25
      1894477.04       766092.40
BEGIN DESCRIPTION:
South Fork 38.0
END DESCRIPTION:
#Sta/Elev= 29
    4857  517.29  4866.7  515.57  4880.6  513.68  4886.3  512.24  4900.9  509.47
  4912.3  507.78  4927.9  505.34  4940.2  503.61  4947.9  502.72  4953.1  502.28
  4965.5   501.5  4971.6  501.56  4978.4   501.5  4979.4  501.32  4986.2   499.1
  4989.2   495.1 5010.65   495.1 5013.65   499.1  5028.2  501.96  5029.6  502.49
  5045.5  504.26  5057.8  506.36  5072.5  508.36  5076.5  509.23  5085.7  510.47
  5094.4  511.83  5104.1  514.18  5116.2  516.43  5130.8   518.8
#Mann= 3 , 1 , 0
 4857.00    0.11       0  4986.2    0.05       0 5013.65    0.15       0
Bank Sta=4986.20,5013.65
Exp/Cntr=0.3,0.1

Type RM Length L Ch R = 1 ,22653.5,610,610,610
XS GIS Cut Line= 3
      1894564.29       766604.13      1894702.75       766653.81
      1894826.53       766692.43
BEGIN DESCRIPTION:
South Fork 37.0
END DESCRIPTION:
#Sta/Elev= 28
  4852.9  514.16  4861.6   513.3  4872.9  511.65  4878.3  510.77  4880.8  510.33
  4892.4  508.18  4911.6  505.39  4914.6  504.91  4918.3  504.09  4927.7  502.32
  4935.4  501.55  4961.6  499.45 4988.63  496.12 4991.13  492.12    5009  492.12
  5011.5  496.12    5014  496.52  5017.8  499.38  5020.3  501.02  5031.9  503.47
  5039.2  506.46  5052.2  510.62  5067.4  515.23    5068   515.4  5069.8  515.73
  5093.2  519.69  5098.5  520.22  5129.7  521.27
#Mann= 3 , 1 , 0
 4852.90    0.11       0 4988.63    0.05       0  5011.5    0.13       0
Bank Sta=4988.63,5011.50
Exp/Cntr=0.3,0.1

Type RM Length L Ch R = 1 ,22043.5,818.5,818.5,818.5
XS GIS Cut Line= 3
      1894230.09       767146.91      1894332.87       767134.88
      1894679.17       766972.19
BEGIN DESCRIPTION:
South Fork 36.0
END DESCRIPTION:
#Sta/Elev= 30
  4896.5     513  4903.3  511.29  4907.7  510.88  4934.1  504.07  4953.7  497.84
  4986.2  495.63  4989.2  491.63 5010.65  491.63 5013.65  495.63  5018.3  495.92
  5029.6  497.62  5051.6  498.54  5067.3  499.05  5098.6  499.44  5108.1  499.72
  5124.3  500.01  5141.2   500.5  5165.8  501.77  5181.2   502.7  5201.4  504.64
  5222.1  505.84  5235.1   506.9  5264.3  508.68    5287  509.83  5295.9   510.4
  5307.4  510.71  5341.9  512.17  5351.6  512.42  5375.5  513.64  5382.6  514.12
#Mann= 3 , 1 , 0
 4896.50    0.15       0  4986.2    0.05       0 5013.65    0.15       0
Bank Sta=4986.20,5013.65
Exp/Cntr=0.3,0.1

Type RM Length L Ch R = 1 ,21225.0,402.1,402.1,402.1
XS GIS Cut Line= 4
      1894674.96       767474.63      1894841.13       767374.12
      1894909.86       767335.66      1894898.40       767250.19
BEGIN DESCRIPTION:
South Fork 35.0
END DESCRIPTION:
#Sta/Elev= 30
  4805.8  507.08  4827.8  505.02  4841.8  503.35  4856.7  501.06  4876.1  498.93
  4890.2  497.56  4917.7  496.78  4925.1  496.06  4954.3  492.95  4967.3  492.27
 4988.63  492.18 4991.13  488.18 5008.88  488.18 5011.38  492.18    5024  495.42
  5024.3  495.14  5035.5  494.69    5055  497.44  5055.7  497.91  5057.6  497.99
  5078.8  498.07  5084.4  498.39  5089.1  498.55  5102.3  499.67  5107.4  499.99
  5130.4  503.95  5133.5  504.42  5143.3  505.47  5149.1  505.81    5165  507.31
#Mann= 3 , 1 , 0
 4805.80    0.13       0 4988.63    0.05       0 5011.38    0.15       0
Bank Sta=4988.63,5011.38
Exp/Cntr=0.3,0.1

Type RM Length L Ch R = 1 ,20822.9,650.5,650.5,650.5
XS GIS Cut Line= 3
      1894802.97       767656.73      1895174.25       767514.75
      1895231.89       767526.87
BEGIN DESCRIPTION:
South Fork 34.0
END DESCRIPTION:
#Sta/Elev= 30
  4602.5  507.13  4618.5  506.27  4632.8  505.75  4652.6  504.78  4674.9  504.07
  4703.9  503.36  4796.8     503  4812.5  503.18  4835.5  502.69  4850.7  501.22
  4865.9  500.78  4876.6  500.31  4885.6  499.35  4894.3  498.26  4910.4  495.82
  4935.9  493.26  4940.9  492.97  4961.5  491.32  4967.6  489.36  4972.8  488.24
  4984.7  488.12  4987.7  484.12  5012.3  484.12  5015.3  488.12  5025.6   493.1
  5026.2  493.01  5037.2  493.47    5042  498.79  5055.6  506.35  5058.9  507.36
#Mann= 3 , 1 , 0
 4602.50    0.12       0  4984.7    0.05       0  5015.3    0.15       0
Bank Sta=4984.70,5015.30
Exp/Cntr=0.3,0.1

Type RM Length L Ch R = 1 ,20172.4,534,534,534
XS GIS Cut Line= 3
      1894725.24       767800.10      1894847.25       767894.56
      1895096.65       768077.50
BEGIN DESCRIPTION:
South Fork 33.0
END DESCRIPTION:
#Sta/Elev= 29
  4845.7  504.55  4882.8  499.58  4891.4  498.58  4900.4  497.42  4908.8  495.59
  4913.5  494.69  4925.6  493.02  4936.2  491.98  4942.2  491.55  4959.4  490.66
  4984.7  487.05  4987.7  483.05  5012.3  483.05  5015.3  487.05  5016.6  487.31
  5016.9  487.29  5044.2  490.63  5050.4  490.82  5090.3  490.81  5152.1  491.77
  5185.1  492.58  5194.1  492.94    5227  494.62  5236.1  495.32  5253.9  496.28
    5269  497.61  5282.7  499.65  5293.6  501.95  5309.3  504.64
#Mann= 3 , 1 , 0
 4845.70    0.12       0  4984.7    0.05       0  5015.3    0.12       0
Bank Sta=4984.70,5015.30
Exp/Cntr=0.3,0.1

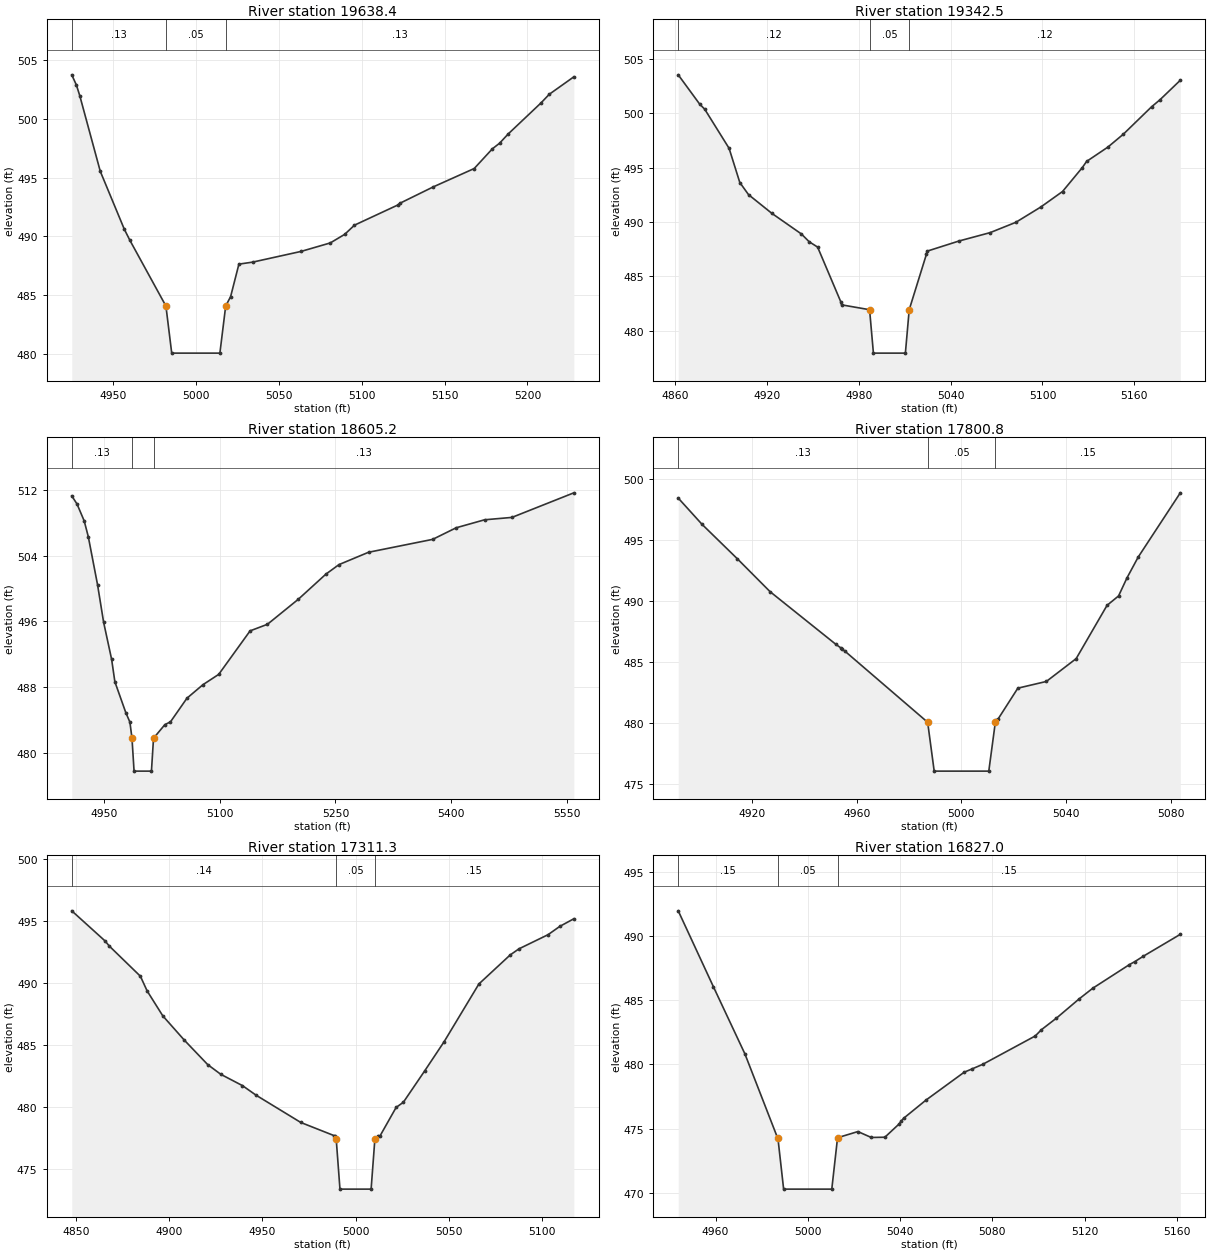
Type RM Length L Ch R = 1 ,19638.4,295.9,295.9,295.9
XS GIS Cut Line= 3
      1894425.18       768241.95      1894489.50       768280.12
      1894684.92       768397.58
BEGIN DESCRIPTION:
South Fork 32.0
END DESCRIPTION:
#Sta/Elev= 27
  4925.2  503.73    4928  502.86    4930  501.97  4942.4  495.53  4956.9  490.61
  4960.3  489.66 4981.98  484.09 4985.48  480.09 5014.53  480.09 5018.03  484.09
    5021  484.89    5026  487.65  5034.3  487.82  5063.5  488.73  5081.1  489.45
  5089.8  490.18  5095.7  490.96  5121.8  492.67  5123.1  492.82  5143.2  494.21
  5167.9  495.77  5178.9  497.45  5183.2  497.92  5188.5  498.72  5208.1  501.33
  5213.2  502.08    5228  503.56
#Mann= 3 , 1 , 0
 4925.20    0.13       0 4981.98    0.05       0 5018.03    0.13       0
Bank Sta=4981.98,5018.03
Exp/Cntr=0.3,0.1

Type RM Length L Ch R = 1 ,19342.5,737.3,737.3,737.3
XS GIS Cut Line= 3
      1894316.59       768542.63      1894447.73       768572.43
      1894635.60       768618.02
BEGIN DESCRIPTION:
South Fork 31.0
END DESCRIPTION:
#Sta/Elev= 30
  4862.2  503.56  4876.1  500.88  4879.5  500.39  4895.4  496.79  4902.4  493.64
  4908.1  492.52  4923.4  490.79  4942.6   488.9  4947.7  488.18  4953.2  487.69
  4968.3  482.66  4968.8  482.37 4987.13  481.92 4989.63  477.92  5010.5  477.92
    5013  481.92  5024.2  487.01  5024.6  487.31  5045.5  488.25  5065.8  489.02
  5082.6  489.97  5098.9  491.38  5113.1  492.81    5126  495.01  5128.8  495.58
  5142.7   496.9  5152.8  498.09  5171.2  500.61  5176.7  501.26    5190  503.06
#Mann= 3 , 1 , 0
 4862.20    0.12       0 4987.13    0.05       0    5013    0.12       0
Bank Sta=4987.13,5013.00
Exp/Cntr=0.3,0.1

Type RM Length L Ch R = 1 ,18605.2,804.4,804.4,804.4
XS GIS Cut Line= 4
      1894296.89       769190.09      1894324.25       769102.25
      1894380.03       768955.24      1894713.48       768730.77
BEGIN DESCRIPTION:
South Fork 30.0
END DESCRIPTION:
#Sta/Elev= 30
    4908  511.26  4914.8  510.27  4924.1  508.22  4929.4  506.31  4941.4  500.47
  4949.3  495.89  4959.7  491.37  4963.9  488.65  4978.1  484.89  4983.4  483.74
  4986.1  481.78  4988.8  477.78 5011.34  477.78 5014.04  481.78  5028.8  483.44
    5036  483.77  5057.4  486.65  5078.1  488.29  5098.6  489.55  5139.3  494.84
  5161.8  495.64  5201.9  498.69  5237.6  501.74  5254.6   502.9  5292.9   504.4
  5376.1  505.97  5406.6  507.38  5443.4  508.35  5478.9  508.64  5559.2  511.63
#Mann= 3 , 1 , 0
 4908.00    0.13       0  4986.1    0.05       0 5014.04    0.13       0
Bank Sta=4986.10,5014.04
Exp/Cntr=0.3,0.1

Type RM Length L Ch R = 1 ,17800.8,489.5,489.5,489.5
XS GIS Cut Line= 3
      1894770.41       769273.03      1894873.37       769239.81
      1894955.21       769222.21
BEGIN DESCRIPTION:
South Fork 29.0
END DESCRIPTION:
#Sta/Elev= 22
  4891.8   498.4  4900.9  496.25  4914.4  493.43  4926.9  490.74  4952.1  486.42
    4954  486.13  4954.4  486.03  4955.4  485.89 4987.13  480.05 4989.63  476.05
  5010.5  476.05    5013  480.05  5013.4   480.2    5014   480.3  5021.6  482.84
  5032.5  483.39  5043.9  485.26  5055.7  489.62  5060.1  490.39  5063.3  491.86
  5067.6  493.57  5083.7  498.83
#Mann= 3 , 1 , 0
 4891.80    0.13       0 4987.13    0.05       0    5013    0.15       0
Bank Sta=4987.13,5013.00
Exp/Cntr=0.3,0.1

Type RM Length L Ch R = 1 ,17311.3,484.3,484.3,484.3
XS GIS Cut Line= 3
      1894770.50       769620.46      1894881.00       769725.12
      1894967.43       769803.98
BEGIN DESCRIPTION:
South Fork 28.0
END DESCRIPTION:
#Sta/Elev= 30
  4847.8   495.8  4865.6  493.38    4868  492.95  4884.6  490.53  4888.2  489.35
  4896.6  487.34  4908.1  485.39  4920.7  483.41  4927.7  482.63  4939.3  481.72
  4946.7  480.94  4970.6  478.75  4988.3   477.7  4988.8  477.65  4989.6  477.38
  4991.6  473.38  5008.3  473.38  5010.3  477.38  5012.1  477.69  5012.9  477.62
  5021.7  479.96  5025.6  480.38    5037   482.9  5047.5  485.27  5066.1  489.91
  5082.9  492.25  5087.6  492.74  5103.2  493.88  5109.5  494.55    5117  495.16
#Mann= 3 , 1 , 0
 4847.80    0.14       0  4989.6    0.05       0  5010.3    0.15       0
Bank Sta=4989.60,5010.30
Exp/Cntr=0.3,0.1

Type RM Length L Ch R = 1 ,16827.0,852.6,852.6,852.6
XS GIS Cut Line= 3
      1894590.03       770107.84      1894645.65       770108.89
      1894782.58       770022.19
BEGIN DESCRIPTION:
South Fork 27.0
END DESCRIPTION:
#Sta/Elev= 27
  4943.8  491.96    4959  486.07  4972.7  480.83  4986.8  474.32    4987   474.3
  4989.5   470.3 5010.38   470.3 5012.88   474.3  5021.7  474.78  5027.5  474.32
  5033.4  474.34  5039.5  475.36  5040.6  475.62  5041.5  475.81  5051.3  477.24
  5067.8   479.4    5071  479.64  5075.8  480.01  5098.6  482.22  5101.3  482.71
  5107.8  483.61  5117.6   485.1  5123.5  485.93  5139.4  487.77  5141.8  488.01
  5145.4  488.42  5161.5  490.13
#Mann= 3 , 1 , 0
 4943.80    0.15       0    4987    0.05       0 5012.88    0.15       0
Bank Sta=4987.00,5012.88
Exp/Cntr=0.3,0.1

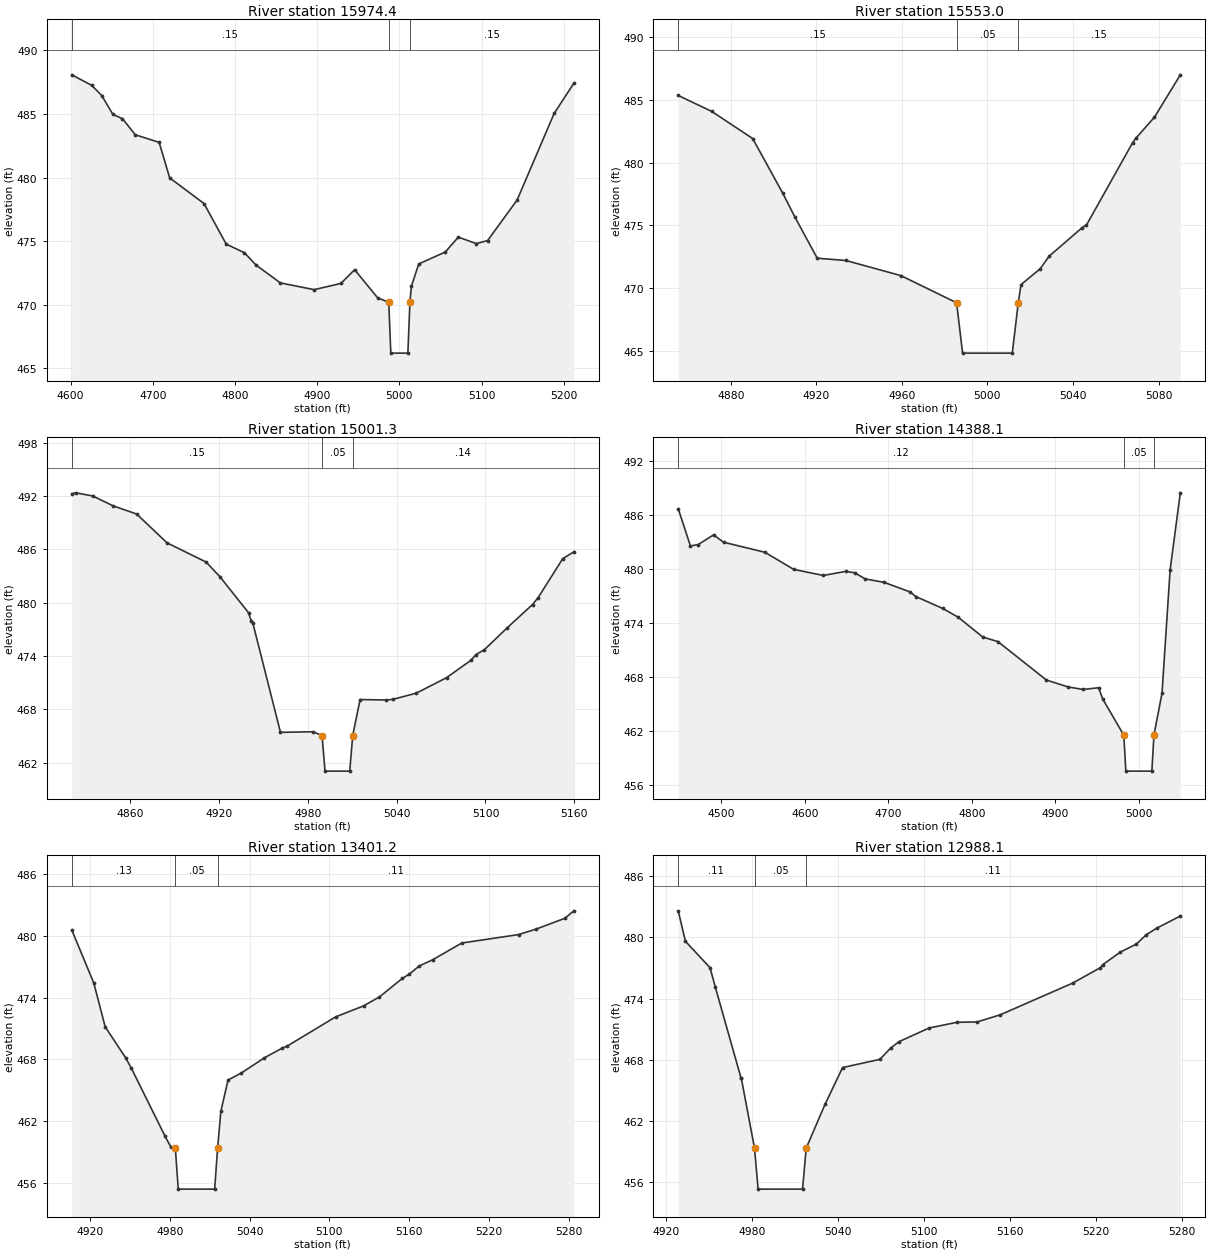
Type RM Length L Ch R = 1 ,15974.4,421.4,421.4,421.4
XS GIS Cut Line= 3
      1894938.64       770345.69      1895312.32       770218.27
      1895465.05       770065.54
BEGIN DESCRIPTION:
South Fork 26.0
END DESCRIPTION:
#Sta/Elev= 30
  4601.5  488.08  4625.8  487.25    4638  486.45  4651.5  484.97  4663.2  484.63
  4678.7  483.37  4707.8  482.77  4720.6  479.98  4762.4  477.96  4789.4  474.77
  4811.6  474.09  4825.7  473.12  4855.3  471.72  4896.4  471.19  4928.9  471.68
  4945.6  472.76  4973.7  470.54 4987.13   470.2 4989.63   466.2 5010.38   466.2
 5012.88   470.2  5014.7  471.46  5023.6  473.21  5055.9  474.15  5071.8  475.32
  5093.6  474.81  5107.4  475.05  5143.3  478.24  5188.3  485.04  5212.3  487.42
#Mann= 3 , 1 , 0
 4601.50    0.15       0 4987.13    0.05       0 5012.88    0.15       0
Bank Sta=4987.13,5012.88
Exp/Cntr=0.3,0.1

Type RM Length L Ch R = 1 ,15553.0,551.7,551.7,551.7
XS GIS Cut Line= 3
      1894980.58       770415.33      1895119.61       770463.06
      1895181.31       770525.53
BEGIN DESCRIPTION:
South Fork 25.0
END DESCRIPTION:
#Sta/Elev= 21
  4855.4  485.33  4871.1  484.06  4890.2  481.91  4904.3  477.56  4909.9  475.69
  4920.4   472.4  4933.8  472.22  4959.5  471.02 4985.58  468.86 4988.38  464.86
 5011.62  464.86 5014.42  468.86  5015.7   470.3  5024.7  471.57  5028.8  472.55
  5044.3  474.83  5046.3  475.03  5067.9  481.58  5069.6  481.97  5078.1   483.6
  5090.2  486.97
#Mann= 3 , 1 , 0
 4855.40    0.15       0 4985.58    0.05       0 5014.42    0.15       0
Bank Sta=4985.58,5014.42
Exp/Cntr=0.3,0.1

Type RM Length L Ch R = 1 ,15001.3,613.2,613.2,613.2
XS GIS Cut Line= 3
      1894660.30       770926.50      1894830.10       770868.52
      1894985.71       770832.47
BEGIN DESCRIPTION:
South Fork 24.0
END DESCRIPTION:
#Sta/Elev= 30
  4820.5  492.25  4823.4  492.35  4834.7  491.99  4848.4  490.89  4864.4  489.96
  4884.8  486.73  4911.3  484.56  4920.7  482.89  4939.9  478.87  4941.7  477.96
  4942.8  477.72  4961.5  465.41  4983.5  465.48  4989.6  465.05  4991.6  461.05
  5008.3  461.05  5010.3  465.05  5015.3   469.1    5033  469.05  5037.4  469.12
  5053.3  469.82  5073.7  471.56  5090.3  473.53  5093.6  474.16  5099.3  474.71
  5114.8  477.19  5131.8  479.79  5135.6  480.57  5152.2  484.95  5159.7  485.71
#Mann= 3 , 1 , 0
 4820.50    0.15       0  4989.6    0.05       0  5010.3    0.14       0
Bank Sta=4989.60,5010.30
Exp/Cntr=0.3,0.1

Type RM Length L Ch R = 1 ,14388.1,986.9,986.9,986.9
XS GIS Cut Line= 4
      1894727.21       771665.14      1894722.85       771527.01
      1895114.50       771395.00      1895164.05       771398.85
BEGIN DESCRIPTION:
South Fork 23.0
END DESCRIPTION:
#Sta/Elev= 30
  4448.5  486.66  4463.1  482.52  4472.4  482.68  4490.9  483.76  4502.7  482.94
  4552.3  481.82  4586.7  479.92  4622.4  479.24    4649   479.7  4659.8  479.54
  4672.4  478.86  4694.9  478.48  4725.9  477.42  4733.2  476.89  4765.1  475.58
  4783.6  474.61  4813.1   472.4  4831.3  471.89  4889.3  467.62  4915.6  466.84
  4933.5  466.57  4951.8  466.76  4956.9  465.49    4982  461.49  4984.5  457.49
 5015.63  457.49 5018.13  461.49  5027.8  466.16  5037.5  479.87  5049.7  488.43
#Mann= 3 , 1 , 0
 4448.50    0.12       0    4982    0.05       0 5018.13    0.13       0
Bank Sta=4982.00,5018.13
Exp/Cntr=0.3,0.1

Type RM Length L Ch R = 1 ,13401.2,413.1,413.1,413.1
XS GIS Cut Line= 3
      1894927.48       772116.78      1895014.52       772079.10
      1895255.64       771931.60
BEGIN DESCRIPTION:
South Fork 22.0
END DESCRIPTION:
#Sta/Elev= 29
  4906.3  480.58  4922.9   475.4  4931.4  471.16  4946.8  468.14    4951  467.15
  4976.4  460.52  4980.6   459.5 4984.16  459.36 4986.36  455.36 5013.75  455.36
 5015.95  459.36  5018.4  462.92  5023.8  465.98  5033.7  466.65  5050.9  468.12
  5064.5  469.08  5068.4  469.29  5104.7  472.12  5125.7  473.19  5137.6  474.06
  5154.9  475.87  5160.2  476.29  5167.6  477.08  5177.7  477.68  5199.6  479.31
  5242.3  480.13  5255.6  480.67    5277  481.71  5283.8  482.44
#Mann= 3 , 1 , 0
 4906.30    0.13       0 4984.16    0.05       0 5015.95    0.11       0
Bank Sta=4984.16,5015.95
Exp/Cntr=0.3,0.1

Type RM Length L Ch R = 1 ,12988.1,500.7,500.7,500.7
XS GIS Cut Line= 3
      1895173.76       772487.58      1895216.50       772430.63
      1895395.41       772216.68
BEGIN DESCRIPTION:
South Fork 21.0
END DESCRIPTION:
#Sta/Elev= 27
  4928.8  482.59  4933.8  479.61    4951  477.02  4954.6  475.15  4972.6  466.22
  4972.8  466.19    4982  459.35  4984.5  455.35  5015.5  455.35    5018  459.35
  5031.2  463.66  5043.4  467.25  5069.4  468.05    5077  469.17  5082.7  469.78
  5103.7  471.12  5123.2  471.68  5137.1  471.71  5153.3  472.41  5203.9  475.52
  5223.2  477.03  5224.9  477.33  5237.1  478.55  5248.3  479.34  5255.1  480.24
  5262.3  480.88  5278.9  482.08
#Mann= 3 , 1 , 0
 4928.80    0.11       0    4982    0.05       0    5018    0.11       0
Bank Sta=4982.00,5018.00
Exp/Cntr=0.3,0.1

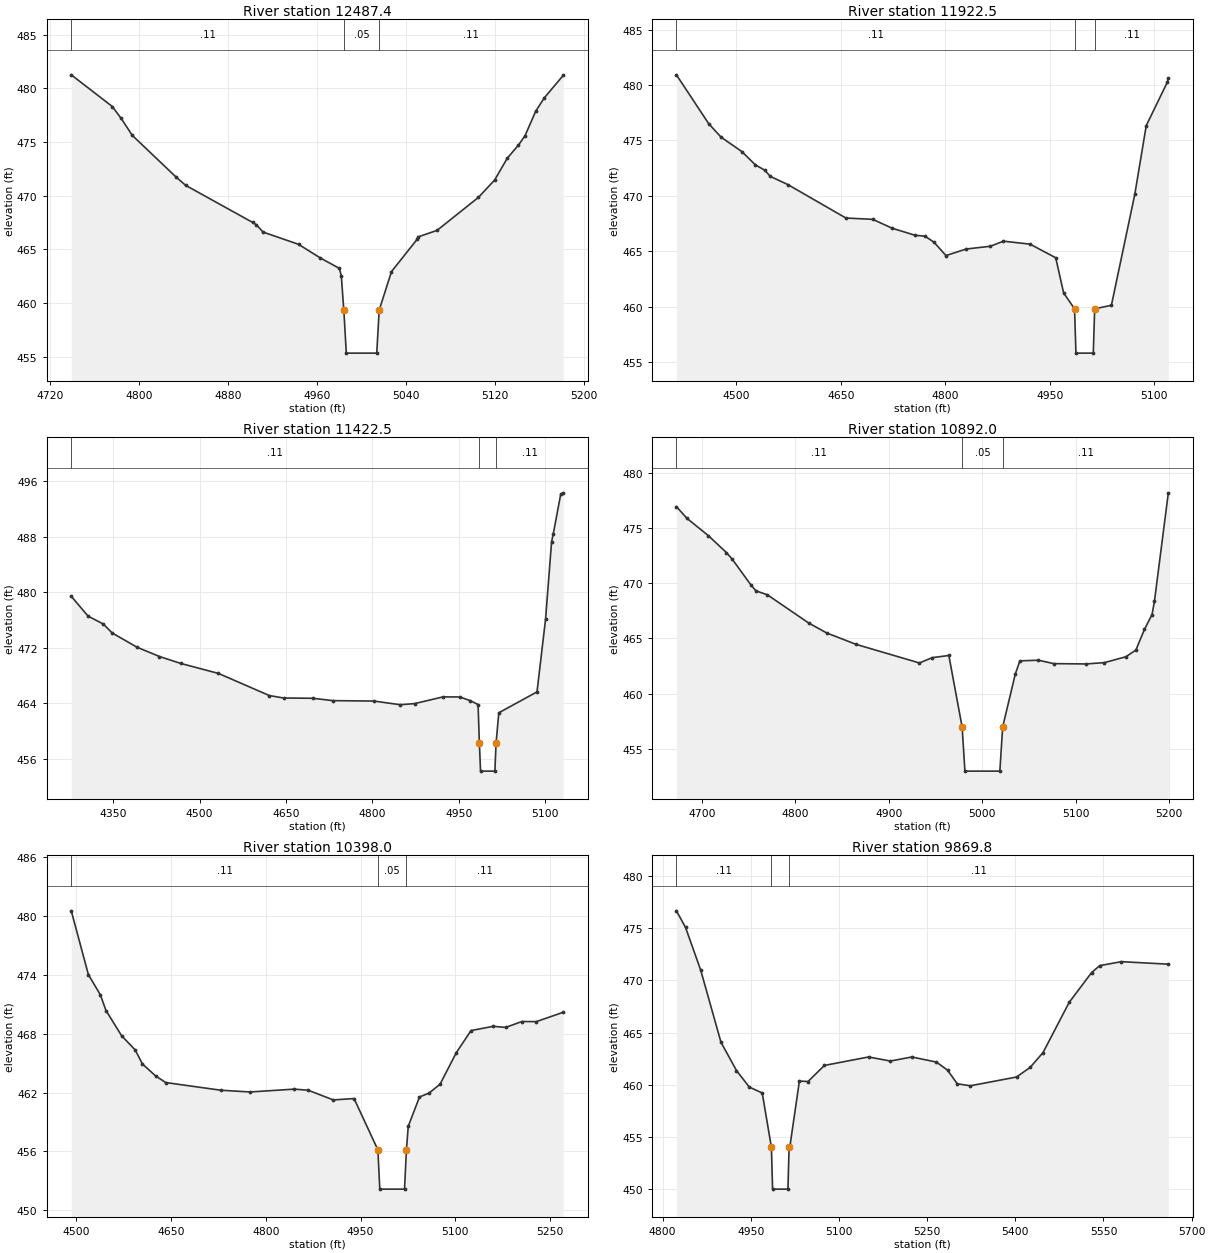
Type RM Length L Ch R = 1 ,12487.4,564.9,564.9,564.9
XS GIS Cut Line= 4
      1895694.08       772633.62      1895754.10       772537.43
      1895715.04       772399.41      1895648.67       772226.11
BEGIN DESCRIPTION:
South Fork 20.0
END DESCRIPTION:
#Sta/Elev= 30
  4738.9  481.25  4775.8   478.3  4783.8  477.19  4793.8  475.61  4833.1  471.74
  4841.8  470.96    4902  467.51  4905.4  467.29  4911.4  466.61  4943.3  465.47
  4962.6  464.22    4980  463.23  4981.8  462.53    4984  459.33 4984.05  459.34
 4986.25  455.34 5013.64  455.34 5015.84  459.34  5026.9  462.93  5049.9  465.93
  5051.1  466.17  5067.9  466.77  5105.1  469.84  5119.7  471.46    5131  473.48
  5141.1  474.71    5147  475.58  5156.6  477.86  5164.3   479.1  5181.3  481.19
#Mann= 3 , 1 , 0
 4738.90    0.11       0 4984.05    0.05       0 5015.84    0.11       0
Bank Sta=4984.05,5015.84
Exp/Cntr=0.3,0.1

Type RM Length L Ch R = 1 ,11922.5,500,500,500
XS GIS Cut Line= 3
      1895868.47       772741.21      1896257.72       772303.46
      1896301.09       772191.34
BEGIN DESCRIPTION:
South Fork 19.0
END DESCRIPTION:
#Sta/Elev= 30
  4414.2  480.93  4460.5  476.52  4478.3   475.3  4508.1     474  4527.5   472.8
  4540.9  472.32  4548.9  471.76  4574.1  471.02  4657.4     468    4696  467.88
  4723.7  467.08  4756.9  466.44    4771  466.36    4784  465.81    4801  464.61
  4830.1   465.2  4864.7  465.45  4883.6  465.91  4921.8  465.64  4958.6  464.41
  4969.9  461.24  4985.6   459.8  4987.6   455.8  5012.5   455.8  5014.5   459.8
  5038.5  460.12  5072.1  470.15  5088.5  476.34  5118.7  480.26  5120.2   480.6
#Mann= 3 , 1 , 0
 4414.20    0.11       0  4985.6    0.05       0  5014.5    0.11       0
Bank Sta=4985.60,5014.50
Exp/Cntr=0.3,0.1

Type RM Length L Ch R = 1 ,11422.5,530.5,530.5,530.5
XS GIS Cut Line= 3
      1896106.64       772919.76      1896689.00       772498.37
      1896769.00       772389.67
BEGIN DESCRIPTION:
South Fork 18.0
END DESCRIPTION:
#Sta/Elev= 30
  4277.2  479.42  4306.4  476.56  4332.9  475.42  4348.1  474.14  4391.5  472.07
  4430.3  470.74  4466.9  469.75  4532.7   468.3  4621.1  465.11  4645.8  464.76
  4696.4  464.72  4731.4  464.38  4802.4  464.32  4848.2  463.79  4873.1  463.95
  4922.5  464.92  4951.7  464.91  4969.3  464.39  4983.3  463.82  4985.6  458.22
  4987.6  454.22  5012.5  454.22  5014.5  458.22  5019.3  462.63  5085.6  465.64
  5100.5  476.16  5110.9  487.27  5113.9  488.45  5126.8  494.14    5131  494.33
#Mann= 3 , 1 , 0
 4277.20    0.11       0  4985.6    0.05       0  5014.5    0.11       0
Bank Sta=4985.60,5014.50
Exp/Cntr=0.3,0.1

Type RM Length L Ch R = 1 ,10892.0,494,494,494
XS GIS Cut Line= 3
      1896897.40       773090.89      1897093.63       772829.19
      1897102.34       772630.48
BEGIN DESCRIPTION:
South Fork 17.0
END DESCRIPTION:
#Sta/Elev= 30
  4672.9  476.96  4684.1   475.9    4707  474.33  4726.4  472.79  4732.5   472.2
  4752.6  469.85  4757.9  469.32    4770  468.97  4814.4   466.4  4833.6   465.5
  4864.9  464.47  4932.7  462.78  4946.4  463.26  4964.2  463.46  4978.4  456.97
  4981.4  452.97 5018.75  452.97 5021.75  456.97  5035.3  461.79  5040.2  462.97
    5060  463.03  5076.3  462.72  5110.7  462.69  5130.6  462.81  5153.4  463.34
  5164.2  463.95  5173.4  465.83  5181.5  467.17  5184.1   468.4  5198.9  478.21
#Mann= 3 , 1 , 0
 4672.90    0.11       0  4978.4    0.05       0 5021.75    0.11       0
Bank Sta=4978.40,5021.75
Exp/Cntr=0.3,0.1

Type RM Length L Ch R = 1 ,10398.0,528.2,528.2,528.2
XS GIS Cut Line= 3
      1896986.18       773176.98      1897422.50       772916.81
      1897670.47       772808.43
BEGIN DESCRIPTION:
South Fork 16.0
END DESCRIPTION:
#Sta/Elev= 30
    4492  480.52  4519.1  474.02  4537.9  471.98    4547  470.36  4571.6   467.8
  4593.2  466.34  4604.7  464.91  4625.6  463.69  4641.6  463.02  4728.6  462.24
  4774.9  462.06  4844.9  462.35  4866.9  462.24  4906.8  461.25  4939.6  461.39
 4977.35  456.16 4980.35  452.16  5019.5  452.16  5022.5  456.16  5025.4  458.56
  5043.2  461.55  5058.1  461.94  5075.7  462.85  5101.5  466.07  5124.8  468.32
  5159.9  468.75  5179.7  468.64  5205.3  469.24  5228.1  469.23  5270.6  470.18
#Mann= 3 , 1 , 0
 4492.00    0.11       0 4977.35    0.05       0  5022.5    0.11       0
Bank Sta=4977.35,5022.50
Exp/Cntr=0.3,0.1

Type RM Length L Ch R = 1 ,9869.8,577.4,577.4,577.4
XS GIS Cut Line= 3
      1897222.93       773386.24      1897344.95       773407.38
      1897751.20       772821.45
BEGIN DESCRIPTION:
South Fork 15.0
END DESCRIPTION:
#Sta/Elev= 30
  4823.4  476.66  4838.9  475.07  4864.8  470.96  4899.2  464.07  4925.6  461.36
  4947.3  459.78  4969.4  459.21    4985     454    4987     450  5013.1     450
  5015.1     454  5016.8  454.22  5032.6  460.35  5047.3  460.31  5075.2  461.85
  5150.3  462.66  5187.5  462.27  5223.9  462.66  5265.7  462.17  5284.6   461.4
  5301.2  460.09  5323.4   459.9    5402  460.74  5425.2  461.66  5447.1  463.08
  5491.6  467.89  5529.8  470.75  5543.6  471.41  5580.3  471.79  5660.3  471.55
#Mann= 3 , 1 , 0
 4823.40    0.11       0    4985    0.05       0  5015.1    0.11       0
Bank Sta=4985.00,5015.10
Exp/Cntr=0.5,0.3