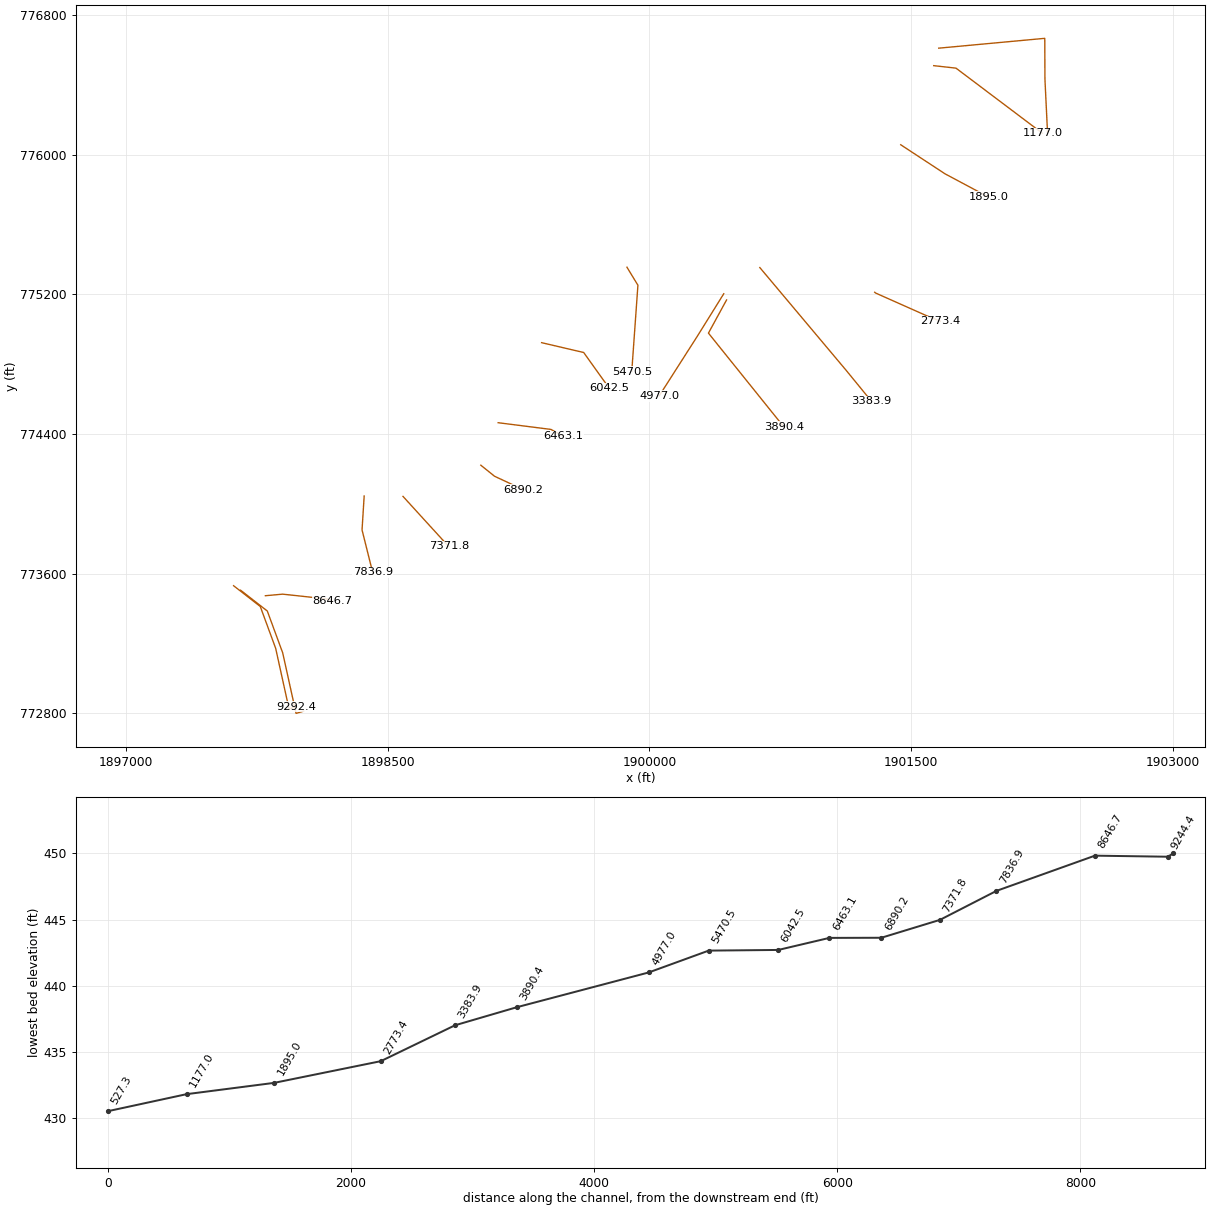
HEC-RAS study SOUTH FORK.PRJ: South Fork

--- SOUTH FORK.g01 (geometry) --- (continued)

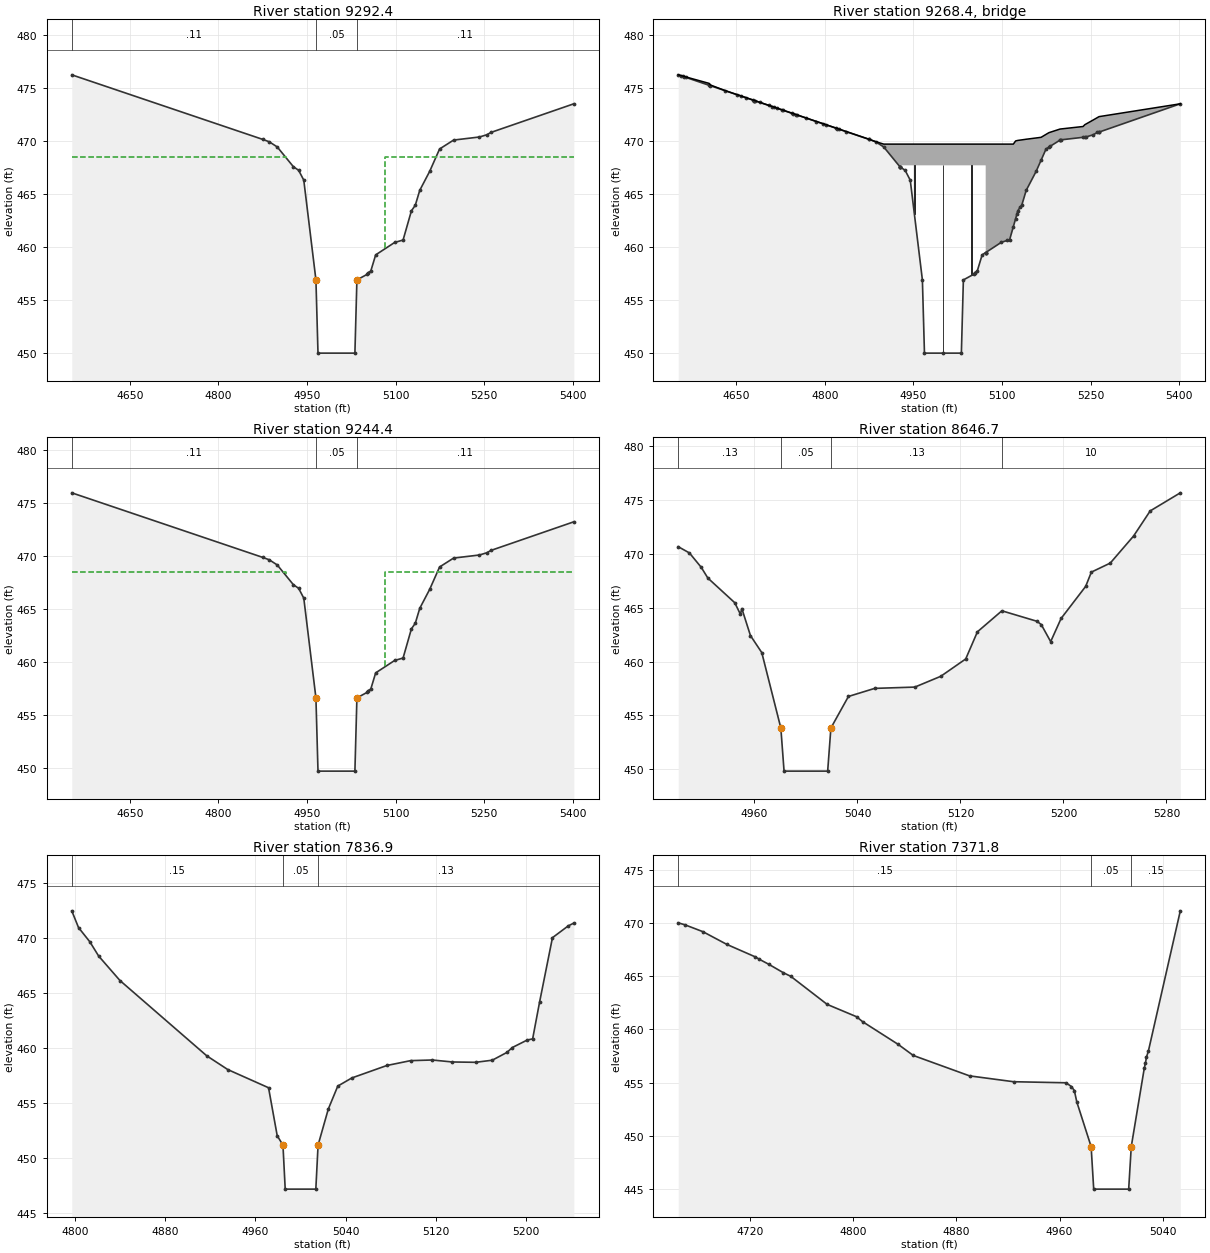
Type RM Length L Ch R = 1 ,9292.4,48,48,48
XS GIS Cut Line= 5
      1897616.36       773530.07      1897769.28       773410.96
      1897857.51       773171.27      1897934.16       772824.03
      1897977.49       772836.78
BEGIN DESCRIPTION:
Upstream Section of Bridge/Culvert/Weir
END DESCRIPTION:
#Sta/Elev= 27
  4551.9  476.23  4874.9  470.15  4886.2  469.92  4899.8  469.43  4927.1  467.57
    4936  467.23  4944.7   466.3 4965.25   456.9 4968.75     450 5031.25     450
 5034.63   456.9  5052.4  457.44  5053.8  457.59  5058.1  457.73  5066.4  459.26
  5098.5  460.43  5112.8  460.66  5126.9  463.41  5133.5  463.94    5141  465.34
  5157.9  467.14  5174.6  469.24  5198.3  470.08    5242  470.37  5254.6  470.58
  5261.5   470.8  5401.9   473.5
#Mann= 3 , 1 , 0
 4551.90    0.11       0 4965.25    0.05       0 5034.63    0.11       0
#XS Ineff= 2 , 0
       0    4915   468.5    5083       0   468.5
Bank Sta=4965.25,5034.63
Exp/Cntr=0.5,0.3

Type RM Length L Ch R = 3 ,9268.4,,,
BEGIN DESCRIPTION:
South Fork - Lindley Rd
Structure ID: NCF-0100
Approximate Survey Structure
END DESCRIPTION:
Bridge Culvert--1,0,-1,-1, 0
Deck Dist Width WeirC Skew NumUp NumDn MinLoCord MaxHiCord MaxSubmerge Is_Ogee
10,28,2.6,, 28, 28,,,0.95,0,1,1,,
  4551.9  4604.4  4606.5  4631.6  4874.9  4886.2  4899.8 4927.41  4927.5 5072.39
  5072.5  5098.5  5112.8  5119.2  5123.1  5126.9  5133.5    5141  5157.9  5166.2
  5174.6  5179.5  5198.3  5237.3  5240.2  5254.6  5264.3  5401.9
  476.23  475.42  475.27  474.74  470.16  469.93   469.7   469.7   469.7   469.7
   469.7   469.7   469.7   469.7     470  470.05   470.1  470.16  470.28  470.34
  470.62  470.78  471.12  471.36  471.53  471.98  472.29   473.5
  476.23  475.24   475.2  474.73  470.15  469.92  469.43  467.56   467.7   467.7
  459.48  460.43  460.66  461.91  462.67  463.41  463.94  465.34  467.14  468.18
  469.24  469.41  470.08  470.34  470.36  470.58  470.83   473.5
  4551.9  4604.4  4606.5  4631.6  4874.9  4886.2  4899.8 4927.41  4927.5 5072.39
  5072.5  5098.5  5112.8  5119.2  5123.1  5126.9  5133.5    5141  5157.9  5166.2
  5174.6  5179.5  5198.3  5237.3  5240.2  5254.6  5264.3  5401.9
  476.23  475.42  475.27  474.74  470.16  469.93   469.7   469.7   469.7   469.7
   469.7   469.7   469.7   469.7     470  470.05   470.1  470.16  470.28  470.34
  470.62  470.78  471.12  471.36  471.53  471.98  472.29   473.5
  475.98  474.99  474.95  474.48   469.9  469.67  469.18  467.31  467.45  467.45
  459.23  460.18  460.41  461.66  462.42  463.16  463.69  465.09  466.89  467.93
  468.99  469.16  469.83  470.09  470.11  470.33  470.58  473.25
Pier Skew, UpSta & Num, DnSta & Num=,4951.7, 2 ,4951.7, 2 , 0 , 0 , 0 ,,
       1       1
  461.87   468.7
       1       1
  461.62  468.45
Pier Skew, UpSta & Num, DnSta & Num=,5000.0, 2 ,5000.0, 2 , 0 , 0 , 0 ,,
       1       1
     449   468.7
       1       1
  448.75  468.45
Pier Skew, UpSta & Num, DnSta & Num=,5048.4, 2 ,5048.4, 2 , 0 , 0 , 0 ,,
       1       1
   456.3   468.7
       1       1
  456.05  468.45
BR Coef= 1 , 1 , 0 ,1.25, 0 ,,,0.8,0,2,0,
Wspro=,,,, 1 ,,,, 0 ,,,, 0 ,,,,-1 ,-1 ,-1 , 0 , 0 , 0 , 0 , 0
BC Design=,, 0 ,, 0 ,,,,,,
BR U #Sta/Elev= 82
  4551.9  476.23  4556.8  476.14  4559.6  476.09  4560.9  476.06  4564.2     476
  4604.4  475.24  4606.5   475.2  4631.6  474.73  4650.6  474.37  4658.3  474.23
  4666.6  474.07  4678.9  473.84  4680.8   473.8    4681   473.8  4681.2   473.8
  4689.5  473.64  4705.4  473.34  4711.1  473.23  4714.4  473.17  4719.2  473.08
  4727.1  472.93  4728.7   472.9  4745.3  472.59  4745.7  472.58  4750.6  472.49
  4752.9  472.45  4768.1  472.16  4785.6  471.83  4797.3  471.61  4802.6  471.51
  4819.2   471.2  4820.8  471.17  4823.7  471.11  4836.5  470.87  4874.9  470.15
  4875.3  470.14  4886.2  469.92  4899.8  469.43  4927.1  467.57 4927.41  467.56
  4927.5  467.55  4927.6  467.55    4936  467.23  4944.7   466.3 4965.25   456.9
 4968.75     450    5000     450 5031.25     450 5034.63   456.9  5052.4  457.44
  5053.8  457.59  5058.1  457.73  5066.4  459.26  5072.3  459.48 5072.39  459.48
  5072.5  459.48  5098.5  460.43  5108.7  460.62  5112.8  460.66  5119.2  461.91
  5123.1  462.67  5125.3   463.1  5126.9  463.41  5131.1  463.79  5133.5  463.94
    5141  465.34  5157.9  467.14  5166.2  468.18  5174.6  469.24  5179.5  469.41
  5182.1  469.51  5197.8  470.06  5198.3  470.08  5199.5   470.1  5237.3  470.34
  5240.2  470.36    5242  470.37  5254.6  470.58  5261.5   470.8  5263.5  470.81
  5264.3  470.83  5401.9   473.5
BR U #Mann= 3
 4551.90    0.11 4965.25    0.05 5034.63    0.11
BR U Banks=4965.25,5034.63
BR D #Sta/Elev= 82
  4551.9  475.98  4556.8  475.89  4559.6  475.84  4560.9  475.81  4564.2  475.75
  4604.4  474.99  4606.5  474.95  4631.6  474.48  4650.6  474.12  4658.3  473.98
  4666.6  473.82  4678.9  473.59  4680.8  473.55    4681  473.55  4681.2  473.55
  4689.5  473.39  4705.4  473.09  4711.1  472.98  4714.4  472.92  4719.2  472.83
  4727.1  472.68  4728.7  472.65  4745.3  472.34  4745.7  472.33  4750.6  472.24
  4752.9   472.2  4768.1  471.91  4785.6  471.58  4797.3  471.36  4802.6  471.26
  4819.2  470.95  4820.8  470.92  4823.7  470.86  4836.5  470.62  4874.9   469.9
  4875.3  469.89  4886.2  469.67  4899.8  469.18  4927.1  467.32 4927.41  467.31
  4927.5   467.3  4927.6   467.3    4936  466.98  4944.7  466.05 4965.25  456.65
 4968.75  449.75    5000  449.75 5031.25  449.75 5034.63  456.65  5052.4  457.19
  5053.8  457.34  5058.1  457.48  5066.4  459.01  5072.3  459.23 5072.39  459.23
  5072.5  459.23  5098.5  460.18  5108.7  460.37  5112.8  460.41  5119.2  461.66
  5123.1  462.42  5125.3  462.85  5126.9  463.16  5131.1  463.54  5133.5  463.69
    5141  465.09  5157.9  466.89  5166.2  467.93  5174.6  468.99  5179.5  469.16
  5182.1  469.26  5197.8  469.81  5198.3  469.83  5199.5  469.85  5237.3  470.09
  5240.2  470.11    5242  470.12  5254.6  470.33  5261.5  470.55  5263.5  470.56
  5264.3  470.58  5401.9  473.25
BR D #Mann= 3
 4551.90    0.11 4965.25    0.05 5034.63    0.11
BR D Banks=4965.25,5034.63

Type RM Length L Ch R = 1 ,9244.4,597.7,597.7,597.7
XS GIS Cut Line= 5
      1897656.70       773504.07      1897809.62       773384.96
      1897897.85       773145.27      1897974.50       772798.03
      1898017.83       772810.77
BEGIN DESCRIPTION:
Downstream Section of Bridge/Culvert/Weir
END DESCRIPTION:
#Sta/Elev= 27
  4551.9  475.98  4874.9   469.9  4886.2  469.67  4899.8  469.18  4927.1  467.32
    4936  466.98  4944.7  466.05 4965.25  456.65 4968.75  449.75 5031.25  449.75
 5034.63  456.65  5052.4  457.19  5053.8  457.34  5058.1  457.48  5066.4  459.01
  5098.5  460.18  5112.8  460.41  5126.9  463.16  5133.5  463.69    5141  465.09
  5157.9  466.89  5174.6  468.99  5198.3  469.83    5242  470.12  5254.6  470.33
  5261.5  470.55  5401.9  473.25
#Mann= 3 , 1 , 0
 4551.90    0.11       0 4965.25    0.05       0 5034.63    0.11       0
#XS Ineff= 2 , 0
       0    4915   468.5    5083       0   468.5
Bank Sta=4965.25,5034.63
Exp/Cntr=0.5,0.3

Type RM Length L Ch R = 1 ,8646.7,809.8,809.8,809.8
XS GIS Cut Line= 4
      1897798.84       773472.64      1897897.63       773481.62
      1898154.13       773453.84      1898183.91       773440.09
BEGIN DESCRIPTION:
South Fork 14.0
END DESCRIPTION:
#Sta/Elev= 30
  4900.8  470.66  4909.5  470.08  4918.7  468.74  4923.8  467.75  4944.7  465.46
  4949.1  464.39  4950.2  464.92  4956.9  462.41  4965.7  460.83  4980.5  453.83
    4983  449.83 5016.88  449.83 5019.38  453.83    5033  456.76  5053.4  457.51
  5084.6  457.63  5104.7  458.63  5124.1  460.24  5133.2  462.76  5152.2  464.71
  5179.4  463.74  5182.8  463.43  5190.1  461.85  5198.2     464  5217.3  466.98
  5221.7   468.3  5236.4  469.14  5254.5  471.65  5267.4  473.98  5290.8  475.66
#Mann= 4 , 1 , 0
 4900.80    0.13       0  4980.5    0.05       0 5019.38    0.13       0
  5152.2      10       0
Bank Sta=4980.50,5019.38
Exp/Cntr=0.3,0.1

Type RM Length L Ch R = 1 ,7836.9,465.1,465.1,465.1
XS GIS Cut Line= 3
      1898365.02       774044.46      1898352.86       773849.79
      1898413.72       773606.34
BEGIN DESCRIPTION:
South Fork 13.0
END DESCRIPTION:
#Sta/Elev= 30
  4796.8  472.45  4802.8  470.93  4812.9  469.63  4820.7  468.34  4839.6  466.12
  4916.7  459.28  4935.4  458.03  4971.6  456.38  4979.3  452.02  4984.4  451.17
  4986.4  447.17  5013.6  447.17  5015.6  451.17  5024.7  454.45  5033.1  456.53
  5045.6  457.27  5076.7   458.4  5097.7  458.84    5117   458.9  5134.9  458.72
  5155.5  458.69  5170.3  458.88  5183.4  459.59  5188.1  460.03  5201.3  460.71
  5206.2  460.82  5212.4  464.18  5223.8  470.01  5237.8  471.08  5242.8  471.34
#Mann= 3 , 1 , 0
 4796.80    0.15       0  4984.4    0.05       0  5015.6    0.13       0
Bank Sta=4984.40,5015.60
Exp/Cntr=0.3,0.1

Type RM Length L Ch R = 1 ,7371.8,481.6,481.6,481.6
XS GIS Cut Line= 3
      1898587.61       774042.19      1898813.62       773794.37
      1898850.11       773755.12
BEGIN DESCRIPTION:
South Fork 12.0
END DESCRIPTION:
#Sta/Elev= 29
  4664.6  470.02  4669.7  469.84  4683.7  469.19  4702.3  467.99  4724.3  466.82
  4727.5  466.59  4734.8  466.12  4745.9  465.34  4751.8  464.99    4780  462.35
  4802.8  461.19  4807.4  460.73  4834.9   458.6  4846.7  457.55  4890.3  455.63
  4924.4  455.08    4965  454.98  4969.2  454.63  4971.5  454.25  4973.4  453.18
  4984.5  448.98  4986.5  444.98  5013.6  444.98  5015.6  448.98  5025.7  456.36
  5026.6  456.84  5027.4   457.4  5028.9  457.98  5053.6  471.15
#Mann= 3 , 1 , 0
 4664.60    0.15       0  4984.5    0.05       0  5015.6    0.15       0
Bank Sta=4984.50,5015.60
Exp/Cntr=0.3,0.1

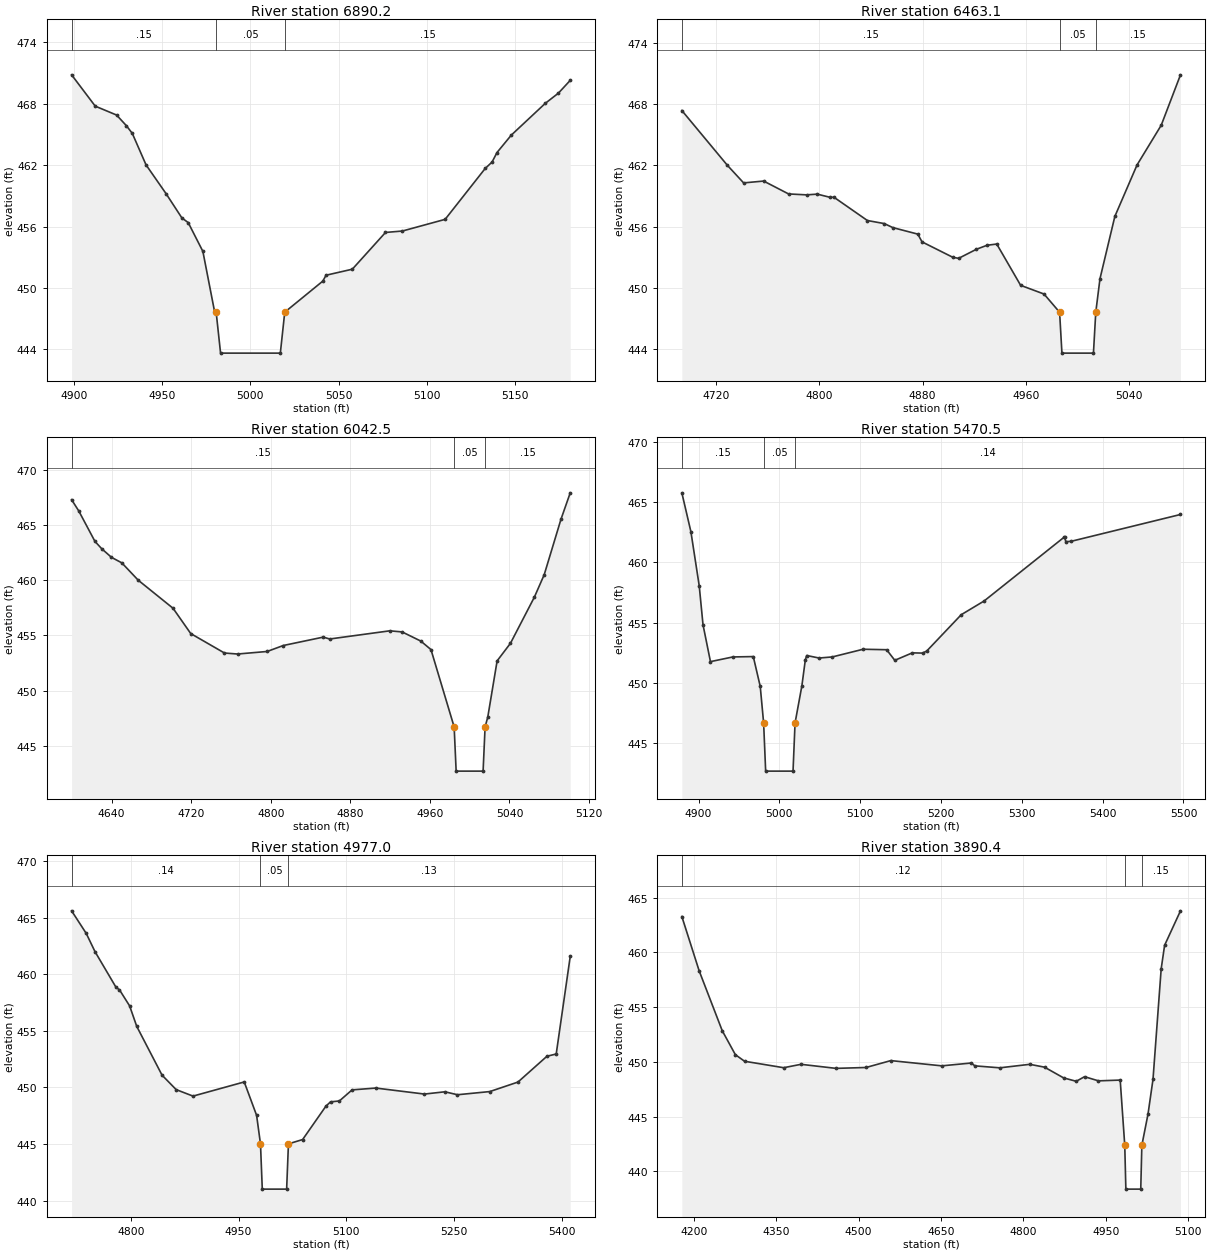
Type RM Length L Ch R = 1 ,6890.2,427.1,427.1,427.1
XS GIS Cut Line= 3
      1899033.73       774221.17      1899112.63       774157.62
      1899276.94       774081.00
BEGIN DESCRIPTION:
South Fork 11.0
END DESCRIPTION:
#Sta/Elev= 28
  4898.7  470.82  4912.1  467.76  4924.2  466.89  4929.7  465.86  4933.1   465.1
  4940.9  462.02  4952.2  459.22  4961.2  456.84  4964.8  456.38  4973.1  453.57
  4979.8  447.63 4980.63  447.63 4983.13  443.63    5017  443.63  5019.5  447.63
  5041.1  450.67  5042.9  451.24  5057.8  451.83  5076.6  455.42  5086.2  455.56
  5110.4   456.7  5133.1  461.67    5137   462.3  5139.8  463.23  5147.9  464.93
  5167.2  468.04  5174.6  469.03  5181.3  470.28
#Mann= 3 , 1 , 0
 4898.70    0.15       0 4980.63    0.05       0  5019.5    0.15       0
Bank Sta=4980.63,5019.50
Exp/Cntr=0.3,0.1

Type RM Length L Ch R = 1 ,6463.1,420.6,420.6,420.6
XS GIS Cut Line= 3
      1899133.34       774464.57      1899436.19       774426.18
      1899506.89       774387.43
BEGIN DESCRIPTION:
South Fork 10.0
END DESCRIPTION:
#Sta/Elev= 30
  4693.7  467.35    4729  461.98  4741.5  460.27    4757  460.45  4776.3  459.19
  4790.2   459.1  4798.5  459.17  4808.4  458.86  4811.4  458.87  4837.3  456.59
  4850.4  456.29  4856.9   455.9  4876.3  455.26  4879.6   454.5  4903.3     453
  4907.9  452.89  4921.7  453.78  4929.9  454.17  4937.4  454.29  4955.9  450.25
    4974   449.4 4986.05  447.62 4987.85  443.62 5012.24  443.62 5014.04  447.62
  5017.3   450.9  5028.8  456.99    5046  462.03  5064.7  465.91  5079.6  470.84
#Mann= 3 , 1 , 0
 4693.70    0.15       0 4986.05    0.05       0 5014.04    0.15       0
Bank Sta=4986.05,5014.04
Exp/Cntr=0.3,0.1

Type RM Length L Ch R = 1 ,6042.5,572,572,572
XS GIS Cut Line= 4
      1899382.31       774923.59      1899623.69       774867.16
      1899710.49       774745.63      1899771.37       774661.23
BEGIN DESCRIPTION:
South Fork 9.0
END DESCRIPTION:
#Sta/Elev= 30
  4599.8  467.28    4607  466.26  4623.3   463.5  4630.2  462.83  4639.9  462.06
  4650.3  461.56  4666.8  459.99  4701.8  457.45  4719.6  455.16  4753.5   453.4
  4766.6  453.31  4796.4  453.54  4812.6  454.08  4852.8  454.84  4859.3  454.67
  4919.7  455.41  4932.1  455.31  4950.9  454.48  4961.1  453.71  4984.4  446.71
  4986.4  442.71  5013.5  442.71  5015.5  446.71  5018.2   447.6  5027.6  452.69
    5041  454.28    5065  458.45  5074.9  460.48  5091.8  465.51  5101.1   467.9
#Mann= 3 , 1 , 0
 4599.80    0.15       0  4984.4    0.05       0  5015.5    0.15       0
Bank Sta=4984.40,5015.50
Exp/Cntr=0.3,0.1

Type RM Length L Ch R = 1 ,5470.5,493.5,493.5,493.5
XS GIS Cut Line= 3
      1899871.84       775356.02      1899934.62       775252.94
      1899899.32       774757.89
BEGIN DESCRIPTION:
South Fork 8.0
END DESCRIPTION:
#Sta/Elev= 30
  4879.3  465.79  4890.5  462.56  4900.8  458.06  4905.5  454.82  4914.7  451.76
  4942.4  452.15  4967.7  452.18  4976.3   449.7  4980.5  446.66    4983  442.66
 5016.88  442.66 5019.38  446.66  5027.8  449.74  5032.1  451.91  5033.8  452.27
  5049.1  452.06  5065.4  452.15  5103.6  452.79  5132.7  452.75  5142.8  451.87
  5164.5  452.49  5177.1  452.47  5182.3  452.64    5225  455.66  5253.3   456.8
  5351.9  462.08    5353   462.1  5354.4  461.73    5361  461.76  5496.3  463.99
#Mann= 3 , 1 , 0
 4879.30    0.15       0  4980.5    0.05       0 5019.38    0.14       0
Bank Sta=4980.50,5019.38
Exp/Cntr=0.3,0.1

Type RM Length L Ch R = 1 ,4977.0,1086.6,1086.6,1086.6
XS GIS Cut Line= 3
      1900426.96       775204.24      1900277.87       774964.63
      1900056.37       774618.08
BEGIN DESCRIPTION:
South Fork 7.0
END DESCRIPTION:
#Sta/Elev= 30
  4717.8   465.6  4738.2   463.6  4750.3     462  4779.6  458.84  4784.4  458.62
  4798.5   457.2  4808.4  455.39  4843.6  451.08  4863.3   449.8  4886.7  449.23
  4957.9  450.48  4975.1  447.53  4980.5  445.01    4983  441.01 5016.88  441.01
 5019.38  445.01  5039.1  445.39  5071.5  448.34  5077.9  448.72  5090.2   448.8
  5107.9  449.78    5141  449.94  5208.6  449.41    5237  449.61  5254.5  449.35
  5299.4  449.63  5338.6  450.47  5378.9  452.75  5391.8  452.95  5411.3  461.57
#Mann= 3 , 1 , 0
 4717.80    0.14       0  4980.5    0.05       0 5019.38    0.13       0
Bank Sta=4980.50,5019.38
Exp/Cntr=0.3,0.1

Type RM Length L Ch R = 1 ,3890.4,506.5,506.5,506.5
XS GIS Cut Line= 4
      1900442.89       775168.53      1900338.97       774978.27
      1900717.87       774507.00      1900771.84       774440.16
BEGIN DESCRIPTION:
South Fork 6.0
END DESCRIPTION:
#Sta/Elev= 30
  4178.5  463.28    4210  458.32    4252  452.85  4275.9  450.66  4292.6  450.06
  4363.8  449.47  4395.3  449.78  4459.2  449.41  4513.6  449.49  4558.8  450.12
  4651.5  449.64  4705.4   449.9  4711.6  449.64  4757.1  449.46  4811.7  449.78
  4838.5  449.52  4873.2  448.54  4896.2  448.23  4911.3  448.65  4936.7  448.27
  4976.2  448.34  4984.5  442.38  4986.5  438.38  5013.6  438.38  5015.6  442.38
  5026.8  445.23  5035.9  448.41  5050.8  458.51    5057  460.65  5085.9   463.8
#Mann= 3 , 1 , 0
 4178.50    0.12       0  4984.5    0.05       0  5015.6    0.15       0
Bank Sta=4984.50,5015.60
Exp/Cntr=0.3,0.1

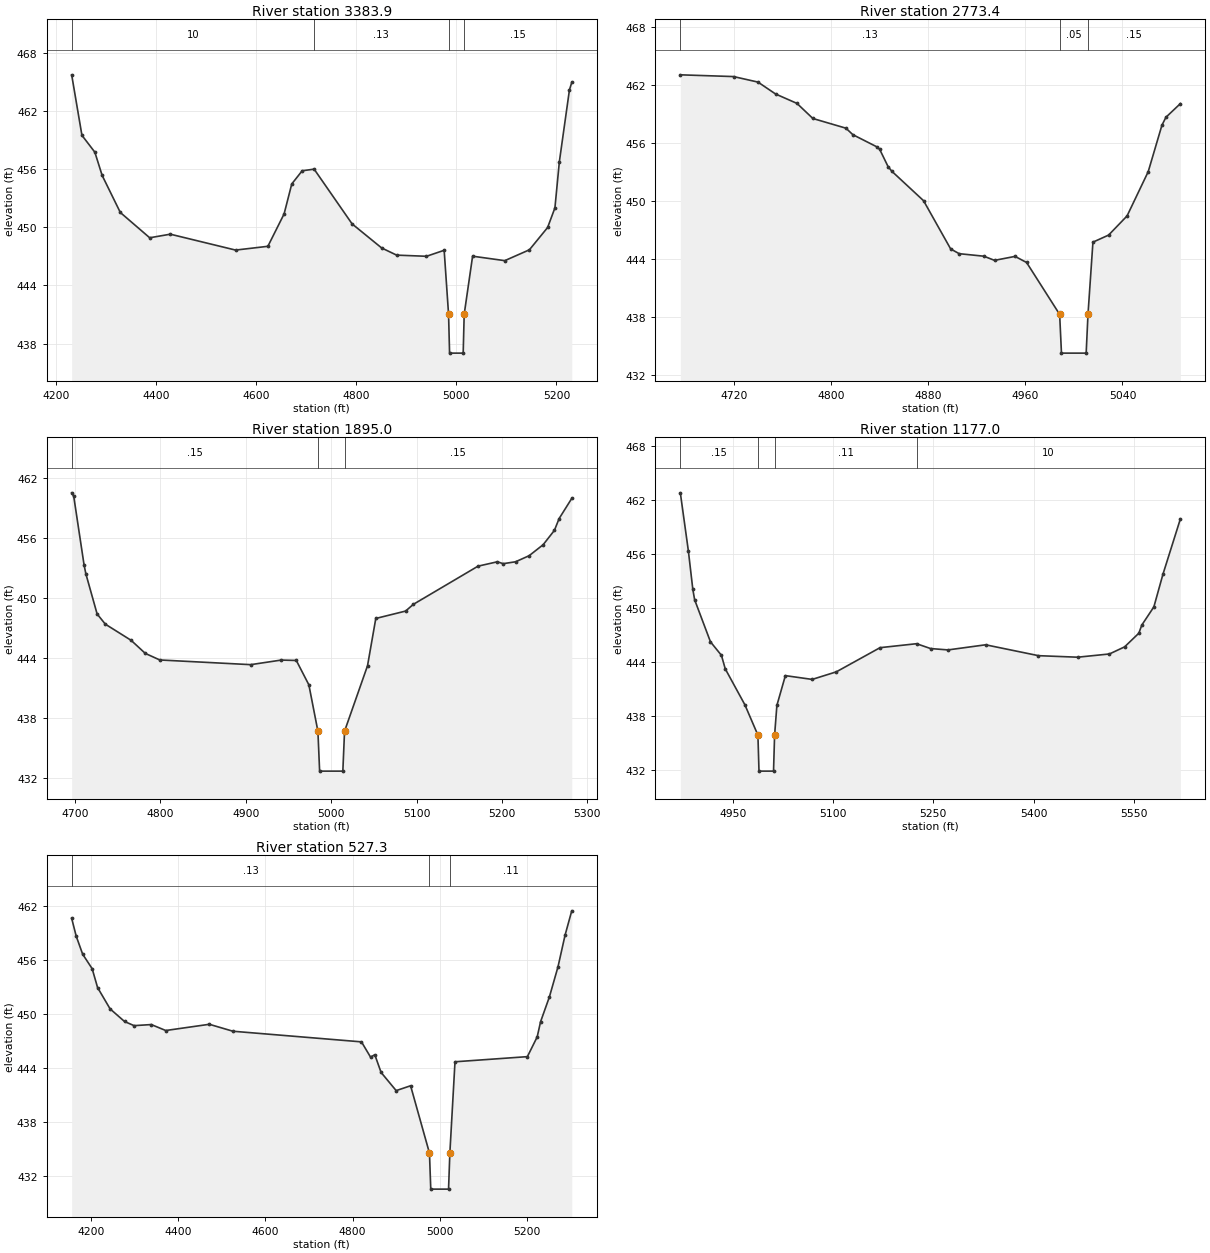
Type RM Length L Ch R = 1 ,3383.9,610.5,610.5,610.5
XS GIS Cut Line= 3
      1900633.62       775354.19      1901128.00       774765.69
      1901273.90       774587.24
BEGIN DESCRIPTION:
South Fork 5.0
END DESCRIPTION:
#Sta/Elev= 30
  4231.4  465.73  4251.9  459.49  4277.7  457.75  4292.3  455.35  4328.6  451.53
  4387.3  448.92  4428.5  449.29  4558.9  447.65  4623.4  448.04  4655.8  451.38
  4671.1  454.47  4691.9  455.83  4715.8     456  4791.7  450.35  4850.7  447.87
  4880.6  447.13  4940.3  447.01  4975.6  447.63  4984.4  441.02  4986.4  437.02
  5013.6  437.02  5015.6  441.02  5032.4  447.02  5096.7  446.56  5145.9  447.68
  5182.3  449.98  5196.9  452.01  5205.7  456.75  5225.9  464.18  5230.5  464.94
#Mann= 4 , 1 , 0
 4231.40      10       0  4715.8    0.13       0  4984.4    0.05       0
  5015.6    0.15       0
Bank Sta=4984.40,5015.60
Exp/Cntr=0.3,0.1

Type RM Length L Ch R = 1 ,2773.4,878.4,878.4,878.4
XS GIS Cut Line= 4
      1901292.28       775212.64      1901298.16       775207.87
      1901587.12       775079.19      1901668.73       775047.05
BEGIN DESCRIPTION:
South Fork 4.0
END DESCRIPTION:
#Sta/Elev= 30
  4676.1  463.05  4719.9  462.87    4740   462.3  4754.5  461.07  4772.1   460.1
  4785.2  458.54  4812.4  457.54  4818.1  456.87  4837.9  455.61  4840.2  455.35
  4847.1  453.57  4850.2  453.09  4876.3  450.05  4898.6  445.07  4905.6  444.58
  4925.9  444.32  4934.7  443.89  4951.6   444.3  4961.1  443.67  4988.3  438.31
  4989.8  434.31 5010.13  434.31 5011.63  438.31  5015.7  445.77  5028.6   446.5
  5043.8  448.48  5061.2  453.05  5072.5  457.85  5075.8  458.67  5087.7  460.08
#Mann= 3 , 1 , 0
 4676.10    0.13       0  4988.3    0.05       0 5011.63    0.15       0
Bank Sta=4988.30,5011.63
Exp/Cntr=0.3,0.1

Type RM Length L Ch R = 1 ,1895.0,718,718,718
XS GIS Cut Line= 3
      1901441.46       776058.34      1901695.63       775891.56
      1901944.19       775759.00
BEGIN DESCRIPTION:
South Fork 3.0
END DESCRIPTION:
#Sta/Elev= 30
    4696  460.56  4698.4  460.22  4710.5  453.35  4712.6  452.45  4725.8  448.42
  4735.4   447.4  4765.6  445.78  4782.2  444.47  4799.2  443.81  4905.7  443.34
  4941.4   443.8  4959.1  443.76  4973.8  441.32  4984.4  436.67  4986.4  432.67
  5013.6  432.67  5015.6  436.67  5042.5  443.23  5052.2  447.97  5087.1  448.71
  5096.1  449.38  5171.9  453.21  5194.6  453.65  5201.4  453.46  5215.9  453.65
  5231.8  454.26  5248.2  455.36  5261.4   456.8  5266.9  457.98  5281.7     460
#Mann= 3 , 1 , 0
 4696.00    0.15       0  4984.4    0.05       0  5015.6    0.15       0
Bank Sta=4984.40,5015.60
Exp/Cntr=0.3,0.1

Type RM Length L Ch R = 1 ,1177.0,649.7,649.7,649.7
XS GIS Cut Line= 3
      1901630.70       776511.81      1901758.50       776497.50
      1902253.47       776124.46
BEGIN DESCRIPTION:
South Fork 2.0
END DESCRIPTION:
#Sta/Elev= 30
  4871.4  462.77  4883.4  456.33  4890.1  452.03  4892.8  450.88  4916.5   446.2
  4932.9   444.7  4938.6   443.2    4968   439.2 4987.52  435.82 4989.12  431.82
 5010.88  431.82 5012.48  435.82  5015.9  439.13  5028.6  442.44  5068.7  442.02
  5104.8  442.86  5170.3  445.55  5224.9  445.99    5246  445.45    5272   445.3
  5328.3  445.87  5407.4  444.66  5466.1  444.49  5513.6  444.85  5536.3  445.64
  5557.6  447.16    5562  448.06  5580.1  450.09  5593.6   453.7  5619.8  459.88
#Mann= 4 , 1 , 0
 4871.40    0.15       0 4987.52    0.05       0 5012.48    0.11       0
  5224.9      10       0
Bank Sta=4987.52,5012.48
Exp/Cntr=0.3,0.1

Type RM Length L Ch R = 1 ,527.3,0,0,0
XS GIS Cut Line= 4
      1901659.46       776612.13      1902267.44       776668.50
      1902268.37       776434.69      1902282.98       776131.94
BEGIN DESCRIPTION:
South Fork 1.0
END DESCRIPTION:
#Sta/Elev= 30
  4155.6  460.58    4166   458.6  4180.8   456.6  4202.6  454.99  4215.1  452.89
  4243.8  450.53  4276.9  449.13  4298.8  448.67  4338.3  448.79  4371.5  448.13
  4471.5  448.82  4525.6  448.05  4820.6  446.87  4841.4  445.18  4851.2  445.44
  4865.6  443.48  4900.2  441.46  4933.3     442  4976.6  434.53  4979.6  430.53
  5020.4  430.53  5023.4  434.53  5035.2  444.66  5201.3  445.23  5223.8  447.42
  5231.6  449.11  5251.9  451.87  5271.6  455.21  5287.7   458.7  5303.1  461.41
#Mann= 3 , 1 , 0
 4155.60    0.13       0  4976.6   0.045       0  5023.4    0.11       0
Bank Sta=4976.60,5023.40
Exp/Cntr=0.3,0.1

Chan Stop Cuts=-1